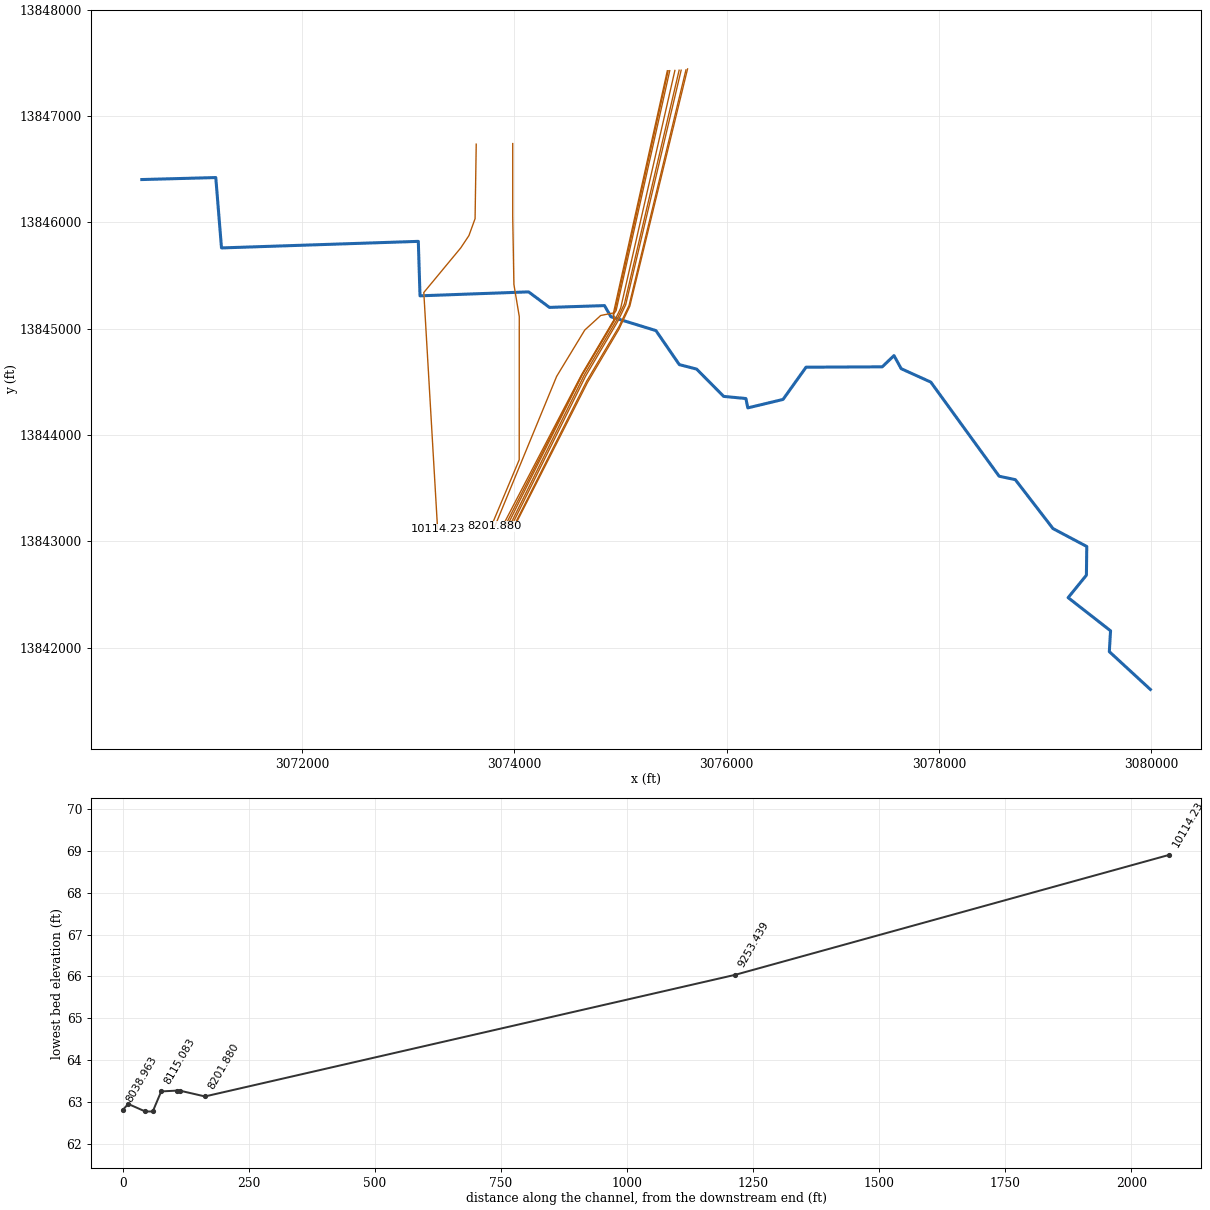
--- W141-00-00.prj (project) ---

Proj Title=W141-00-00
Current Plan=p05
Default Exp/Contr=.3,.1
English Units
Geom File=g01
Flow File=f02
Flow File=f01
Plan File=p04
Plan File=p05
Y Axis Title=Elevation
X Axis Title(PF)=Main Channel Distance
X Axis Title(XS)=Station
BEGIN DESCRIPTION:
Buffalo Bayou
HCFCD Unit W141-00-00
Flood Hazard Model
10, 2, 1, 0.2% Events
Filename W141_00_00prj
Prepared By: Sean Sutton    DATE:
Reviewed By: Joe Barrow, P.E.
Status Final RAS
END DESCRIPTION:
DSS File=dss
DSS Export Rating Curves= 0
DSS Export Rating Curve Sorted= 0
DSS Export Volume Flow Curves= 0
DXF OffsetX= 0
DXF OffsetY= 0
DXF ScaleX= 1
DXF ScaleY= 10

--- W141-00-00.p05 (plan) ---

Plan Title=Floodway
Version=Version 3.0.1  Mar 2001
Short Identifier=Floodway0607
Geom File=g01
Flow File=f01
Subcritical Flow
K Sum by GR= 0
Std Step Tol= 0.01
Critical Tol= 0.01
Num of Std Step Trials= 20
Max Error Tol= 0.3
Flow Tol Ratio= 0.001
Split Flow NTrial= 30
Split Flow Tol= 0.02
Split Flow Ratio= 0.02
Log Output Level= 0
Friction Slope Method= 0
Unsteady Friction Slope Method= 2
Secant Critical Depth
Global Vel Dist= 0 , 0 , 0
Global Log Level= 0
CheckData=True
Encroach Param=-1 ,0,0, 2
Encroach River=W141_00_00
Encroach Reach=1
Encroach Node=10114.23
       1 1538.29 1622.97
Encroach Node=9253.439
       1 1346.17 1438.03
Encroach Node=8201.880
       1 2322.88 2421.68
Encroach Node=8151.557
       1 2318.27 2422.68
Encroach Node=8146.522
       1 2306.96 2433.65
Encroach Node=8135.75
       1 2286.96 2453.65
Encroach Node=8115.083
       1 2306.09 2413.15
Encroach Node=8098.356
       1 2317.03 2440.75
Encroach Node=8083.565
       1 2329.62 2449.86
Encroach Node=8077.768
       1 2309.62 2449.66
Encroach Node=8049.722
       1 2330.08 2468.07
Encroach Node=8038.963
       1 2361.07 2505.56
Encroach Node=8027.744
       1 2361.07 2505.56
Encroach Node=7991.914
       1 2356.87 2515.81
Encroach Node=7973.083
       1  2335.1 2490.75
Encroach Node=7939.783
       1 2367.89  2514.8
Encroach Node=7882.760
       1 2388.27    2547
Encroach Node=7866.413
       1 2395.42 2568.34
Encroach Node=7845.009
       1 2395.34 2535.34
Encroach Node=7830.238
       1 2339.34 2458.53
Encroach Node=7820.418
       1 2244.07 2363.94
Encroach Node=7806.694
       1 2213.69 2331.78
Encroach Node=7795.973
       1 2220.35 2293.78
Encroach Node=7767.664
       1 2228.35 2258.84
Encroach Node=7743.821
       1 2234.89 2271.21
Encroach Node=7700.353
       11952.437 1978.57
Encroach Node=7618.764
       1 2368.18 2407.23
Encroach Node=7593.775
       1 2400.19 2453.16
Encroach Node=7583.359
       1    2410    2490
Encroach Node=7570.627
       1 2451.05  2500.6
Encroach Node=7522.670
       1  2522.3 2562.44
Encroach Node=7414.014
       1 2604.45 2646.38
Encroach Node=7389.206
       1 2624.61 2676.24
Encroach Node=7381.507
       1 2604.61  2703.3
Encroach Node=7371.952
       1 2660.87  2693.3
Encroach Node=7276.310
       1 2697.57 2727.94
Encroach Node=7194.230
       1 2756.33 2772.19
Encroach Node=7148.635
       1 3293.26    3309
Encroach Node=7139.69
       1 3293.26 3350.95
Encroach Node=7114.157
       1 3327.76 3350.95
Encroach Node=7110.373
       1 3333.82 3357.58
Encroach Node=7067.906
       1 3351.42 3372.82
Encroach Node=7062.424
       1 3360.05 3379.06
Encroach Node=7049.029
       1 3373.81 3388.89
Encroach Node=7037.984
       1 3373.81 3421.85
Encroach Node=7023.681
       1 3405.75 3421.85
Encroach Node=6990.267
       1 3422.58 3448.98
Encroach Node=6956.397
       1 3423.47 3448.13
Encroach Node=6914.924
       1 3423.47 3957.85
Encroach Node=6864.223
       1 3903.67 3977.85
Encroach Node=6833.652
       1 3951.55  3997.2
Encroach Node=6553.388
       1 3888.23 3926.62
Encroach Node=6409.043
       1 3979.27 4004.96
Encroach Node=6389.812
       1 3975.26 3998.58
Encroach Node=6375.626
       1 3974.83 3998.58
Encroach Node=6354.587
       1 3974.83 3990.87
Encroach Node=6349.317
       1 3980.86 3996.98
Encroach Node=6341.332
       1  3982.2 3999.18
Encroach Node=6319.752
       1 3977.02 4016.16
Encroach Node=6296.250
       1 3988.81 4016.16
Encroach Node=6292.586
       1 3988.81 4016.16
Encroach Node=6288.734
       1  3991.4 4018.71
Encroach Node=6271.804
       1 3985.43 4019.36
Encroach Node=6256.793
       1 3985.43 4014.03
Encroach Node=6245.423
       1 3985.14 4006.07
Encroach Node=6234.085
       1 3985.14 4006.07
Encroach Node=6209.944
       1 3973.45 4008.58
Encroach Node=6195.311
       1 3973.45 3999.39
Encroach Node=6148.740
       1  3954.9 3974.56
Encroach Node=6105.910
       1  3949.1 3978.96
Encroach Node=6073.959
       1 3948.99 3977.74
Encroach Node=6060.694
       1 3929.46 3977.74
Encroach Node=6048.197
       1 3929.46  3957.9
Encroach Node=6031.563
       1 3913.98 3944.05
Encroach Node=5926.574
       1 3821.38 3851.26
Encroach Node=5815.421
       1 3773.92 3794.29
Encroach Node=5681.828
       1 3631.08 3661.46
Encroach Node=5646.093
       1 3571.06 3599.92
Encroach Node=5637.279
       1 3569.31 3603.85
Encroach Node=5608.713
       1 3571.49 3603.85
Encroach Node=5549.795
       1 3594.09  3642.4
Encroach Node=5544.457
       1 3594.09  3642.4
Encroach Node=5521.918
       1 3594.09  3642.4
Encroach Node=5511.598
       1 3594.66 3632.88
Encroach Node=5504.240
       1 3594.66 3632.88
Encroach Node=5496.916
       1 3593.02 3630.45
Encroach Node=5485.204
       1 3593.02 3650.31
Encroach Node=5458.022
       1 3619.44 3650.31
Encroach Node=5444.518
       1  3618.3 3649.16
Encroach Node=5441.061
       1 3623.98  3655.4
Encroach Node=5435.628
       1 3615.71 3656.65
Encroach Node=5408.428
       1 3615.71 3642.16
Encroach Node=5401.302
       1 3615.71 3642.16
Encroach Node=5395.153
       1 3619.41 3645.61
Encroach Node=5379.058
       1 3616.79 3648.24
Encroach Node=5349.312
       1 3616.46 3647.91
Encroach Node=5317.732
       1 3604.98 3643.32
Encroach Node=5288.194
       1 3606.36 3641.99
Encroach Node=5260.007
       1  3553.6 3641.99
Encroach Node=5213.492
       1  3553.6 3595.65
Encroach Node=5139.392
       1 3059.723095.123
Encroach Node=5036.027
       1 2521.61 2544.78
Encroach Node=4988.462
       1    2520 2568.16
Encroach Node=4969.850
       1 2538.82 2568.16
Encroach Node=4936.753
       13590.439 3631.92
Encroach Node=4850.701
       1 3609.12 3631.47
Encroach Node=4809.538
       1 3146.18 3631.47
Encroach Node=4654.685
       1 3190.68  3204.2
Encroach Node=4565.523
       1 2995.48 3011.39
Encroach Node=4552.487
       1 2971.11 2984.26
Encroach Node=4534.222
       1 2965.25 2985.68
Encroach Node=4527.715
       1 2965.25 2981.23
Encroach Node=4511.651
       1 2966.19  2981.1
Encroach Node=4432.070
       1 2972.46 3011.57
Encroach Node=4208.957
       1  2805.1 2864.03
Encroach Node=4129.772
       1 2878.16 2932.41
Encroach Node=4076.464
       1 2878.16 2976.03
Encroach Node=4016.785
       1 2917.81 2976.03
Encroach Node=3943.477
       1 3060.58 3127.15
Encroach Node=3903.974
       1 3100.49 3167.05
Encroach Node=3856.288
       1 3100.49 3261.73
Encroach Node=3802.434
       1 3168.14 3261.73
Encroach Node=3750.099
       1 3226.69 3271.94
Encroach Node=3671.149
       1 3434.69  3486.8
Encroach Node=3608.031
       1 3445.31 3484.24
Encroach Node=3556.088
       4       1
Encroach Node=3495.269
       1 3436.54 3486.11
Encroach Node=3337.755
       1 3588.08 3623.59
Encroach Node=3160.339
       1 3668.99 3690.64
Encroach Node=3101.713
       1 3703.28 3725.86
Encroach Node=3075.750
       1 3703.53 3745.08
Encroach Node=3037.026
       4       1
Encroach Node=3006.604
       1 3715.78 3754.99
Encroach Node=2904.206
       1 3771.91 3802.21
Encroach Node=2561.522
       1 4029.68 4168.43
Encroach Node=2502.920
       1 3980.58 4132.47
Encroach Node=2483.371
       1 3936.23 4088.35
Encroach Node=2473.321
       1  3915.3 4088.68
Encroach Node=2460.015
       1  3915.3 4068.08
Encroach Node=2446.541
       1 3907.99 4061.55
Encroach Node=2360.616
       1  3790.3 3942.13
Encroach Node=2296.416
       1 2655.33 2758.05
Encroach Node=2234.76
       4       1
Encroach Node=2186.569
       1 3671.83 3764.61
Encroach Node=2054.156
       1 2613.462659.266
Encroach Node=1377.100
       1 1848.95 1888.28
Encroach Node=984.840
       1 1560.55 1593.88
Encroach Node=9.814
       1  181.12   227.5
Encroach Reach=W141-00-00_0000
Encroach Node=10114.23
       1 1538.29 1622.97
Encroach Node=9253.439
       1 1346.17 1438.03
Encroach Node=8201.880
       1 2322.88 2421.68
Encroach Node=8151.557
       1 2318.27 2422.68
Encroach Node=8146.522
       1 2306.96 2433.65
Encroach Node=8135.75
       1 2286.96 2453.65
Encroach Node=8115.083
       1 2306.09 2413.15
Encroach Node=8098.356
       1 2317.03 2440.75
Encroach Node=8083.565
       1 2329.62 2449.86
Encroach Node=8077.768
       1 2309.62 2449.66
Encroach Node=8049.722
       1 2330.08 2468.07
Encroach Node=8038.963
       1 2361.07 2505.56
Encroach Node=8027.744
       1 2361.07 2505.56
Encroach Node=7991.914
       1 2356.87 2515.81
Encroach Node=7973.083
       1  2335.1 2490.75
Encroach Node=7939.783
       1 2367.89  2514.8
Encroach Node=7882.760
       1 2388.27    2547
Encroach Node=7866.413
       1 2395.42 2568.34
Encroach Node=7845.009
       1 2395.34 2535.34
Encroach Node=7830.238
       1 2339.34 2458.53
Encroach Node=7820.418
       1 2244.07 2363.94
Encroach Node=7806.694
       1 2213.69 2331.78
Encroach Node=7795.973
       1 2220.35 2293.78
Encroach Node=7767.664
       1 2228.35 2258.84
Encroach Node=7743.821
       1 2234.89 2271.21
Encroach Node=7700.353
       11952.437 1978.57
Encroach Node=7618.764
       1 2368.18 2407.23
Encroach Node=7593.775
       1 2400.19 2453.16
Encroach Node=7583.359
       1    2410    2490
Encroach Node=7570.627
       1 2451.05  2500.6
Encroach Node=7522.670
       1  2522.3 2562.44
Encroach Node=7414.014
       1 2604.45 2646.38
Encroach Node=7389.206
       1 2624.61 2676.24
Encroach Node=7381.507
       1 2604.61  2703.3
Encroach Node=7371.952
       1 2660.87  2693.3
Encroach Node=7276.310
       1 2697.57 2727.94
Encroach Node=7194.230
       1 2756.33 2772.19
Encroach Node=7148.635
       1 3293.26    3309
Encroach Node=7139.69
       1 3293.26 3350.95
Encroach Node=7114.157
       1 3327.76 3350.95
Encroach Node=7110.373
       1 3333.82 3357.58
Encroach Node=7067.906
       1 3351.42 3372.82
Encroach Node=7062.424
       1 3360.05 3379.06
Encroach Node=7049.029
       1 3373.81 3388.89
Encroach Node=7037.984
       1 3373.81 3421.85
Encroach Node=7023.681
       1 3405.75 3421.85
Encroach Node=6990.267
       1 3422.58 3448.98
Encroach Node=6956.397
       1 3423.47 3448.13
Encroach Node=6914.924
       1 3423.47 3957.85
Encroach Node=6864.223
       1 3903.67 3977.85
Encroach Node=6833.652
       1 3951.55  3997.2
Encroach Node=6553.388
       1 3888.23 3926.62
Encroach Node=6409.043
       1 3979.27 4004.96
Encroach Node=6389.812
       1 3975.26 3998.58
Encroach Node=6375.626
       1 3974.83 3998.58
Encroach Node=6354.587
       1 3974.83 3990.87
Encroach Node=6349.317
       1 3980.86 3996.98
Encroach Node=6341.332
       1  3982.2 3999.18
Encroach Node=6319.752
       1 3977.02 4016.16
Encroach Node=6296.250
       1 3988.81 4016.16
Encroach Node=6292.586
       1 3988.81 4016.16
Encroach Node=6288.734
       1  3991.4 4018.71
Encroach Node=6271.804
       1 3985.43 4019.36
Encroach Node=6256.793
       1 3985.43 4014.03
Encroach Node=6245.423
       1 3985.14 4006.07
Encroach Node=6234.085
       1 3985.14 4006.07
Encroach Node=6209.944
       1 3973.45 4008.58
Encroach Node=6195.311
       1 3973.45 3999.39
Encroach Node=6148.740
       1  3954.9 3974.56
Encroach Node=6105.910
       1  3949.1 3978.96
Encroach Node=6073.959
       1 3948.99 3977.74
Encroach Node=6060.694
       1 3929.46 3977.74
Encroach Node=6048.197
       1 3929.46  3957.9
Encroach Node=6031.563
       1 3913.98 3944.05
Encroach Node=5926.574
       1 3821.38 3851.26
Encroach Node=5815.421
       1 3773.92 3794.29
Encroach Node=5681.828
       1 3631.08 3661.46
Encroach Node=5646.093
       1 3571.06 3599.92
Encroach Node=5637.279
       1 3569.31 3603.85
Encroach Node=5608.713
       1 3571.49 3603.85
Encroach Node=5549.795
       1 3594.09  3642.4
Encroach Node=5544.457
       1 3594.09  3642.4
Encroach Node=5521.918
       1 3594.09  3642.4
Encroach Node=5511.598
       1 3594.66 3632.88
Encroach Node=5504.240
       1 3594.66 3632.88
Encroach Node=5496.916
       1 3593.02 3630.45
Encroach Node=5485.204
       1 3593.02 3650.31
Encroach Node=5458.022
       1 3619.44 3650.31
Encroach Node=5444.518
       1  3618.3 3649.16
Encroach Node=5441.061
       1 3623.98  3655.4
Encroach Node=5435.628
       1 3615.71 3656.65
Encroach Node=5408.428
       1 3615.71 3642.16
Encroach Node=5401.302
       1 3615.71 3642.16
Encroach Node=5395.153
       1 3619.41 3645.61
Encroach Node=5379.058
       1 3616.79 3648.24
Encroach Node=5349.312
       1 3616.46 3647.91
Encroach Node=5317.732
       1 3604.98 3643.32
Encroach Node=5288.194
       1 3606.36 3641.99
Encroach Node=5260.007
       1  3553.6 3641.99
Encroach Node=5213.492
       1  3553.6 3595.65
Encroach Node=5139.392
       1 3059.723095.123
Encroach Node=5036.027
       1 2521.61 2544.78
Encroach Node=4988.462
       1    2520 2568.16
Encroach Node=4969.850
       1 2538.82 2568.16
Encroach Node=4936.753
       13590.439 3631.92
Encroach Node=4850.701
       1 3609.12 3631.47
Encroach Node=4809.538
       1 3146.18 3631.47
Encroach Node=4654.685
       1 3190.68  3204.2
Encroach Node=4565.523
       1 2995.48 3011.39
Encroach Node=4552.487
       1 2971.11 2984.26
Encroach Node=4534.222
       1 2965.25 2985.68
Encroach Node=4527.715
       1 2965.25 2981.23
Encroach Node=4511.651
       1 2966.19  2981.1
Encroach Node=4432.070
       1 2972.46 3011.57
Encroach Node=4208.957
       1  2805.1 2864.03
Encroach Node=4129.772
       1 2878.16 2932.41
Encroach Node=4076.464
       1 2878.16 2976.03
Encroach Node=4016.785
       1 2917.81 2976.03
Encroach Node=3943.477
       1 3060.58 3127.15
Encroach Node=3903.974
       1 3100.49 3167.05
Encroach Node=3856.288
       1 3100.49 3261.73
Encroach Node=3802.434
       1 3168.14 3261.73
Encroach Node=3750.099
       1 3226.69 3271.94
Encroach Node=3671.149
       1 3434.69  3486.8
Encroach Node=3608.031
       1 3445.31 3484.24
Encroach Node=3556.088
       4       1
Encroach Node=3495.269
       1 3436.54 3486.11
Encroach Node=3337.755
       1 3588.08 3623.59
Encroach Node=3160.339
       1 3668.99 3690.64
Encroach Node=3101.713
       1 3703.28 3725.86
Encroach Node=3075.750
       1 3703.53 3745.08
Encroach Node=3037.026
       4       1
Encroach Node=3006.604
       1 3715.78 3754.99
Encroach Node=2904.206
       1 3771.91 3802.21
Encroach Node=2561.522
       1 4029.68 4168.43
Encroach Node=2502.920
       1 3980.58 4132.47
Encroach Node=2483.371
       1 3936.23 4088.35
Encroach Node=2473.321
       1  3915.3 4088.68
Encroach Node=2460.015
       1  3915.3 4068.08
Encroach Node=2446.541
       1 3907.99 4061.55
Encroach Node=2360.616
       1  3790.3 3942.13
Encroach Node=2296.416
       1 2655.33 2758.05
Encroach Node=2234.76
       4       1
Encroach Node=2186.569
       1 3671.83 3764.61
Encroach Node=2054.156
       1 2613.462659.266
Encroach Node=1377.100
       1 1848.95 1888.28
Encroach Node=984.840
       1 1560.55 1593.88
Encroach Node=9.814
       1  181.12   227.5
Computation Interval=1HOUR
Output Interval=1HOUR
Run HTab= 0
Run UNet= 0
Run PostProcess= 0
UNET Theta= 1
UNET ZTol= 0.02
UNET ZSATol= 0.1
UNET MxIter= 20
UNET MaxInSteps= 20
UNET DtIC= 0
UNET DtMin= 0
UNET MaxCRTS= 20
UNET WFStab= 2
UNET SFStab= 1
UNET WFX= 1
UNET SFX= 1
UNET Convert EG Bridges=-1
UNET Use Existing IB Tables=-1
Instantaneous Interval=1HOUR
DSS File=dss
Write IC File= 0
IC Time=0
Write Velocity= 0
Write Detailed= 0

--- W141-00-00.p04 (plan) ---

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Plan Title=FEMA Effective June 2007
Short Identifier=FEMAeff0607
Geom File=g01
Flow File=f02
Encroach Param=-1 ,0,0, 0

--- W141-00-00.f01 (steady flow) ---

Flow Title=Floodway
Program Version=3.13
Number of Profiles= 2
Profile Names=1PCT_100_YR,1PCT_Floodway_100yrFW
River Rch & RM=W141_00_00,W141-00-00_0000               ,10114.23
     293     293
River Rch & RM=W141_00_00,W141-00-00_0000               ,9253.439
     338     338
River Rch & RM=W141_00_00,W141-00-00_0000               ,8201.880
     414     414
River Rch & RM=W141_00_00,W141-00-00_0000               ,7806.694
     446     446
River Rch & RM=W141_00_00,W141-00-00_0000               ,7700.353
     451     451
River Rch & RM=W141_00_00,W141-00-00_0000               ,7049.029
     485     485
River Rch & RM=W141_00_00,W141-00-00_0000               ,6409.043
     515     515
River Rch & RM=W141_00_00,W141-00-00_0000               ,5926.574
     539     539
River Rch & RM=W141_00_00,W141-00-00_0000               ,5544.457
     571     571
River Rch & RM=W141_00_00,W141-00-00_0000               ,5036.027
     615     615
River Rch & RM=W141_00_00,W141-00-00_0000               ,4850.701
     647     647
River Rch & RM=W141_00_00,W141-00-00_0000               ,4432.070
     666     666
River Rch & RM=W141_00_00,W141-00-00_0000               ,3943.477
     702     702
River Rch & RM=W141_00_00,W141-00-00_0000               ,3160.339
     759     759
River Rch & RM=W141_00_00,W141-00-00_0000               ,2561.522
     814     814
River Rch & RM=W141_00_00,W141-00-00_0000               ,2296.416
     848     848
River Rch & RM=W141_00_00,W141-00-00_0000               ,984.840
     894     894
Boundary for River Rch & Prof#=W141_00_00,W141-00-00_0000               , 1
Up Type= 0
Dn Type= 3
Dn Slope=0.006
Boundary for River Rch & Prof#=W141_00_00,W141-00-00_0000               , 2
Up Type= 0
Dn Type= 3
Dn Slope=0.006
DSS Import GetInterval= 0
DSS Import GetPeak= 0
DSS Import FillOption= 0

--- W141-00-00.f02 (steady flow) ---

Flow Title=FEMA Effective June 2007
Program Version=3.13
Number of Profiles= 4
Profile Names=10PCT_10yr,2PCT_50yr,1PCT_100yr,0.2PCT_500yr
River Rch & RM=W141_00_00,W141-00-00_0000 ,10114.23
     156     245     293     443
River Rch & RM=W141_00_00,W141-00-00_0000 ,9253.439
     180     283     338     511
River Rch & RM=W141_00_00,W141-00-00_0000 ,8201.880
     221     347     414     626
River Rch & RM=W141_00_00,W141-00-00_0000 ,7806.694
     237     373     446     673
River Rch & RM=W141_00_00,W141-00-00_0000 ,7700.353
     240     377     451     681
River Rch & RM=W141_00_00,W141-00-00_0000 ,7049.029
     258     405     485     732
River Rch & RM=W141_00_00,W141-00-00_0000 ,6409.043
     274     431     515     778
River Rch & RM=W141_00_00,W141-00-00_0000 ,5926.574
     287     451     539     814
River Rch & RM=W141_00_00,W141-00-00_0000 ,5544.457
     304     478     571     863
River Rch & RM=W141_00_00,W141-00-00_0000 ,5036.027
     328     514     615     928
River Rch & RM=W141_00_00,W141-00-00_0000 ,4850.701
     345     541     647     977
River Rch & RM=W141_00_00,W141-00-00_0000 ,4432.070
     355     557     666    1006
River Rch & RM=W141_00_00,W141-00-00_0000 ,3943.477
     374     587     702    1060
River Rch & RM=W141_00_00,W141-00-00_0000 ,3160.339
     404     635     759    1147
River Rch & RM=W141_00_00,W141-00-00_0000 ,2561.522
     433     681     814    1229
River Rch & RM=W141_00_00,W141-00-00_0000 ,2296.416
     451     709     848    1280
River Rch & RM=W141_00_00,W141-00-00_0000 ,984.840
     476     747     894    1349
Boundary for River Rch & Prof#=W141_00_00,W141-00-00_0000 , 1
Up Type= 0
Dn Type= 3
Dn Slope=0.006
Boundary for River Rch & Prof#=W141_00_00,W141-00-00_0000 , 2
Up Type= 0
Dn Type= 3
Dn Slope=0.006
Boundary for River Rch & Prof#=W141_00_00,W141-00-00_0000 , 3
Up Type= 0
Dn Type= 3
Dn Slope=0.006
Boundary for River Rch & Prof#=W141_00_00,W141-00-00_0000 , 4
Up Type= 0
Dn Type= 3
Dn Slope=0.006
DSS Import GetInterval= 0
DSS Import GetPeak= 0
DSS Import FillOption= 0

--- W141-00-00.g01 (geometry) ---

Geom Title=W141-00-00 June 2007
Version=Version 3.0.1  Mar 2001

River Reach=W141_00_00      ,W141-00-00_0000
Reach XY= 30
     3070489.324    13846401.918     3071186.002    13846420.539
     3071239.823    13845758.913      3073094.21    13845820.594
     3073110.325    13845308.571      3074133.49    13845345.637
     3074329.629    13845199.691     3074848.547     13845216.68
     3074908.945    13845111.721     3075333.338    13844981.477
     3075553.442    13844661.733     3075716.562     13844619.61
      3075971.74    13844362.836     3076180.752    13844342.939
      3076198.85     13844254.86      3076530.79    13844334.362
     3076747.587    13844637.406     3077465.586    13844640.837
     3077576.155    13844746.451     3077644.218    13844623.249
     3077922.834     13844497.39     3078567.018    13843612.231
     3078719.268    13843580.119     3079074.103    13843120.189
     3079392.611    13842951.695     3079389.221     13842681.99
     3079217.077    13842470.671      3079616.72    13842158.912
      3079605.06    13841962.903     3079991.935    13841607.213

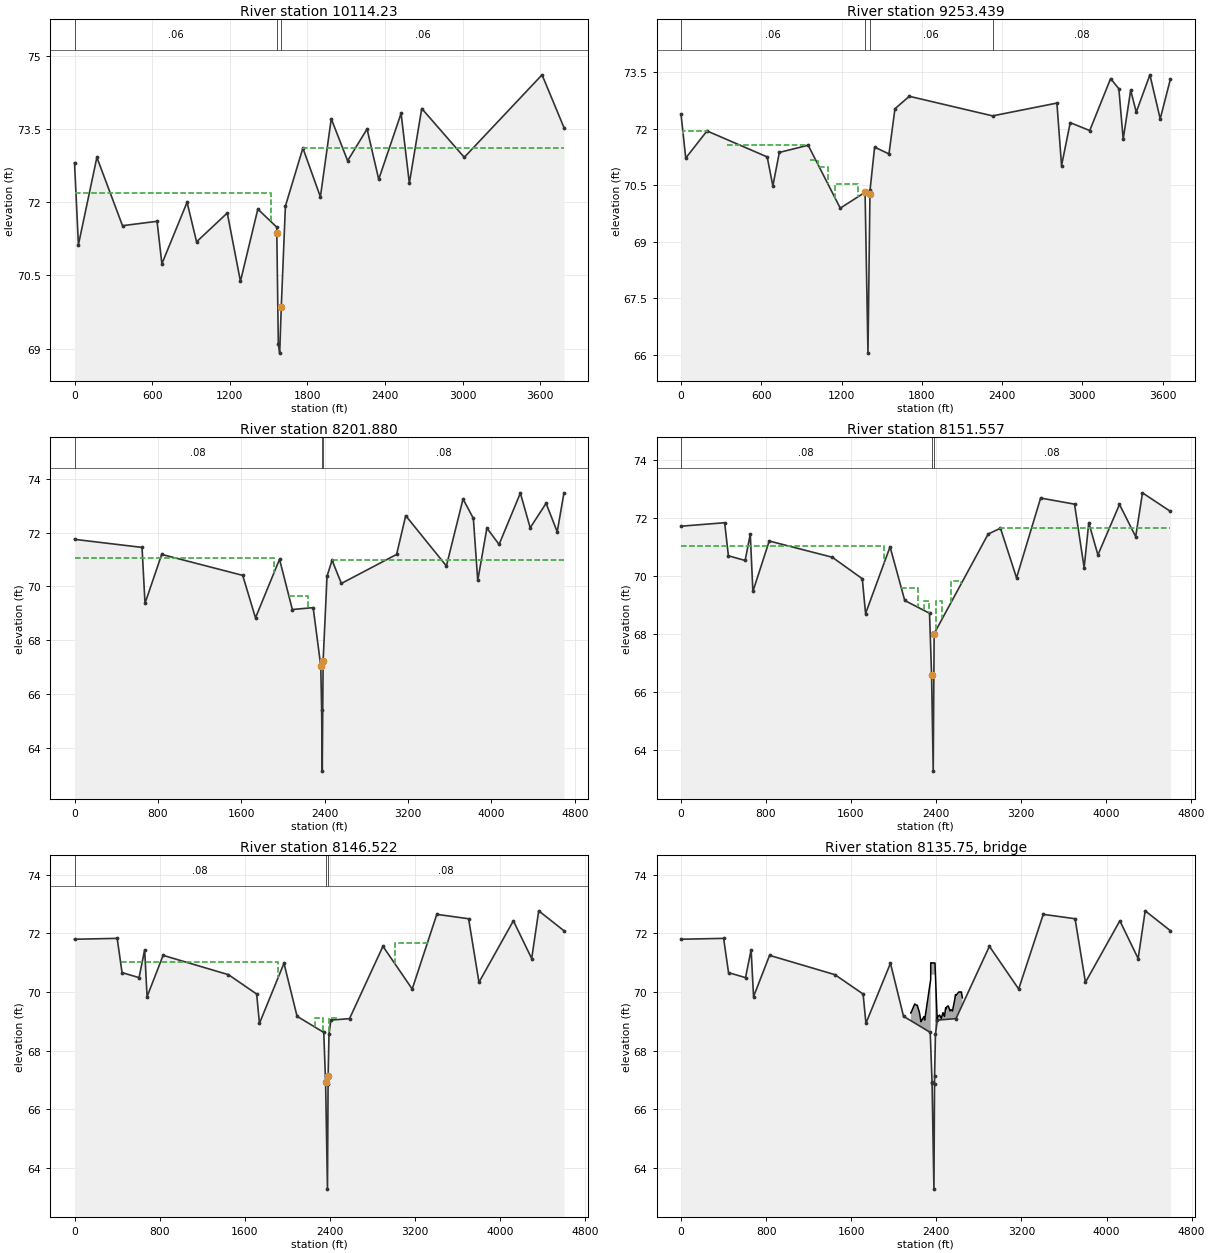
Type RM Length L Ch R = 1 ,10114.23,856.94,860.8,863.72
BEGIN DESCRIPTION:
Stations 1562.16 - 1604.62 developed from survey information, and the remainder developed from LiDAR
Blocked obstruction in the far overbank at basin divide.
END DESCRIPTION:
XS GIS Cut Line= 6
     3073639.932    13846734.443      3073629.12    13846033.858
     3073571.117    13845874.886     3073493.779    13845758.879
     3073146.006    13845339.705     3073275.908    13843115.136
#Sta/Elev= 30
       0   72.81   30.15   71.13  172.84   72.92  370.92   71.52  637.79   71.61
  675.22   70.74  869.89      72  943.28   71.19 1180.58   71.78 1282.36   70.38
 1416.63   71.86 1562.91   71.49 1563.29   71.38 1575.06    69.1 1585.47   68.91
 1597.97   69.86 1598.05   69.87 1629.72   71.92 1764.95   73.11 1900.18   72.11
 1984.19   73.71 2110.54   72.85 2260.79    73.5 2350.95   72.47 2523.83   73.82
 2587.66   72.39 2683.41   73.92 3012.07   72.92 3613.09   74.61 3782.54   73.53
#Mann= 3 ,-1 , 0
       0     .06       0 1562.91     .04       0 1598.05     .06       0
#XS Ineff= 2 , 0
         1520.54   72.19 1768.27           73.11
Permanent Ineff=
       F       F
#Block Obstruct= 2 , 0
                         3044.37           74.66
Bank Sta=1563.29,1597.97
XS Rating Curve= 0
Exp/Cntr=.3,.1

Type RM Length L Ch R = 1 ,9253.439,1092.7,1051.56,1000.05
BEGIN DESCRIPTION:
Stations 1340.4 - 1416.05 developed from survey information, and the remainder developed from LiDAR
Blocked obstruction in the far overbank at basin divide.
END DESCRIPTION:
XS GIS Cut Line= 6
     3073983.771    13846739.977     3073983.771    13846054.438
     3073994.899    13845415.827     3074045.549    13845113.743
     3074045.015    13843766.796     3073780.324    13843138.837
#Sta/Elev= 30
       0   72.39   35.68   71.22  194.51   71.94  644.51   71.25  686.82   70.48
  735.39   71.37  950.72   71.56 1190.75   69.89 1375.88   70.31 1376.17   70.31
 1397.85   66.04 1412.69   70.26 1413.13   70.36 1447.57   71.51 1554.84   71.33
 1599.58   72.53  1707.2   72.86 2329.41   72.34 2810.25   72.68    2845   71.02
 2909.85   72.16 3055.81   71.95 3211.64   73.33 3273.38   73.06 3305.77   71.72
 3361.79   73.02 3403.44   72.44 3505.48   73.43 3582.56   72.26 3658.97   73.32
#Mann= 4 ,-1 , 0
       0     .06       0 1375.88     .04       0 1413.13     .06       0
 2329.41     .08       0
#XS Ineff= 5 ,-1
   16.36  190.88   71.94  344.92  950.27   71.56  966.72 1026.71   71.16
 1037.61 1100.33   70.99 1154.86 1323.93   70.52
Permanent Ineff=
       F       F       F       F       F
#Block Obstruct= 2 , 0
                         2792.95           73.46
Bank Sta=1376.17,1412.69
XS Rating Curve= 0
Exp/Cntr=.3,.1

Type RM Length L Ch R = 1 ,8201.880,25.28,50.32,81.58
BEGIN DESCRIPTION:
Stations 2362.88 - 2387.21 developed from survey information, and the remainder developed from LiDAR
Blocked obstruction in the far overbank at basin divide.
END DESCRIPTION:
XS GIS Cut Line= 6
     3075440.561    13847424.496     3074933.105    13845147.523
     3074813.052    13845123.732      3074662.91    13844987.011
     3074397.811    13844551.478     3073815.248    13843140.651
#Sta/Elev= 30
       0   71.75  648.05   71.45  676.38   69.37  836.52   71.19 1613.82   70.41
 1736.76   68.83 1967.28   71.01 2090.22   69.14 2290.01   69.21 2362.88   67.05
 2371.56   65.41 2377.27   63.13  2385.6   67.21  2385.7   67.24  2423.1   70.38
 2471.45   70.97 2560.79   70.11 3090.94   71.19 3178.04   72.63 3568.55   70.76
 3728.09   73.25 3827.25   72.53 3869.35   70.22 3957.07   72.17 4073.92   71.56
 4278.31   73.47 4372.56   72.18 4525.07   73.09 4632.02   72.03 4696.71   73.48
#Mann= 3 ,-1 , 0
       0     .08       0 2371.56     .06       0  2385.7     .08       0
#XS Ineff= 3 ,-1
   -2.27 1911.36   71.04 2057.44 2240.85   69.65 2471.09 4696.16   70.97
Permanent Ineff=
       F       F       F
#Block Obstruct= 2 , 0
                         3723.55           73.49
Bank Sta=2362.88,2385.6
XS Rating Curve= 0
Exp/Cntr=.3,.1

Type RM Length L Ch R = 1 ,8151.557,5.35,5.03,5.63
BEGIN DESCRIPTION:
Stations 2349.64 - 2387.9 developed from survey information, and the remainder developed from LiDAR
Blocked obstruction in the far overbank at basin divide.
END DESCRIPTION:
XS GIS Cut Line= 6
     3075448.519     13847424.86     3074944.741    13845158.921
     3074930.575    13845137.685     3074935.737    13845079.264
     3074631.684    13844565.031     3073888.981    13843144.482
#Sta/Elev= 30
       0   71.71  410.96   71.83  446.19   70.69  603.66   70.53  652.13   71.44
  676.69   69.46  830.35    71.2 1424.03   70.64 1706.23    69.9 1736.96    68.7
 1967.45      71 2105.75   69.15 2338.84   68.71 2358.27   66.57  2358.6   66.52
  2373.6   63.27 2382.32   67.97 2382.68   68.01 2890.64   71.44 3006.51   71.64
 3157.69   69.93 3384.31   72.68 3703.29   72.47 3793.85   70.28 3837.56   71.83
 3923.33   70.72 4126.45   72.46 4278.79   71.35 4342.85   72.86 4605.82   72.22
#Mann= 3 ,-1 , 0
       0     .08       0  2358.6     .06       0 2382.32     .08       0
#XS Ineff= 6 ,-1
   -3.68 1909.95   71.03 2067.39 2230.24   69.57 2286.08 2334.93   69.12
 2400.07 2460.56   69.12 2537.33 2635.04   69.83 2998.27 4605.26   71.65
Permanent Ineff=
       F       F       F       F       F       F
#Block Obstruct= 2 , 0
                         3450.51           72.85
Bank Sta=2358.27,2382.68
XS Rating Curve= 0
Exp/Cntr=.5,.3

Type RM Length L Ch R = 1 ,8146.522,44.76,31.44,19.09
BEGIN DESCRIPTION:
Stations 2353.61 - 2391.87 developed from survey information (copied from cross-section 8151.56) , and the remainder developed from LiDAR.
Blocked obstruction in the far overbank at basin divide.
END DESCRIPTION:
XS GIS Cut Line= 6
     3075463.363    13847425.537     3074958.014    13845170.055
     3074935.604    13845137.685     3074940.766    13845079.264
     3074637.152     13844567.98     3073912.145    13843145.685
#Sta/Elev= 30
       0    71.8  400.94   71.83  447.05   70.66   606.7   70.49  659.32   71.44
  682.04   69.84  832.74   71.25 1447.25   70.59 1711.82   69.93 1738.29   68.93
 1968.87   70.98 2091.84   69.17 2342.73   68.62 2359.96   66.91 2360.05    66.9
 2377.57   63.27 2383.24   66.85 2383.65   67.12 2391.87   68.55 2409.42   69.04
 2584.97   69.09 2898.96   71.56 3174.08    70.1 3405.29   72.65  3704.1    72.5
 3801.64   70.33 4125.01   72.43 4297.07   71.14 4363.13   72.77 4600.49   72.09
#Mann= 3 ,-1 , 0
       0     .08       0 2360.05     .06       0 2383.24     .08       0
#XS Ineff= 4 ,-1
  432.31 1911.26   71.02 2259.13 2340.07   69.12 2394.82 2463.86   69.12
 3014.79 3339.02   71.68
Permanent Ineff=
       F       F       F       F
#Block Obstruct= 2 , 0
                         3492.61            72.8
Bank Sta=2359.96,2383.65
XS Rating Curve= 0
Exp/Cntr=.5,.3

Type RM Length L Ch R = 3 ,8135.75 ,,,
BEGIN DESCRIPTION:
Structure 33 - unnamed wood bridge
Structure 33
END DESCRIPTION:
Bridge Culvert--1,0,-1,-1, 0
Deck Dist Width WeirC Skew NumUp NumDn MinLoCord MaxHiCord MaxSubmerge Is_Ogee
7.5,9,2.6,0, 48, 56, , , .95, 0, 0,0,,
  2160.9 2160.92 2196.55 2213.08 2220.32 2239.85 2244.08 2255.64 2255.96 2283.73
 2289.73 2290.36 2347.26 2347.33 2349.08 2362.88 2377.93 2387.59 2407.52 2416.38
 2430.69 2431.43 2439.57 2446.49 2459.85 2461.54 2463.53 2475.56 2476.59 2487.69
 2491.64 2496.24 2506.68 2512.56 2521.73 2529.57 2536.36 2551.82 2572.98 2579.95
 2581.91 2583.72 2611.26    2612 2613.32 2630.32 2635.65    2645
   69.28   69.28   69.59   69.55   69.55   69.32   69.24   68.98   68.99   69.16
   69.05   69.04   70.43   70.97      71   70.99   70.99   70.99   69.09   69.17
   69.21   69.21   69.15    69.1   69.26   69.29   69.29   69.18   69.17   69.46
   69.42   69.48   69.52   69.52   69.43   69.35    69.4   69.35   69.74   69.91
   69.91   69.88      70      70      70      70      70    69.8
                                                                                
                   70.03   70.57    70.6   70.59   70.59   70.59
                                                                                
                                                                                
                                                                
 2056.04 2088.64 2092.99 2095.39 2098.74 2111.18 2127.27 2147.23 2174.35 2174.37
    2210 2226.53 2233.77  2253.3 2257.53 2269.09 2269.41 2297.18 2303.18 2303.81
 2360.71 2360.78 2362.53 2376.33 2391.38 2401.04 2420.97 2429.83 2444.14 2444.88
 2453.02 2459.94  2473.3 2474.99 2476.98 2489.01 2490.04 2501.14 2505.09 2509.69
 2520.13 2526.01 2535.18 2543.02 2549.81 2565.27 2586.43  2593.4 2595.36 2597.17
 2624.71 2625.45 2626.77 2643.77  2649.1    2663
   70.09   69.63    69.5   69.46   69.49   69.29   69.34   69.41   69.28   69.28
   69.59   69.55   69.55   69.32   69.24   68.98   68.99   69.16   69.05   69.04
   70.43   70.97      71   70.99   70.99   70.99   69.09   69.17   69.21   69.21
   69.15    69.1   69.26   69.29   69.29   69.18   69.17   69.46   69.42   69.48
   69.52   69.52   69.43   69.35    69.4   69.35   69.74   69.91   69.91   69.88
      70      70      70      70      70      70
                                                                                
                                                                                
   70.03   70.57    70.6   70.59   70.59   70.59
                                                                                
                                                                                
                                                
BR Coef=-1 , 0 , 0 ,, 0 ,,,.8,-1,,0,
WSPro=,,,, 1 ,,,, 0 ,,,, 0 ,,,,-1 ,-1 ,-1 , 0 , 0 , 0 , 0 , 0
BC Design=,, 0 ,, 0 ,,,,,,
BC HTab HWMax=72.83

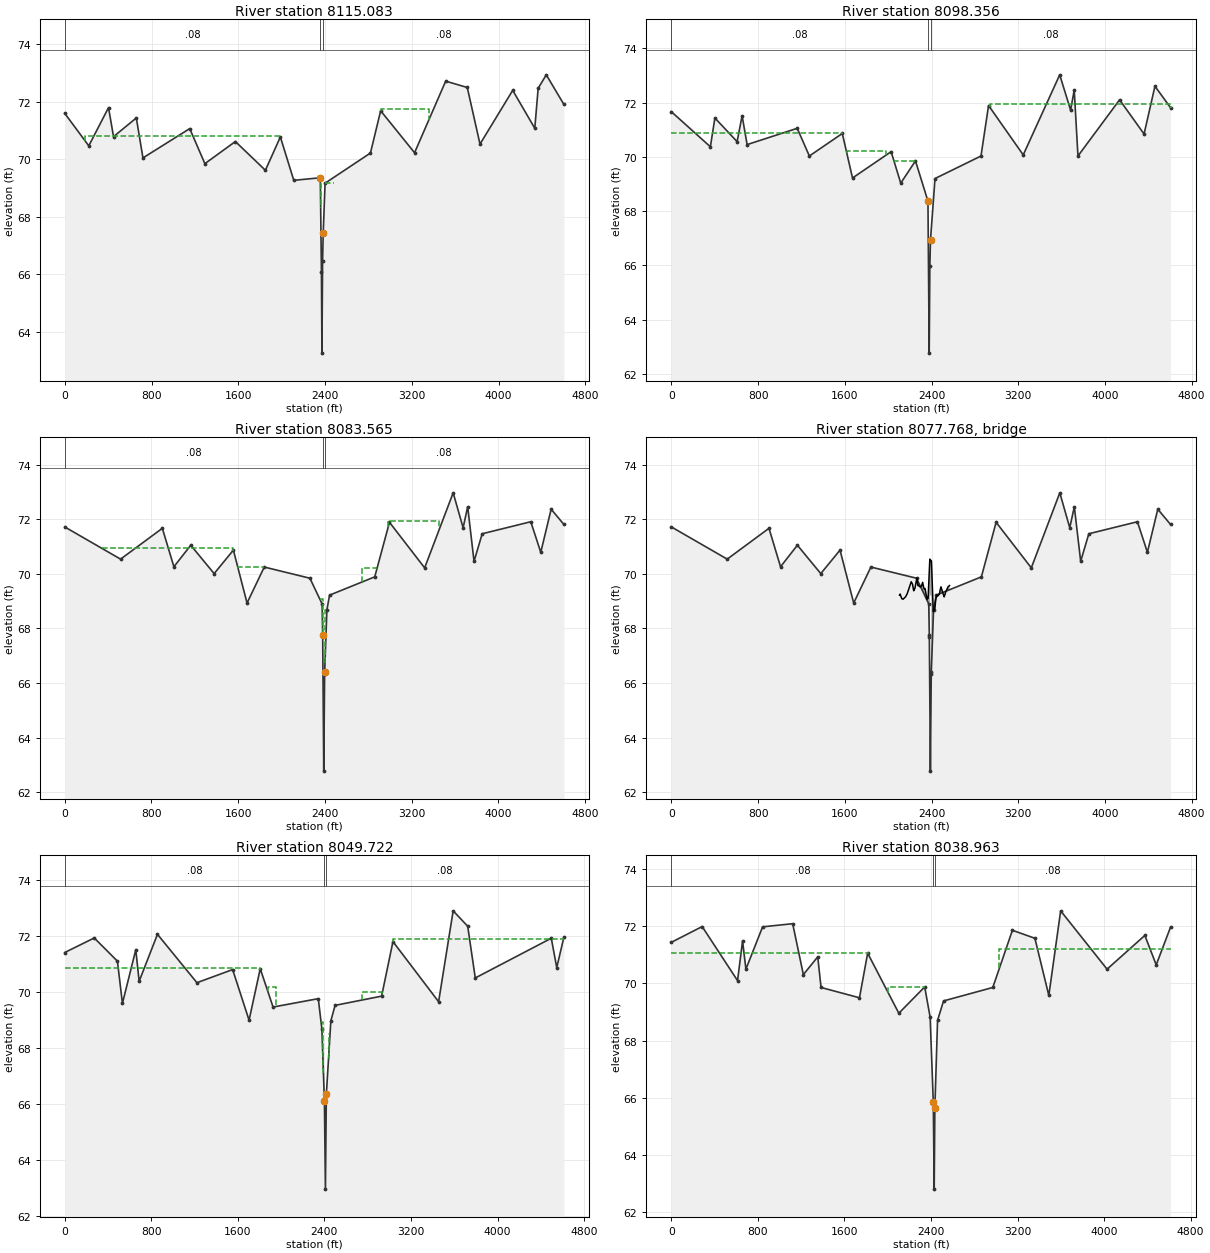
Type RM Length L Ch R = 1 ,8115.083,15.01,16.73,16.68
BEGIN DESCRIPTION:
Stations 2355.84 - 2400.17 developed from survey information (copied from cross-section 8098.36) , and the remainder developed from LiDAR. The elevations of the copied surveyed portion adjusted such that slope is consistent with closest surveyed data.
Blocked obstruction in the far overbank at basin divide.
END DESCRIPTION:
XS GIS Cut Line= 6
     3075511.824    13847427.749     3075000.744    13845191.979
     3074981.351    13845151.537     3074955.219    13845098.162
     3074643.621    13844574.979     3073932.431    13843146.739
#Sta/Elev= 30
       0   71.59  221.54   70.46   403.6   71.79  449.76   70.78  659.88   71.43
  720.97   70.04 1152.33   71.06 1291.96   69.84    1573   70.61 1849.97   69.61
 1987.89   70.77 2111.55   69.26 2356.09   69.35 2366.68   66.06 2371.15   63.25
 2377.16   66.46 2382.87    67.4 2383.15   67.43 2400.17   69.16 2818.43   70.21
 2912.67   71.68 3225.26   70.22 3512.11   72.71 3711.21   72.49 3828.51   70.52
 4130.13   72.39 4333.65   71.07 4364.72   72.46 4439.51   72.93 4602.18    71.9
#Mann= 3 ,-1 , 0
       0     .08       0 2356.09     .06       0 2382.87     .08       0
#XS Ineff= 4 ,-1
  187.71 1985.21    70.8 2354.98  2359.5   69.38 2401.36 2480.31   69.17
  2912.4 3356.09   71.73
Permanent Ineff=
       F       F       F       F
#Block Obstruct= 2 , 0
                         3469.85           72.98
Bank Sta=2356.09,2383.15
XS Rating Curve= 0
Exp/Cntr=.5,.3

Type RM Length L Ch R = 1 ,8098.356,15.19,14.79,14.62
BEGIN DESCRIPTION:
Stations 2363.42 - 2407.77 developed from survey information, and the remainder developed from LiDAR
Blocked obstruction in the far overbank at basin divide.
END DESCRIPTION:
XS GIS Cut Line= 6
     3075551.613    13847429.565     3075036.107    13845232.425
     3074997.319    13845151.537     3074960.306    13845074.537
     3074661.526       13844571.     3073956.441    13843147.986
#Sta/Elev= 30
       0   71.66  359.78   70.37  401.34   71.43  606.29   70.56  652.52   71.51
  698.74   70.45 1160.96   71.05 1273.04   70.03 1576.96   70.86 1671.09   69.22
 2027.43   70.19 2116.21   69.03 2252.06   69.85 2367.03   68.37 2367.36   68.32
 2378.73   62.77 2384.74   65.98 2390.75   66.95 2432.39    69.2 2856.64   70.03
 2926.41   71.89 3246.27   70.07 3582.94   73.02 3683.39   71.72 3716.87   72.46
 3751.24   70.03 4135.38    72.1 4361.19   70.84 4461.57    72.6 4605.57   71.81
#Mann= 3 ,-1 , 0
       0     .08       0 2367.36     .06       0 2390.75     .08       0
#XS Ineff= 4 ,-1
       0 1570.72   70.87 1618.41 1976.14   70.21 2055.92 2253.29   69.85
 2935.86 4621.71   71.93
Permanent Ineff=
       F       F       F       F
#Block Obstruct= 2 , 0
                         3515.36           73.05
Bank Sta=2367.03,2390.75
XS Rating Curve= 0
Exp/Cntr=.5,.3

Type RM Length L Ch R = 1 ,8083.565,33.03,33.84,33.1
BEGIN DESCRIPTION:
Stations 2374.24 - 2418.59 developed from survey information (copied from cross-section 8098.36) , and the remainder developed from LiDAR.
Blocked obstruction in the far overbank at basin divide.
END DESCRIPTION:
XS GIS Cut Line= 6
     3075570.768    13847430.439     3075048.051    13845223.625
     3075009.262    13845142.737      3074972.25    13845065.737
     3074671.474    13844555.084     3073974.155    13843148.906
#Sta/Elev= 30
       0   71.72  515.01   70.54  900.38   71.67 1006.98   70.26 1162.44   71.05
 1378.25   70.01 1555.79   70.87 1681.87   68.93  1840.7   70.25 2261.79   69.84
 2374.24    68.9 2379.62   67.76 2379.85   67.67 2389.55   62.77 2397.54   66.33
 2397.86   66.39 2418.59   68.68 2443.02   69.22 2859.99   69.89 2995.96   71.89
 3320.48   70.22 3583.48   72.97 3675.38   71.69 3717.43   72.46 3776.11   70.46
 3851.37   71.47 4299.62   71.91 4391.71   70.79 4487.61   72.37 4605.25   71.81
#Mann= 3 ,-1 , 0
       0     .08       0 2379.85     .06       0 2397.54     .08       0
#XS Ineff= 6 ,-1
   341.3  1552.9   70.93 1598.24 1840.19   70.25 2354.35 2379.95   69.09
 2400.88 2421.82   68.68 2738.54 2881.59   70.22 2984.13  3456.2   71.93
Permanent Ineff=
       F       F       F       F       F       F
#Block Obstruct= 2 , 0
                         3526.73           73.02
Bank Sta=2379.62,2397.86
XS Rating Curve= 0
Exp/Cntr=.5,.3

Type RM Length L Ch R = 3 ,8077.768,,,
BEGIN DESCRIPTION:
Structure 32 - unnamed wooden bridge
END DESCRIPTION:
Bridge Culvert--1,0,-1,-1, 0
Deck Dist Width WeirC Skew NumUp NumDn MinLoCord MaxHiCord MaxSubmerge Is_Ogee
4,14,2.6,0, 53, 49, , , .95, 0, 0,0,,
 2104.74 2110.81 2114.35  2125.7 2136.99 2160.69 2175.25 2196.73 2205.84 2212.55
 2224.81 2235.16 2241.33 2247.19 2264.51 2267.62 2274.42 2280.31 2291.05 2298.06
 2308.79 2318.19 2324.32 2331.61 2340.96 2347.77 2357.33 2357.56 2368.45 2384.26
 2384.65 2397.98 2399.29 2416.23 2431.22  2437.7 2440.81 2442.77 2451.73 2459.73
 2471.09 2484.38 2486.13 2487.63  2506.8 2515.54 2516.23 2517.03 2531.27 2543.45
 2547.93 2553.66    2566
   69.22   69.26   69.21   69.09   69.07   69.16   69.27   69.52   69.63   69.71
   69.62   69.38   69.42   69.48   69.84   69.75   69.57   69.58   69.53   69.52
   69.57   69.69   69.56   69.45   69.46   69.29   69.11   69.07    69.1   70.54
   70.54   70.47   70.47   68.61   68.73   69.01   69.09   69.13   69.23    69.2
   69.25   69.49   69.52   69.52   69.27   69.17   69.16   69.16   69.34   69.45
   69.48   69.53   69.57
                                                                                
                                                                                
                                                                           69.24
   69.24   69.17
                                                                                
                        
    2123 2127.73  2133.8 2137.34 2148.69 2159.98 2183.68 2198.24 2219.72 2228.83
 2235.54  2247.8 2258.15 2264.32 2270.18  2287.5 2290.61 2297.41  2303.3 2314.04
 2321.05 2331.78 2341.18 2347.31  2354.6 2363.95 2370.76 2380.32 2380.55 2391.44
 2407.25 2407.64 2420.97 2422.28 2439.22 2454.21 2460.69  2463.8 2465.76 2474.72
 2482.72 2494.08 2507.37 2509.12 2510.62 2529.79 2538.53 2539.22 2540.02
   69.22   69.22   69.26   69.21   69.09   69.07   69.16   69.27   69.52   69.63
   69.71   69.62   69.38   69.42   69.48   69.84   69.75   69.57   69.58   69.53
   69.52   69.57   69.69   69.56   69.45   69.46   69.29   69.11   69.07    69.1
   70.54   70.54   70.47   70.47   68.61   68.73   69.01   69.09   69.13   69.23
    69.2   69.25   69.49   69.52   69.52   69.27   69.17   69.16   69.16
                                                                                
                                                                                
                                                                                
   69.24   69.24   69.17
                                                                        
BR Coef=-1 , 0 , 0 ,, 0 ,,,.8,-1,,0,
WSPro=,,,, 1 ,,,, 0 ,,,, 0 ,,,,-1 ,-1 ,-1 , 0 , 0 , 0 , 0 , 0
BC Design=,, 0 ,, 0 ,,,,,,
BC HTab HWMax=72.97

Type RM Length L Ch R = 1 ,8049.722,10.91,10.76,10.19
BEGIN DESCRIPTION:
Stations 2380.09 - 2422.98 developed from survey information (copied from cross-section 8027.74) , and the remainder developed from LiDAR. The elevation of survey points adjusted to match the overall stream slope of approx. .0064 ft/ft.
Blocked obstruction in the far overbank at basin divide.
END DESCRIPTION:
XS GIS Cut Line= 6
     3075615.912      13847432.5     3075080.227    13845218.952
     3075009.407    13845069.551     3074985.381     13845019.21
     3074681.421    13844507.337     3073997.513     13843150.12
#Sta/Elev= 30
       0   71.41  272.69   71.93  486.86    71.1  533.16   69.59  656.62   71.51
  687.49   70.38  856.95   72.06 1221.78   70.33 1551.74    70.8 1703.63   68.99
 1806.88   70.83 1925.33   69.46 2343.46   69.76 2376.66   68.67 2399.94   66.11
 2400.08   66.09 2409.38   62.95 2417.79   66.29 2418.07   66.35 2459.68   68.97
 2498.82   69.52 2928.77   69.85 3033.44    71.8 3455.61   69.65 3589.98    72.9
 3724.36   72.35 3794.37    70.5 4497.06   71.92  4547.4   70.87 4613.67   71.96
#Mann= 3 ,-1 , 0
       0     .08       0 2399.94     .06       0 2417.79     .08       0
#XS Ineff= 6 ,-1
       0 1804.57   70.85 1876.79 1950.15   70.16 2370.48 2391.58   68.93
    2438 2452.06    68.5 2743.17  2932.5   70.01 3033.14 4622.31   71.89
Permanent Ineff=
       F       F       F       F       F       F
#Block Obstruct= 2 , 0
                         3577.93           72.96
Bank Sta=2400.08,2418.07
XS Rating Curve= 0
Exp/Cntr=.5,.3

Type RM Length L Ch R = 1 ,8038.963,11.39,11.22,10.68
BEGIN DESCRIPTION:
Stations 2400.11 - 2443 developed from survey information, and the remainder developed from LiDAR
Blocked obstruction in the far overbank at basin divide.
Section data copied from cross-section 8027.744
END DESCRIPTION:
XS GIS Cut Line= 6
     3075631.132    13847442.298     3075086.919    13845210.939
       3075016.1    13845061.538     3074983.609    13844992.997
     3074688.469    13844494.242 3074010.403424513843159.9447058
#Sta/Elev= 30
       0   71.44  284.48   71.99  611.63    70.1  657.95   71.49  688.82    70.5
  843.22   71.98 1121.14   72.09 1219.94   70.31 1352.73   70.93 1383.61   69.86
 1738.72    69.5 1814.29   71.06 2102.39   68.96 2341.61   69.88  2391.9   68.82
 2421.07   65.85 2421.17   65.84 2429.39   62.81 2435.56   65.65 2460.38   68.71
 2515.77   69.39 2971.02   69.86 3152.44   71.86 3360.21   71.58 3488.95   69.58
 3598.37   72.54 4027.37    70.5 4376.56   71.68 4481.67   70.65  4614.2   71.97
#Mann= 3 ,-1 , 0
       0     .08       0 2421.17     .06       0 2435.56     .08       0
#XS Ineff= 3 ,-1
       0  1817.3   71.06  2006.1 2341.76   69.88 3032.15 4628.43   71.22
Permanent Ineff=
       F       F       F
#Block Obstruct= 2 , 0
       0                 3606.37       0   72.56
Bank Sta=2421.07,2435.56
XS Rating Curve= 0
Exp/Cntr=.5,.3