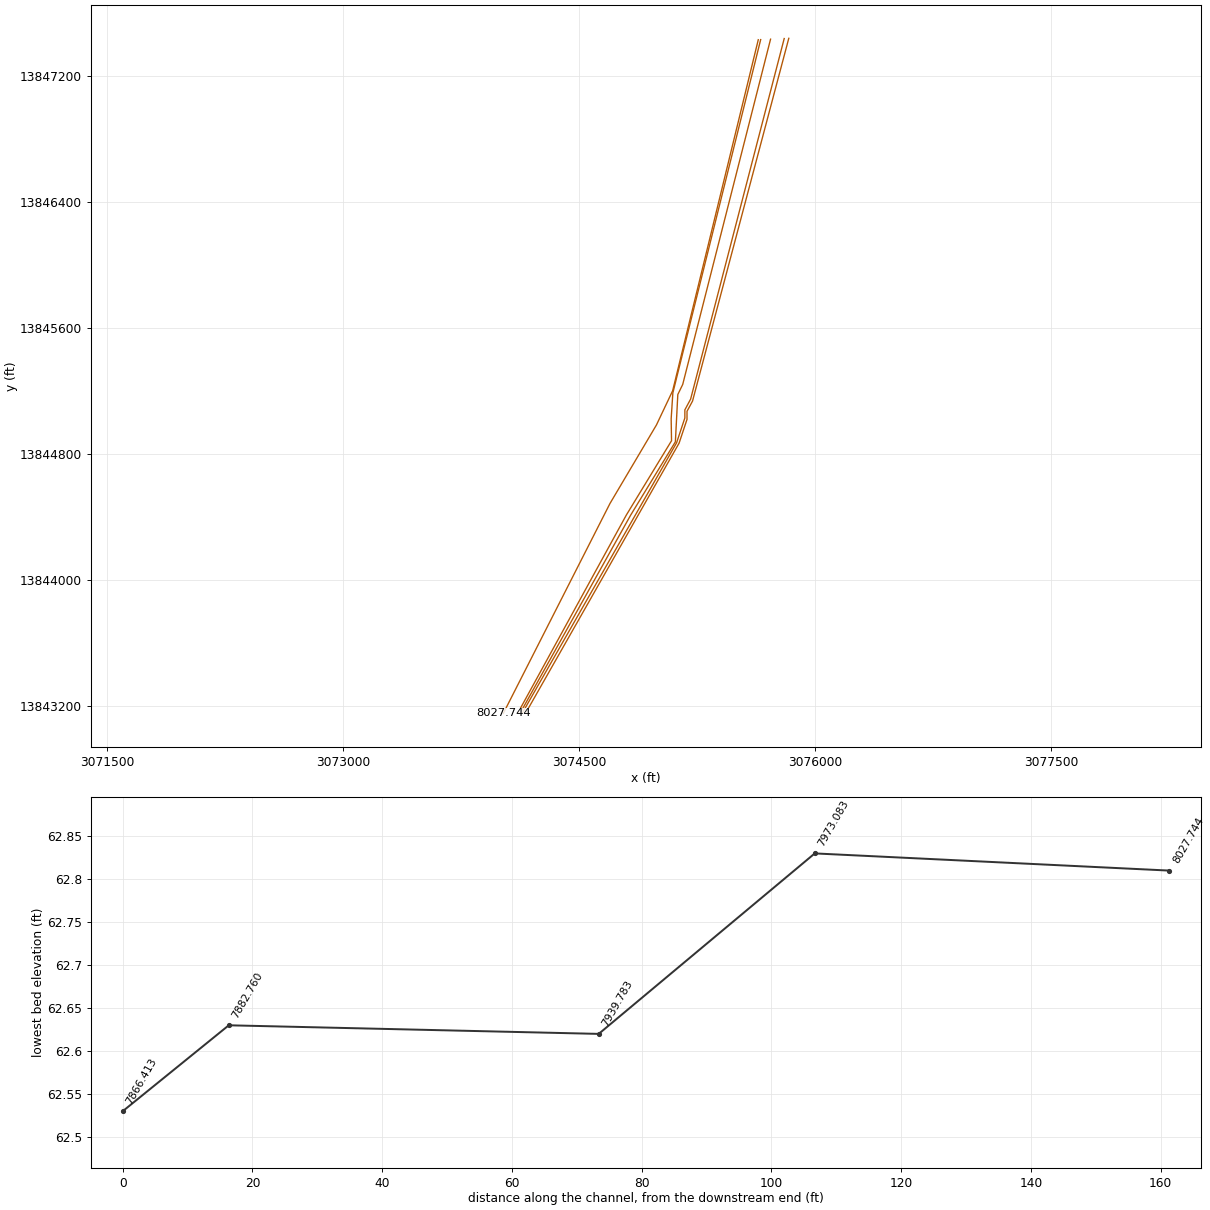
HEC-RAS study W141-00-00.prj: W141-00-00

--- W141-00-00.g01 (geometry) --- (continued)

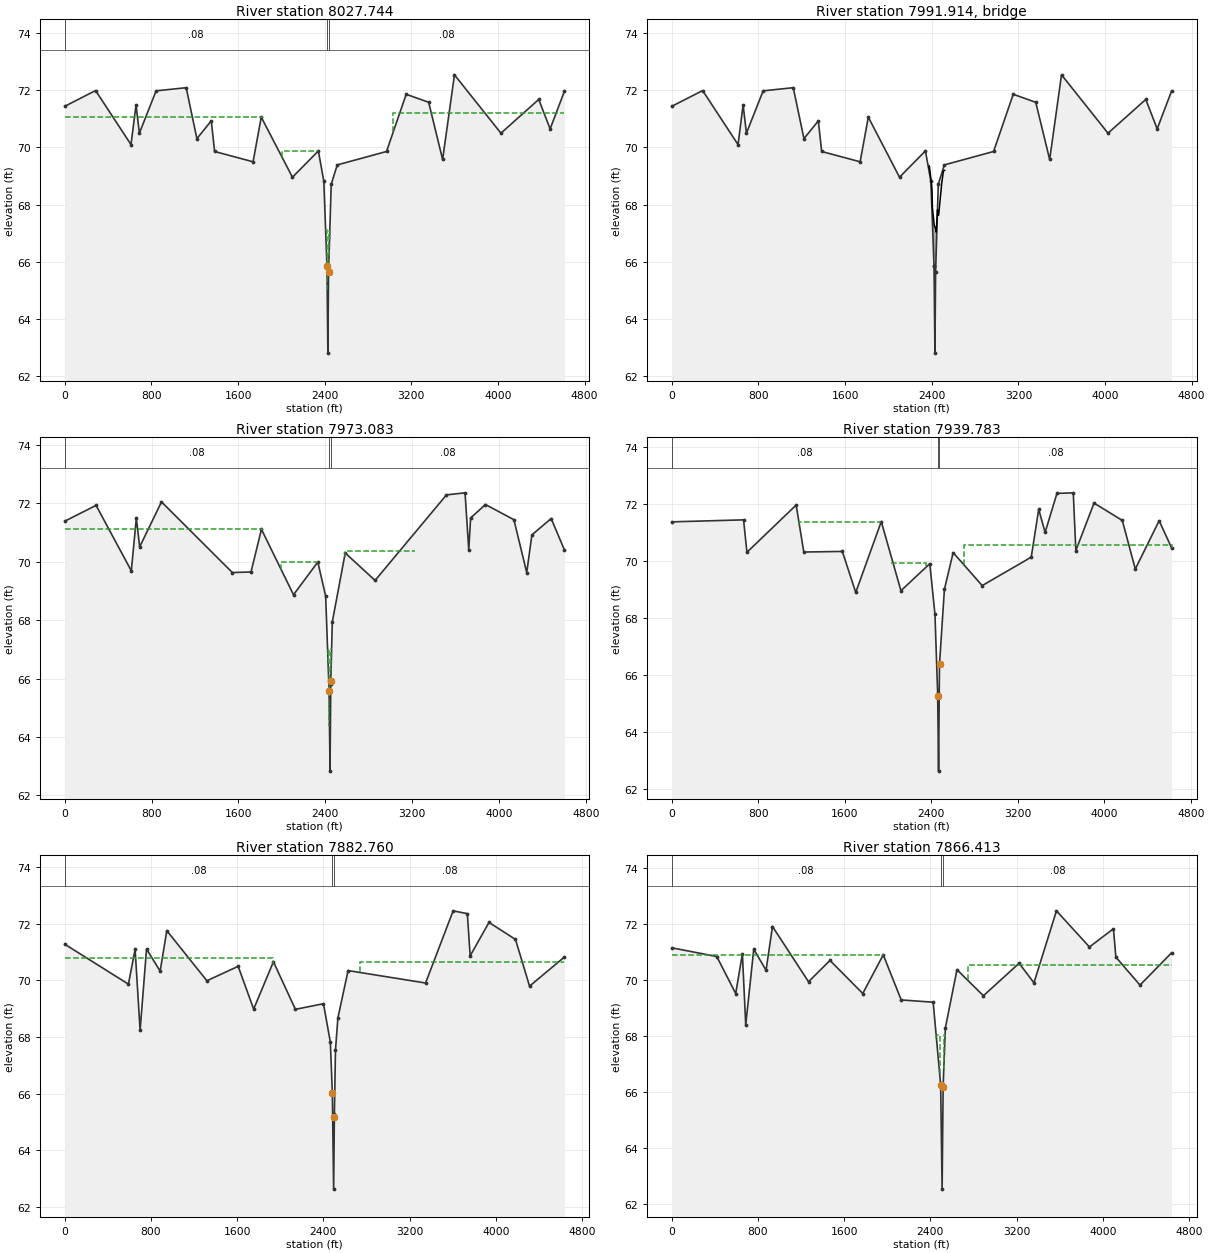
Type RM Length L Ch R = 1 ,8027.744,47.37,54.66,61.15
BEGIN DESCRIPTION:
Stations 2400.11 - 2443 developed from survey information, and the remainder developed from LiDAR
Blocked obstruction in the far overbank at basin divide.
END DESCRIPTION:
XS GIS Cut Line= 6
      3075638.01    13847433.509     3075466.836    13846731.666
     3075093.798     13845202.15     3074990.488    13844984.208
     3074695.347    13844485.453     3074017.278    13843151.146
#Sta/Elev= 30
       0   71.44  284.48   71.99  611.63    70.1  657.95   71.49  688.82    70.5
  843.22   71.98 1121.14   72.09 1219.94   70.31 1352.73   70.93 1383.61   69.86
 1738.72    69.5 1814.29   71.06 2102.39   68.96 2341.61   69.88  2391.9   68.82
 2421.07   65.85 2421.17   65.84 2429.39   62.81 2435.56   65.65 2460.38   68.71
 2515.77   69.39 2971.02   69.86 3152.44   71.86 3360.21   71.58 3488.95   69.58
 3598.37   72.54 4027.37    70.5 4376.56   71.68 4481.67   70.65  4614.2   71.97
#Mann= 3 ,-1 , 0
       0     .08       0 2421.17     .06       0 2435.56     .08       0
#XS Ineff= 5 ,-1
       0  1817.3   71.06  2006.1 2341.76   69.88 2408.99 2423.37    67.1
 2435.58 2444.88   67.08 3032.15 4628.43   71.22
Permanent Ineff=
       F       F       F       F       F
#Block Obstruct= 2 , 0
                         3606.37           72.56
Bank Sta=2421.07,2435.56
XS Rating Curve= 0
Exp/Cntr=.5,.3

Type RM Length L Ch R = 3 ,7991.914,,,
BEGIN DESCRIPTION:
Structure 31 - unnamed concrete bridge
END DESCRIPTION:
Bridge Culvert--1,0,-1,-1, 0
Deck Dist Width WeirC Skew NumUp NumDn MinLoCord MaxHiCord MaxSubmerge Is_Ogee
29,11.3,2.6,0, 20, 32, , , .95, 0, 0,0,,
 2376.75 2377.81 2398.06 2402.79 2405.94 2423.61 2424.69 2435.09 2439.49 2440.79
    2453 2459.92 2462.83 2465.47 2491.52 2492.21 2492.87  2507.7 2508.39 2518.69
   69.29   69.36    68.7   68.51   67.91   67.26   67.26   67.16   67.12   67.04
   67.82   67.65   67.63    67.7   68.72   68.76   68.77   69.17   69.18    69.2
                                           66.16   66.16   66.06
                                                                                
    2383 2392.11 2393.17 2413.42 2418.15  2421.3 2438.97 2440.05 2450.45 2454.85
 2456.15 2468.36 2475.28 2478.19 2480.83 2506.88 2507.57 2508.23 2523.06 2523.75
 2534.05 2553.28 2566.68  2568.3 2570.09 2583.32 2585.89 2598.34 2609.61 2611.44
 2617.49 2628.21
    69.4   69.39   69.36    68.7   68.51   67.91   67.26   67.26   67.16   67.12
   67.04   67.82   67.65   67.63    67.7   68.72   68.76   68.77   69.17   69.18
    69.2   69.25   69.43   69.44   69.48   69.91   70.02   70.36   70.32   70.32
   70.27    70.1
                                                   66.16   66.16   66.06
                                                                                
                                                                                
                
BR Coef=-1 , 0 , 0 ,, 0 ,,,.8,-1,,0,
WSPro=,,,, 1 ,,,, 0 ,,,, 0 ,,,,-1 ,-1 ,-1 , 0 , 0 , 0 , 0 , 0
BC Design=,, 0 ,, 0 ,,,,,,
BC HTab HWMax=72.54

Type RM Length L Ch R = 1 ,7973.083,33.45,33.3,33.61
BEGIN DESCRIPTION:
Stations 2432.23 - 2464.61 developed from survey information (copied from cross-section 7939.78) , and the remainder developed from LiDAR. The elevation of survey points adjusted to match the overall stream slope of approx. .0064 ft/ft.
Blocked obstruction in the far overbank at basin divide.
END DESCRIPTION:
XS GIS Cut Line= 6
     3075653.292    13847434.206     3075094.982    13845188.393
     3075084.275    13845023.906     3075086.595    13844884.287
       3074798.8    13844411.047     3074111.009    13843156.016
#Sta/Elev= 30
       0   71.39  288.38   71.93  612.91   69.69  659.27   71.49  690.18   70.51
  891.08   72.05 1544.02   69.63 1715.84   69.65 1811.92   71.11 2107.26   68.87
 2331.41   69.99 2403.52   68.82  2435.1   65.59 2435.19   65.56 2443.72   62.83
 2450.52    65.8 2450.75   65.92 2464.61   67.94  2583.7    70.3 2858.63   69.36
 3516.68   72.29 3687.73   72.36 3721.94    70.4 3739.05    71.5 3875.88   71.96
 4137.79   71.44 4255.89   69.63 4303.51   70.92 4481.12   71.48 4603.73    70.4
#Mann= 3 ,-1 , 0
       0     .08       0 2435.19     .06       0 2450.52     .08       0
#XS Ineff= 5 ,-1
  -12.44 1814.51   71.12 1994.95 2329.14      70 2425.85 2438.86   67.02
 2450.65 2459.76   67.02  2577.3 3224.98   70.36
Permanent Ineff=
       F       F       F       F       F
#Block Obstruct= 2 , 0
                         3696.25           72.39
Bank Sta=2435.1,2450.75
XS Rating Curve= 0
Exp/Cntr=.5,.3

Type RM Length L Ch R = 1 ,7939.783,53.65,57.02,54.19
BEGIN DESCRIPTION:
Stations 2454.61 - 2486.99 developed from survey information, and the remainder developed from LiDAR
Blocked obstruction in the far overbank at basin divide.
END DESCRIPTION:
XS GIS Cut Line= 6
     3075716.104    13847437.073     3075157.645    13845242.106
     3075126.485    13845177.892     3075111.075    13844877.375
     3074827.448    13844412.638     3074126.511    13843156.821
#Sta/Elev= 30
       0   71.38  663.25   71.45  694.21   70.31 1149.38   71.97 1220.13   70.32
 1576.45   70.34 1700.27    68.9 1936.29   71.39 2118.17   68.96 2384.97   69.91
 2432.71   68.13 2457.57   65.36 2457.89   65.25  2466.1   62.62 2474.38   66.34
  2474.8   66.39 2520.08   69.01 2600.95    70.3 2869.33   69.14 3322.98   70.14
 3391.77   71.82 3451.12   71.01 3560.45   72.38 3711.54    72.4 3735.26   70.37
 3903.26   72.04 4164.72   71.43 4284.83   69.72 4505.33   71.42 4619.92   70.47
#Mann= 3 ,-1 , 0
       0     .08       0 2457.57     .06       0 2474.38     .08       0
#XS Ineff= 3 ,-1
 1179.43 1938.07   71.39 2030.28 2347.48   69.93 2701.91 4636.21   70.56
Permanent Ineff=
       F       F       F
#Block Obstruct= 2 , 0
                         3697.38           72.41
Bank Sta=2457.89,2474.8
XS Rating Curve= 0
Exp/Cntr=.3,.1

Type RM Length L Ch R = 1 ,7882.760,15.44,16.35,17.14
BEGIN DESCRIPTION:
Stations 2464.91 - 2512.48 developed from survey information (copied from cross-section 7866.41) , and the remainder developed from LiDAR. The elevation of survey points adjusted to match the overall stream slope of approx. .0064 ft/ft.
Blocked obstruction in the far overbank at basin divide.
END DESCRIPTION:
XS GIS Cut Line= 6
     3075802.857    13847441.033     3075207.945    13845148.955
      3075171.34    13845080.473     3075171.326    13845029.133
     3075118.587    13844870.915     3074140.395    13843157.542
#Sta/Elev= 30
       0   71.28  590.68   69.87  652.67    71.1  699.16   68.24  758.78   71.11
  885.12   70.33  947.03   71.76 1319.04   69.99 1609.24    70.5 1752.95   68.99
 1936.62   70.66 2140.54   68.98 2400.95   69.18 2464.91   67.82 2483.27   66.02
 2483.55   65.95  2495.4   62.63    2502   65.17 2502.24   65.27 2512.48   67.54
 2534.62   68.67 2629.39   70.35 3348.61   69.91 3604.53   72.46 3736.25   72.36
 3762.49   70.87 3937.09   72.05 4183.16   71.45 4313.56    69.8 4637.81   70.83
#Mann= 3 ,-1 , 0
       0     .08       0 2483.55     .06       0 2502.24     .08       0
#XS Ineff= 2 , 0
         1928.33   70.78 2736.06           70.66
Permanent Ineff=
       F       F
#Block Obstruct= 2 , 0
                         3614.33           72.46
Bank Sta=2483.27,2502
XS Rating Curve= 0
Exp/Cntr=.5,.3

Type RM Length L Ch R = 1 ,7866.413,49.22,36.17,32.44
BEGIN DESCRIPTION:
Stations 2478.45 - 2526.05 developed from survey information, and the remainder developed from LiDAR
Blocked obstruction in the far overbank at basin divide.
END DESCRIPTION:
XS GIS Cut Line= 6
     3075831.945     13847442.36     3075219.988    13845136.003
     3075185.072    13845071.588     3075185.059    13845020.248
     3075134.596     13844868.86     3074162.415    13843158.686
#Sta/Elev= 30
       0   71.14  417.06   70.83  592.89   69.51  654.97   70.92     686   68.39
  760.47   71.09  874.61   70.34  934.31    71.9  1268.8   69.93 1468.14   70.69
 1772.34   69.51 1962.42   70.89 2129.27   69.28 2425.91    69.2 2495.42   66.25
 2495.61   66.21 2508.94   62.53 2518.34   66.17 2518.66   66.22 2538.99   68.28
 2646.88   70.36 2892.14   69.43 3224.05   70.59 3361.43   69.89 3570.35   72.46
 3876.59   71.17 4099.31   71.82 4121.69   70.81 4345.81   69.81 4638.59   70.96
#Mann= 3 ,-1 , 0
       0     .08       0 2495.61     .06       0 2518.66     .08       0
#XS Ineff= 4 ,-1
   -4.76 1957.56    70.9 2456.02 2487.19   68.04 2524.58 2534.97   68.04
 2747.79 4708.04   70.53
Permanent Ineff=
       F       F       F       F
#Block Obstruct= 2 , 0
                         3593.86           72.49
Bank Sta=2495.42,2518.34
XS Rating Curve= 0
Exp/Cntr=.5,.3