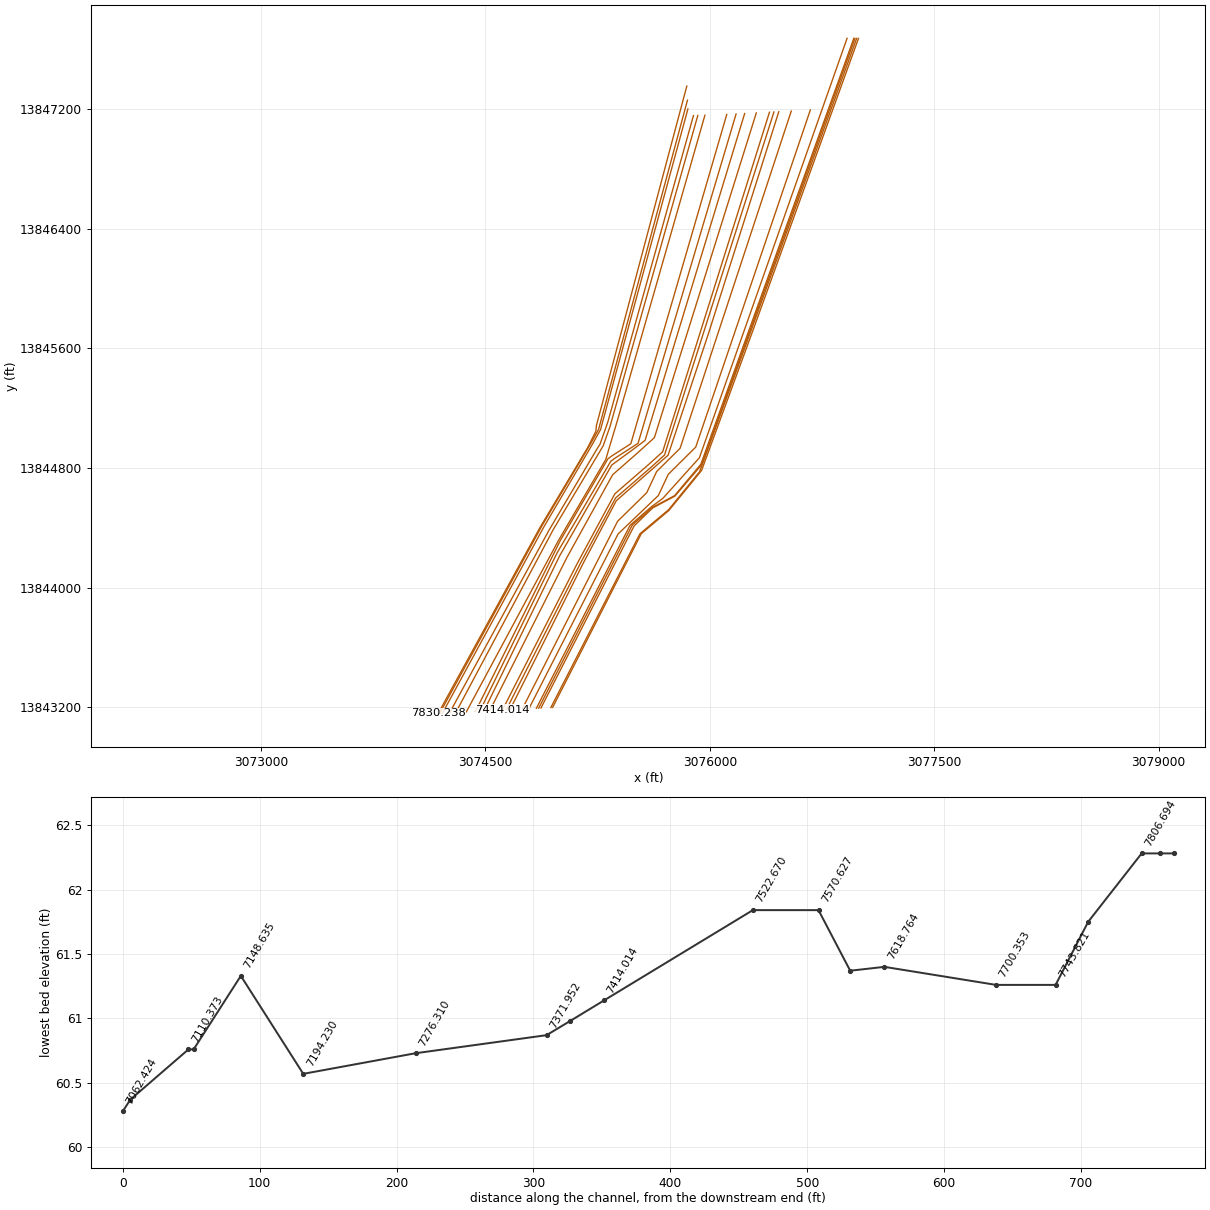
HEC-RAS study W141-00-00.prj: W141-00-00

--- W141-00-00.g01 (geometry) --- (continued)

Type RM Length L Ch R = 3 ,7845.009,,,
BEGIN DESCRIPTION:
Structure 29 - unnamed metal bridge
END DESCRIPTION:
Bridge Culvert--1,0,-1,-1, 0
Deck Dist Width WeirC Skew NumUp NumDn MinLoCord MaxHiCord MaxSubmerge Is_Ogee
10,14,2.6,0, 66, 67, , , .95, 0, 0,0,,
 2007.16 2018.18 2026.87 2037.54 2046.32 2050.25 2052.64 2066.29 2072.45 2082.32
 2083.35 2084.09 2085.74 2130.43 2131.18 2146.47 2155.75  2162.5 2165.55 2173.62
  2173.8 2178.62 2182.37 2194.94  2197.9 2211.27 2211.39 2243.91  2249.7 2260.24
 2268.16 2276.56 2279.92 2292.88 2298.69 2308.07 2335.86 2348.44  2374.5 2390.94
 2400.66 2413.11 2422.45 2426.66 2434.25 2451.96 2453.54 2454.07  2465.4 2469.88
 2472.19 2484.18  2495.9 2498.84 2515.99 2525.44 2540.88 2546.78  2548.4 2548.95
 2553.38 2580.59 2583.94 2593.92 2596.05 2596.73
   69.86   69.74   69.65   69.58   69.61    69.6   69.64   69.67   69.57   69.51
    69.5    69.5   69.52   69.04   69.05   69.05   68.86   68.75   68.72   68.68
   68.68   68.69   68.73   68.85    68.9   68.78   68.78   68.98   68.95   68.94
   69.08   69.27   69.29   69.36   69.35   69.23   69.06   69.08   69.17   69.18
   69.18   69.15   69.24   69.18   69.03   68.75   68.72    68.7    68.4      68
   68.82   70.02   70.52    70.5   70.43   69.66   68.73   68.96      69   69.01
   69.02   68.94   69.13   69.54   69.64    69.6
                                                                                
                                                                                
                                                                                
                                                                                
                                                                                
                            67.3   67.23
                                                
 1923.13 1934.15 1942.84 1953.51 1962.29 1966.22 1968.61 1982.26 1988.42 1998.29
 1999.32 2000.06 2001.71  2046.4 2047.15 2062.44 2071.72 2078.47 2081.52 2089.59
 2089.77 2094.59 2098.34 2110.91 2113.87 2127.24 2127.36 2159.88 2165.67 2176.21
 2184.13 2192.53 2195.89 2208.85 2214.66 2224.04 2251.83 2264.41 2290.47 2306.91
 2316.63 2329.08 2338.42 2342.63 2350.22 2367.93 2369.51 2370.04 2381.37 2385.85
 2388.16 2400.15 2411.87 2414.81 2431.96 2441.41 2456.85 2462.75 2464.37 2464.92
 2469.35 2496.56 2499.91 2509.89 2512.02  2512.7 2538.37
   69.86   69.74   69.65   69.58   69.61    69.6   69.64   69.67   69.57   69.51
    69.5    69.5   69.52   69.04   69.05   69.05   68.86   68.75   68.72   68.68
   68.68   68.69   68.73   68.85    68.9   68.78   68.78   68.98   68.95   68.94
   69.08   69.27   69.29   69.36   69.35   69.23   69.06   69.08   69.17   69.18
   69.18   69.15   69.24   69.18   69.03   68.75   68.72    68.7    68.4      68
   68.82   70.02   70.52    70.5   70.43   69.66   68.73   68.96      69   69.01
   69.02   68.94   69.13   69.54   69.64   69.65   70.06
                                                                                
                                                                                
                                                                                
                                                                                
                                                                                
                            67.3   67.23
                                                        
BR Coef=-1 , 0 , 0 ,, 0 ,,,.8,-1,,0,
WSPro=,,,, 1 ,,,, 0 ,,,, 0 ,,,,-1 ,-1 ,-1 , 0 , 0 , 0 , 0 , 0
BC Design=,, 0 ,, 0 ,,,,,,
BC HTab HWMax=72.46

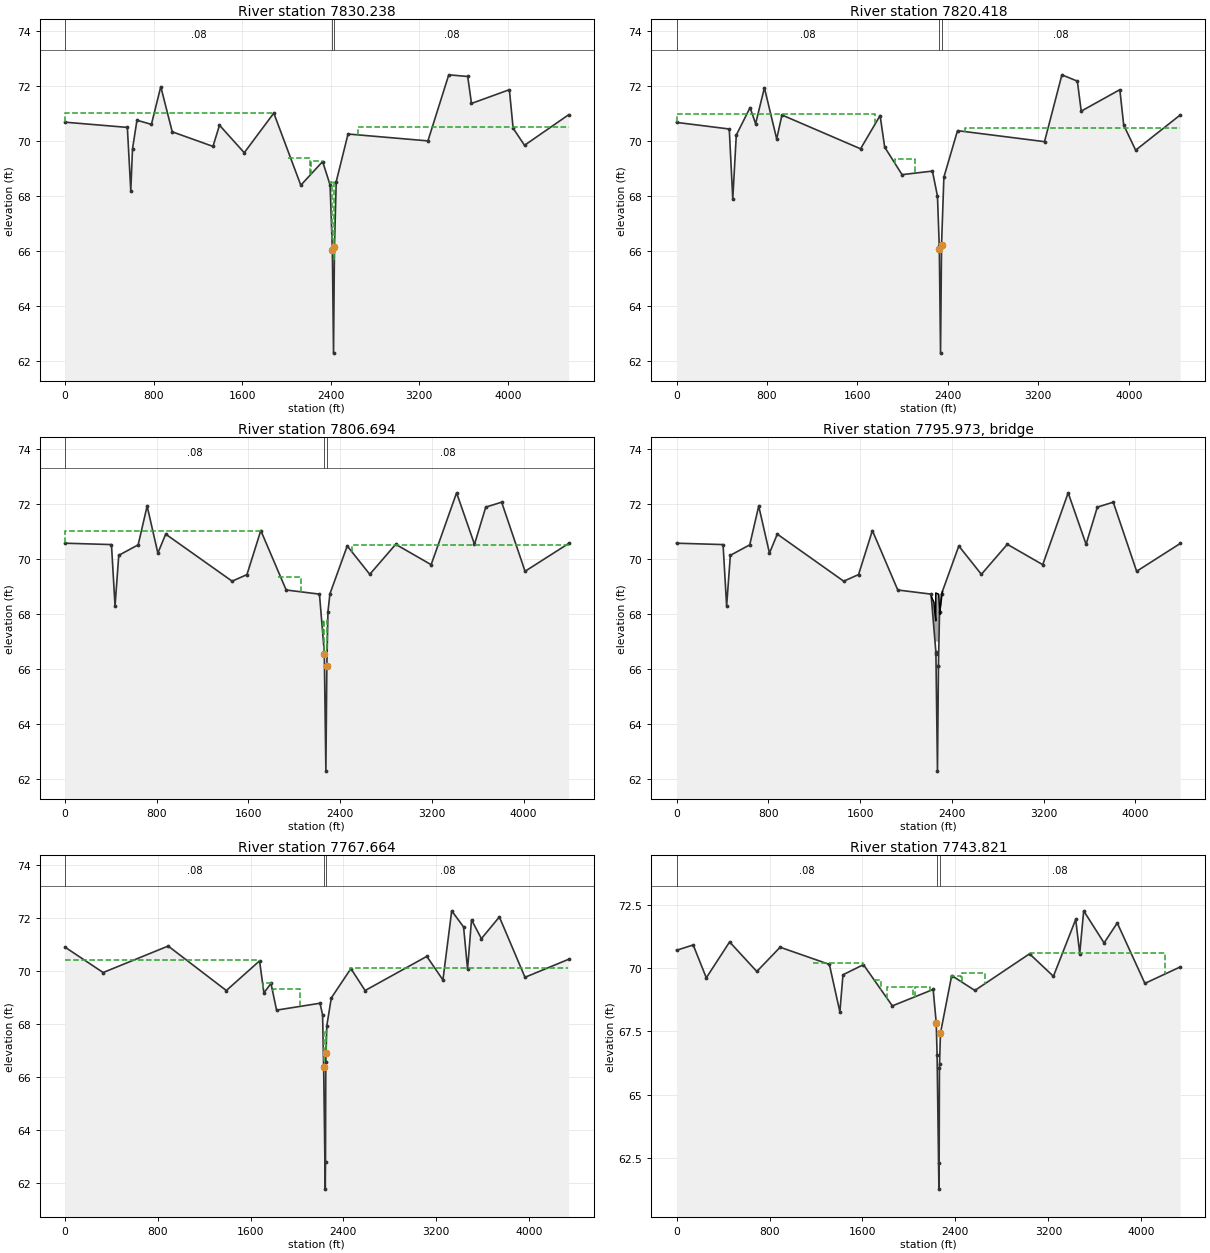
Type RM Length L Ch R = 1 ,7830.238,10.67,9.82,9.49
BEGIN DESCRIPTION:
Stations 2405.88 - 2438.64 developed from survey information (copied from cross-section 7820.42) , and the remainder developed from LiDAR.
Blocked obstruction in the far overbank at basin divide.
END DESCRIPTION:
XS GIS Cut Line= 6
     3075845.961    13847353.582     3075241.815    13845085.216
      3075237.85    13845045.812     3075184.336    13844938.408
     3074865.646     13844404.68     3074184.014    13843159.808
#Sta/Elev= 30
       0   70.67  563.26   70.48   594.3   68.18  609.82    69.7  649.93   70.74
  780.58   70.59  865.11   71.96  968.64   70.32 1336.38   69.79 1395.33   70.56
 1618.81   69.56 1885.66      71 2129.54   68.38 2326.52   69.24    2394   68.39
 2414.11   66.08 2414.34   66.04 2424.99   62.28 2433.53   66.13 2433.76   66.18
 2449.38   68.51 2555.99   70.24 3277.43   69.99 3465.55   72.39 3636.56   72.33
 3670.77   71.35  4012.8   71.85 4046.79   70.45 4149.61   69.83 4548.06   70.94
#Mann= 3 ,-1 , 0
       0     .08       0 2414.11     .06       0 2433.76     .08       0
#XS Ineff= 6 ,-1
       0 1887.23   70.99 2015.18 2208.44   69.38 2218.61 2325.41   69.25
 2388.25 2414.11    68.5 2432.52 2450.93    68.5 2650.08 4600.12    70.5
Permanent Ineff=
       F       F       F       F       F       F
#Block Obstruct= 2 , 0
                         3515.36           72.44
Bank Sta=2414.34,2433.53
XS Rating Curve= 0
Exp/Cntr=.5,.3

Type RM Length L Ch R = 1 ,7820.418,15.27,13.72,13.95
BEGIN DESCRIPTION:
Stations 2315.82 - 2348.59 developed from survey information, and the remainder developed from LiDAR
Blocked obstruction in the far overbank at basin divide.
END DESCRIPTION:
XS GIS Cut Line= 6
      3075850.45    13847259.299     3075255.653    13845056.917
     3075248.351    13845044.196     3075209.435    13844974.061
     3074876.787    13844412.638     3074194.074    13843160.331
#Sta/Elev= 30
       0   70.67  466.12   70.43   497.2   67.89  528.27   70.21  650.46   71.21
  699.18   70.62  776.87   71.93  885.63   70.07  932.24   70.94 1627.47   69.71
 1800.33   70.92  1840.9   69.77 1994.48   68.77 2263.04    68.9  2307.8   67.99
 2323.53   66.17 2324.07   66.08 2334.94   62.28 2343.94   66.23 2344.07   66.25
 2364.59   68.68 2485.11   70.37 3254.63   69.97 3408.39    72.4 3545.06   72.17
 3579.23   71.08 3920.92   71.86 3955.09   70.57 4060.82   69.66 4455.05   70.94
#Mann= 3 ,-1 , 0
       0     .08       0 2323.53     .06       0 2344.07     .08       0
#XS Ineff= 3 ,-1
   -3.14 1759.22   70.99 1932.78 2113.05   69.33 2552.11 4582.28   70.47
Permanent Ineff=
       F       F       F
#Block Obstruct= 2 , 0
                         3416.38           72.39
Bank Sta=2324.07,2343.94
XS Rating Curve= 0
Exp/Cntr=.5,.3

Type RM Length L Ch R = 1 ,7806.694,34.07,39.03,42.07
BEGIN DESCRIPTION:
Stations 2256.22 - 2288.99 developed from survey information (copied from cross-section 7820.42) , and the remainder developed from LiDAR.
Blocked obstruction in the far overbank at basin divide.
END DESCRIPTION:
XS GIS Cut Line= 6
     3075853.248    13847200.553     3075268.926    13845056.133
     3075262.075    13845044.196     3075213.545    13844956.735
     3074891.111    13844407.863     3074212.278    13843161.276
#Sta/Elev= 30
       0   70.56  405.52   70.51  436.61   68.28  469.04   70.12  638.17    70.5
  716.46   71.91  810.09    70.2  878.35   70.89 1457.63   69.18 1587.08   69.42
 1707.77   71.02 1929.11   68.86 2219.25   68.71 2261.34   66.61 2261.69   66.55
 2275.34   62.28 2283.74    66.1 2283.78   66.11 2293.43   68.07 2310.59   68.72
 2461.52   70.46 2658.15   69.43 2884.31   70.52 3193.36   69.78 3415.09   72.39
 3571.34   70.52 3669.43   71.87 3808.24   72.05 4012.23   69.54  4392.4   70.55
#Mann= 3 ,-1 , 0
       0     .08       0 2261.34     .06       0 2283.74     .08       0
#XS Ineff= 5 ,-1
   -1.79 1709.23   71.02 1855.47 2055.06   69.32 2248.19 2261.46   67.76
 2286.74 2294.93   67.76 2501.73 4406.86   70.48
Permanent Ineff=
       F       F       F       F       F
#Block Obstruct= 2 , 0
                         3409.56           72.39
Bank Sta=2261.69,2283.78
XS Rating Curve= 0
Exp/Cntr=.5,.3

Type RM Length L Ch R = 3 ,7795.973,,,
BEGIN DESCRIPTION:
Structure 28 - unnamed wooden bridge
END DESCRIPTION:
Bridge Culvert--1,0,-1,-1, 0
Deck Dist Width WeirC Skew NumUp NumDn MinLoCord MaxHiCord MaxSubmerge Is_Ogee
4.5,14.1,2.6,0, 14, 16, , , .95, 0, 0,0,,
 2223.85 2232.19 2244.84 2248.42 2260.35 2260.43 2261.96 2283.61 2286.25 2295.94
 2299.14 2304.17 2313.73  2319.1
   68.61   68.52   68.41   68.21   67.74   68.75   68.75   68.71    68.7   67.97
   68.18   68.32   68.68    68.8
                                                      67   66.96   66.95
                                
 2192.85 2201.19 2213.84 2217.42 2229.35 2229.43 2230.96 2252.61 2255.25 2264.94
 2268.14 2273.17 2282.73  2288.1    2293 2320.89
   68.61   68.52   68.41   68.21   67.74   68.75   68.75   68.71    68.7   67.97
   68.18   68.32   68.68    68.8   68.92   68.92
                                                      67   66.96   66.95
                                                
BR Coef=-1 , 0 , 0 ,, 0 ,,,.8,-1,,0,
WSPro=,,,, 1 ,,,, 0 ,,,, 0 ,,,,-1 ,-1 ,-1 , 0 , 0 , 0 , 0 , 0
BC Design=,, 0 ,, 0 ,,,,,,
BC HTab HWMax=72.39

Type RM Length L Ch R = 1 ,7767.664,23.62,23.84,23.65
BEGIN DESCRIPTION:
Stations 2221.11 - 2257.43 developed from survey information (copied from cross-section 7743.82) , and the remainder developed from LiDAR. The elevations of the copied surveyed portion adjusted such that slope is consistent with closest surveyed data.
Blocked obstruction in the far overbank at basin divide.
END DESCRIPTION:
XS GIS Cut Line= 6
     3075890.284    13847156.272     3075316.994    13845104.521
     3075265.838    13844959.711     3075234.883    13844909.908
     3074924.534     13844383.99     3074260.345    13843163.773
#Sta/Elev= 30
       0   70.89  329.11   69.93   889.8   70.93 1391.19   69.25 1677.72   70.37
 1715.25   69.16 1776.18   69.52 1824.27   68.51 2198.74   68.77 2221.11   68.33
 2230.35   66.35 2244.18   61.75 2246.19   62.79 2248.62   66.54 2250.84   66.89
 2251.06   66.92 2257.43   67.92 2296.18   68.97 2465.32   70.08 2587.59   69.25
 3119.71   70.54 3258.65   69.65 3334.28   72.26 3436.75   71.65  3470.9   70.06
 3505.06   71.92 3590.45   71.21 3745.23   72.03 3966.17   69.75 4342.49   70.43
#Mann= 3 ,-1 , 0
       0     .08       0 2230.35     .06       0 2251.06     .08       0
#XS Ineff= 6 ,-1
       0 1676.26   70.39 1708.96 1775.07   69.52 1790.33 2026.81   69.31
 2223.34  2230.9    67.7 2251.62 2259.22   67.71 2453.89 4338.56   70.09
Permanent Ineff=
       F       F       F       F       F       F
#Block Obstruct= 2 , 0
                         3339.02           72.23
Bank Sta=2230.35,2250.84
XS Rating Curve= 0
Exp/Cntr=.5,.3

Type RM Length L Ch R = 1 ,7743.821,41.1,43.47,43.26
BEGIN DESCRIPTION:
Stations 2234.89 - 2271.21 developed from survey information, and the remainder developed from LiDAR
Blocked obstruction in the far overbank at basin divide.
END DESCRIPTION:
XS GIS Cut Line= 6
     3075919.458     13847157.04      3075332.43    13845077.456
     3075314.638     13845027.09      3075286.84    13844948.402
     3074953.182    13844388.764     3074301.729    13843165.923
#Sta/Elev= 30
       0   70.71  143.12   70.92   255.9   69.62  456.46   71.04  690.62   69.87
  891.26   70.83 1315.26   70.15  1405.6   68.27 1432.07   69.74 1608.38   70.14
 1857.14   68.51 2208.38   69.16 2234.89   67.84 2242.14   66.58 2257.96   61.26
 2259.97    62.3  2262.4   66.05 2263.38    66.2 2271.21   67.43 2367.74   69.71
 2567.44   69.12 3037.99   70.57  3243.3   69.68 3435.28   71.93 3469.87   70.58
 3503.86   72.27 3679.42      71 3792.79   71.79 4030.73    69.4 4334.81   70.05
#Mann= 3 ,-1 , 0
       0     .08       0 2242.14     .06       0 2263.38     .08       0
#XS Ineff= 8 ,-1
    -.81 1163.78   70.32 1176.34 1607.83   70.21 1701.52 1763.41   69.55
 1813.11  2034.5   69.27 2048.78 2184.47   69.24 2362.93 2448.84   69.71
 2454.04  2654.6   69.81 3040.29 4205.08   70.61
Permanent Ineff=
       F       F       F       F       F       F       F       F
#Block Obstruct= 2 , 0
                         3505.12           72.29
Bank Sta=2234.89,2271.21
XS Rating Curve= 0
Exp/Cntr=.3,.1

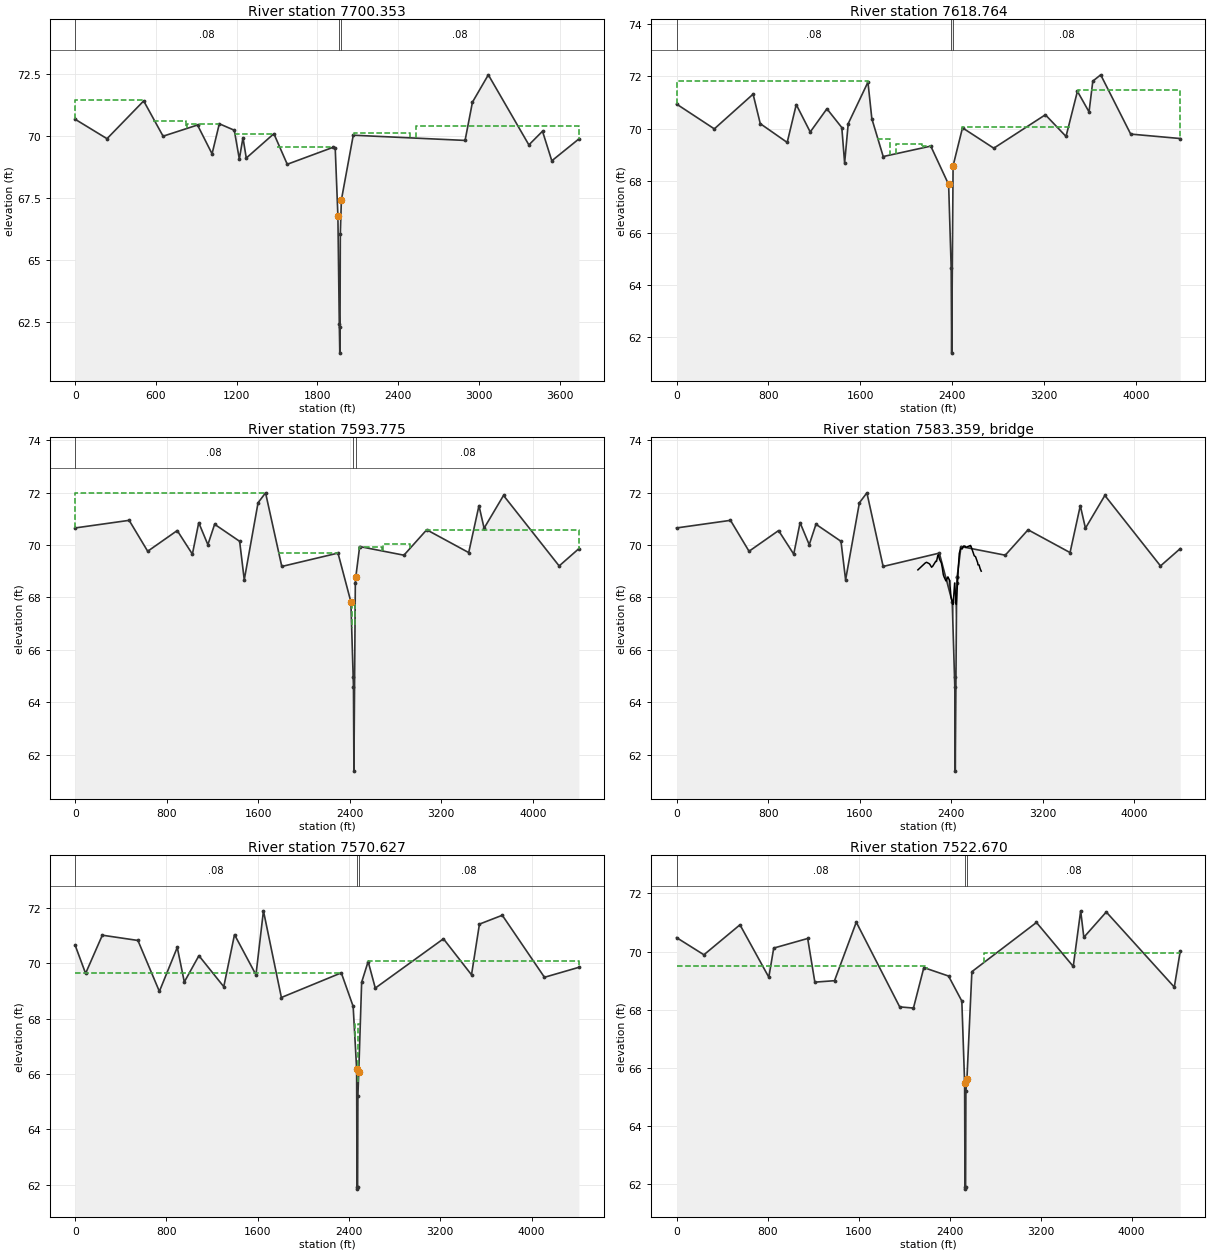
Type RM Length L Ch R = 1 ,7700.353,93.03,81.59,66.73
BEGIN DESCRIPTION:
Stations 2247.8 - 2284.65 developed from survey information (copied from cross-section 7743.82) , and the remainder developed from LiDAR. The elevations of the copied surveyed portion adjusted such that slope is consistent with closest surveyed data.
Blocked obstruction in the far overbank at basin divide.
END DESCRIPTION:
XS GIS Cut Line= 6
      3075966.84    13847158.287     3075379.619    13845109.824
     3075330.251     13844945.38     3075304.155    13844857.182
     3074985.014    13844310.777     3074371.764    13843169.561
#Sta/Elev= 30
       0   70.67 236.278   69.89 508.816   71.41 653.052   69.99 909.006   70.44
1017.112   69.281071.169   70.491182.471   70.231219.814   69.071246.843   69.93
1271.464   69.111476.573   70.091576.045   68.861915.259   69.541932.614    69.5
1952.437   66.791962.838   62.441966.614   61.261968.346    62.31970.459   66.05
1978.409   67.431978.565   67.432066.692   70.032897.799   69.822952.627   71.36
3070.605   72.463372.078   69.643473.351   70.193542.511      693743.802   69.88
#Mann= 3 ,-1 , 0
       0     .08       01962.838     .03       01978.409     .08       0
#XS Ineff= 7 ,-1
       0 508.565   71.44 580.211 821.936    70.6  831.35 1069.94    70.5
1189.0361477.846   70.091502.9611895.366   69.57 2075.492487.164   70.11
2530.8473745.698   70.41
Permanent Ineff=
       F       F       F       F       F       F       F
#Block Obstruct= 2 , 0
                        3064.093           72.49
Bank Sta=1952.437,1978.565
XS Rating Curve= 0
Skew Angle= 30
Exp/Cntr=.3,.1

Type RM Length L Ch R = 1 ,7618.764,26.65,24.99,24.21
BEGIN DESCRIPTION:
Stations 2368.18 - 2418.02 developed from survey information, and the remainder developed from LiDAR
Blocked obstruction in the far overbank at basin divide.
END DESCRIPTION:
XS GIS Cut Line= 6
     3076112.938    13847163.776     3075471.489    13844962.176
     3075346.284    13844882.115      3075318.23    13844861.396
     3074999.338     13844313.96     3074433.015    13843172.743
#Sta/Elev= 30
       0   70.94  328.66   69.99  666.07   71.32  728.56   70.19  962.92   69.47
 1041.85   70.92 1163.47   69.87 1308.65   70.76 1438.34   70.04 1462.87   68.68
 1494.12   70.19 1665.98   71.78 1699.81   70.38 1798.71   68.93 2212.81   69.33
 2368.18   67.86 2390.43   64.66 2394.68    61.4 2407.09   68.57 2407.23   68.58
 2488.95   70.03 2761.31   69.25 3210.34   70.53 3390.03    69.7 3489.36   71.43
 3590.36   70.64 3623.32   71.82 3692.01   72.06 3952.87   69.79 4384.19   69.62
#Mann= 3 ,-1 , 0
       0     .08       0 2390.43     .03       0 2407.09     .08       0
#XS Ineff= 6 ,-1
       0 1666.38   71.81 1747.32 1856.39   69.59 1907.89  2132.1    69.4
 2144.22  2213.9   69.33 2484.32 3435.67   70.06 3496.09 4405.03   71.47
Permanent Ineff=
       F       F       F       F       F       F
#Block Obstruct= 2 , 0
                         3686.01           72.09
Bank Sta=2368.18,2407.23
XS Rating Curve= 0
Exp/Cntr=.5,.3

Type RM Length L Ch R = 1 ,7593.775,21.3,23.15,24.63
BEGIN DESCRIPTION:
Stations 2410.19 - 2460.03 developed from survey information (copied from cross-section 7618.76) , and the remainder developed from LiDAR. The elevations of the copied surveyed portion adjusted such that slope is consistent with closest surveyed data.
Blocked obstruction in the far overbank at basin divide.
END DESCRIPTION:
XS GIS Cut Line= 6
      3076175.31    13847167.059     3075519.888    13844965.101
     3075362.628    13844863.886     3075337.609    13844845.408
     3074978.648     13844232.79       3074461.6    13843174.228
#Sta/Elev= 30
       0   70.65  471.49   70.94  633.68   69.76  891.85   70.55 1024.39   69.65
 1079.92   70.85  1159.9   70.01 1218.76   70.79  1437.5   70.14 1477.92   68.67
 1598.53   71.61  1664.1   71.99 1806.11   69.18 2297.43   69.69 2410.19   67.83
 2430.13   64.96  2432.8   64.58 2436.69   61.37 2449.02   68.53 2452.98   68.77
 2453.16   68.78 2486.94   69.94 2873.87   69.61 3073.17   70.58 3440.33   69.71
 3529.96    71.5 3574.92   70.64 3744.69   71.89  4231.1    69.2 4403.68   69.86
#Mann= 3 ,-1 , 0
       0     .08       0 2430.13     .03       0 2452.98     .08       0
#XS Ineff= 7 ,-1
   -3.03 1666.38   71.99 1771.66 2296.46   69.69 2410.56 2417.23   67.75
 2446.26  2449.6   67.75 2483.55 2683.52   69.94 2687.15 2923.48   70.02
  3063.3 4401.25   70.58
Permanent Ineff=
       F       F       F       F       F       F       F
#Block Obstruct= 2 , 0
                         3511.95           71.92
Bank Sta=2410.19,2453.16
XS Rating Curve= 0
Exp/Cntr=.5,.3

Type RM Length L Ch R = 3 ,7583.359,,,
BEGIN DESCRIPTION:
Structure 26 - unnamed wooden bridge
END DESCRIPTION:
Bridge Culvert--1,0,-1,-1, 0
Deck Dist Width WeirC Skew NumUp NumDn MinLoCord MaxHiCord MaxSubmerge Is_Ogee
6.8,4.6,2.6,0, 53, 56, , , .95, 0, 0,0,,
    2110  2173.5 2185.44  2211.7 2211.76 2229.94 2233.32 2238.22  2266.4 2272.71
 2284.63 2290.06 2290.65 2298.42 2315.51  2323.6  2332.4 2340.08 2355.06 2356.55
 2369.09 2373.03 2379.16 2389.04 2389.51 2390.76 2398.97 2416.66 2418.22 2431.22
 2445.31 2445.98 2463.39 2471.89 2483.73 2487.67 2496.64 2509.63 2521.32 2528.55
 2547.63 2569.26 2570.29 2570.75 2571.19  2574.4 2602.37 2614.23 2632.75 2635.66
  2644.8 2653.75 2663.78
   69.05   69.31   69.34   69.28   69.28   69.15   69.17   69.18   69.38   69.37
   69.61   69.62   69.62   69.46   69.31   69.12   68.86   68.77   68.63   68.63
   68.77   68.78   68.72   68.64   68.64   68.45   68.02   67.73   67.75   68.55
   67.75   67.73   69.13   69.68   69.88   69.87   69.85   69.96   69.96   69.91
   69.94   69.98   69.98   69.98   69.97   69.95   69.59   69.55   69.32   69.24
   69.24    69.1      69
                                                                                
                                                                                
                                                                    67.1    67.9
    67.1
                                                                                
                        
 2172.31 2173.88 2187.56 2192.11 2194.15  2208.6 2220.54  2246.8 2246.86 2265.04
 2268.42 2273.32  2301.5 2307.81 2319.73 2325.16 2325.75 2333.52 2350.61  2358.7
  2367.5 2375.18 2390.16 2391.65 2404.19 2408.13 2414.26 2424.14 2424.61 2425.86
 2434.07 2451.76 2453.32 2466.32 2480.41 2481.08 2498.49 2518.83 2522.77 2531.74
 2544.73 2556.42 2563.65 2582.73 2604.36 2605.39 2605.85 2606.29  2609.5 2637.47
 2649.33 2667.85 2670.76  2679.9 2688.85 2698.88
   69.05   69.04   69.16   69.21   69.21   69.31   69.34   69.28   69.28   69.15
   69.17   69.18   69.38   69.37   69.61   69.62   69.62   69.46   69.31   69.12
   68.86   68.77   68.63   68.63   68.77   68.78   68.72   68.64   68.64   68.45
   68.02   67.73   67.75   68.55   67.75   67.73   69.13   69.88   69.87   69.85
   69.96   69.96   69.91   69.94   69.98   69.98   69.98   69.97   69.95   69.59
   69.55   69.32   69.24   69.24    69.1      69
                                                                                
                                                                                
                                                                                
                    67.1    67.9    67.1
                                                                                
                                                
BR Coef=-1 , 0 , 0 ,, 0 ,,,.8,-1,,0,
WSPro=,,,, 1 ,,,, 0 ,,,, 0 ,,,,-1 ,-1 ,-1 , 0 , 0 , 0 , 0 , 0
BC Design=,, 0 ,, 0 ,,,,,,
BC HTab HWMax=71.92

Type RM Length L Ch R = 1 ,7570.627,46.62,47.96,50.86
BEGIN DESCRIPTION:
Stations 2467.05 - 2485.6 developed from survey information (copied from cross-section 7414.01) , and the remainder developed from LiDAR. The elevation of survey points adjusted to match the overall stream slope of approx. .0064 ft/ft.
Blocked obstruction in the far overbank at basin divide.
END DESCRIPTION:
XS GIS Cut Line= 6
     3076232.617    13847170.075       3075567.1     13844985.06
     3075509.396    13844941.308     3075344.541    13844820.304
     3074996.155    13844213.691     3074489.865    13843175.696
#Sta/Elev= 30
       0   70.64   90.91   69.63  237.65   71.01  549.62   70.82  737.79   68.98
  894.59   70.57  956.31   69.32 1084.36   70.27 1302.28   69.15 1396.36   71.03
 1584.53   69.58 1650.07   71.89 1807.24   68.76  2332.6   69.65 2436.49   68.44
 2467.05   66.18 2470.13    61.9 2472.63   61.84 2475.52   61.93 2478.15   65.22
  2485.6   66.07 2510.92   69.31 2567.96   70.06 2630.51    69.1 3228.05   70.88
 3474.16   69.58 3543.61   71.41 3743.88   71.73 4113.57   69.49 4415.45   69.85
#Mann= 3 ,-1 , 0
       0     .08       0  2466.3     .03       0 2485.81     .08       0
#XS Ineff= 4 ,-1
       0 2330.01   69.66 2441.22 2451.83   67.79 2482.38 2499.67   67.79
 2569.25 4415.45   70.07
Permanent Ineff=
       F       F       F       F
#Block Obstruct= 2 , 0
                          3543.8           71.76
Bank Sta=2467.05,2485.6
XS Rating Curve= 0
Exp/Cntr=.5,.3

Type RM Length L Ch R = 1 ,7522.670,108.83,108.66,109.1
BEGIN DESCRIPTION:
Stations 2532.41 - 2551.03 developed from survey information (copied from cross-section 7414.01) , and the remainder developed from LiDAR. The elevation of survey points adjusted to match the overall stream slope of approx. .0064 ft/ft.
Blocked obstruction in the far overbank at basin divide.
END DESCRIPTION:
XS GIS Cut Line= 6
      3076310.57    13847174.178     3075629.218    13845003.097
     3075521.181    13844905.238     3075349.917    13844754.892
     3075043.902    13844200.959     3074528.357    13843177.696
#Sta/Elev= 30
       0   70.48  240.45   69.89  557.32   70.92  810.99   69.12  854.06   70.12
 1152.77   70.45 1215.66   68.95 1388.59      69 1579.92   71.01 1961.62    68.1
 2082.49   68.06  2173.8   69.45 2390.94   69.16 2507.83    68.3  2532.3   65.49
 2532.34   65.49  2535.5    61.9 2538.01   61.84 2540.91   61.93 2543.55   65.22
 2552.27   65.58 2552.44   65.61 2596.23   69.31 3163.93      71 3487.22   69.49
 3552.59    71.4 3580.41   70.49 3777.61   71.36  4375.6   68.78 4427.79   70.01
#Mann= 3 ,-1 , 0
       0     .08       0 2532.34     .03       0 2552.27     .08       0
#XS Ineff= 2 , 0
         2203.94   69.49 2699.73           69.96
Permanent Ineff=
       F       F
#Block Obstruct= 2 , 0
                         3549.49           71.54
Bank Sta=2532.3,2552.44
XS Rating Curve= 0
Exp/Cntr=.3,.1

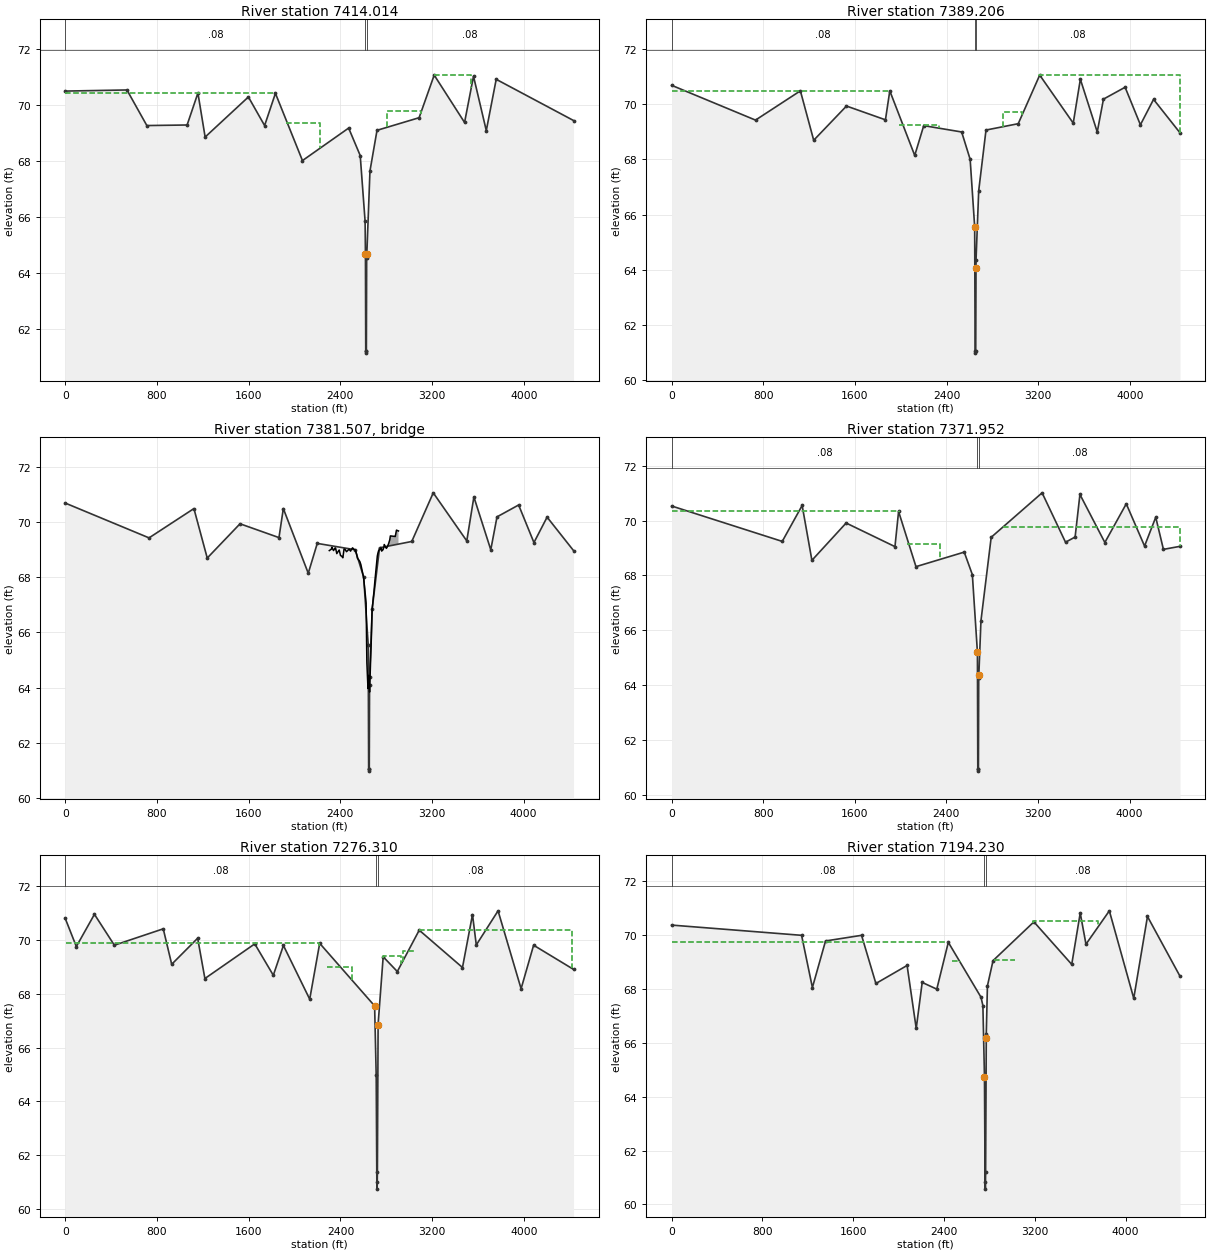
Type RM Length L Ch R = 1 ,7414.014,24.63,24.81,24.64
BEGIN DESCRIPTION:
Stations 2618.9 - 2637.52 developed from survey information, and the remainder developed from LiDAR
Blocked obstruction in the far overbank at basin divide.
END DESCRIPTION:
XS GIS Cut Line= 6
     3076398.571    13847178.809      3075684.37    13844908.467
     3075589.842    13844822.844     3075364.834    13844627.532
     3075113.932    13844162.761     3074613.106    13843182.099
#Sta/Elev= 30
       0   70.49  538.44   70.53  712.28   69.26 1063.52   69.28 1157.87   70.42
 1220.77   68.85 1598.16   70.28 1739.68   69.26 1834.03   70.41  2069.9   68.01
 2472.89   69.17 2573.79   68.19  2616.3   65.85 2619.45   64.66 2619.49    64.6
    2622    61.2  2624.5   61.14 2627.41   61.23 2630.05   64.52 2631.38   64.67
 2631.56   64.69 2658.82   67.64 2720.35   69.09 3087.63   69.54 3219.25   71.06
 3484.19   69.37 3562.17   71.02 3673.72   69.08 3760.23   70.91 4434.86   69.44
#Mann= 3 ,-1 , 0
       0     .08       0 2619.49     .03       0 2631.56     .08       0
#XS Ineff= 4 ,-1
       0 1834.07   70.43 1923.22 2226.15   69.34 2804.85 3099.93   69.79
 3219.11 3542.45   71.07
Permanent Ineff=
       F       F       F       F
#Block Obstruct= 2 , 0
                         3555.18           71.07
Bank Sta=2619.45,2631.38
XS Rating Curve= 0
Exp/Cntr=.5,.3

Type RM Length L Ch R = 1 ,7389.206,17.49,17.25,17.43
BEGIN DESCRIPTION:
Stations 2645.32 - 2663.95 developed from survey information (copied from cross-section 7414.01) , and the remainder developed from LiDAR. The elevation of survey points adjusted to match the overall stream slope of approx. .0064 ft/ft.
Blocked obstruction in the far overbank at basin divide.
END DESCRIPTION:
XS GIS Cut Line= 6
       3076428.3    13847180.374     3075696.977    13844886.941
     3075603.118    13844801.924     3075369.776     13844599.64
     3075137.805    13844169.127      3074638.64    13843183.425
#Sta/Elev= 30
       0   70.68  731.72   69.42 1123.34   70.48 1239.67   68.69 1525.78   69.93
 1865.79   69.43 1903.73   70.48 2121.34   68.14 2199.97   69.22 2530.88   68.99
 2605.05      68 2644.48   65.56 2644.61   65.54 2648.42   61.04 2650.92   60.98
 2653.83   61.07 2656.24   64.08 2656.55   64.37 2679.68   66.86 2743.46   69.06
 3024.82   69.29 3212.25   71.05 3504.86   69.31 3566.91    70.9 3714.35   68.99
 3768.68   70.18 3957.43   70.61 4091.04   69.25 4205.83   70.17  4436.6   68.96
#Mann= 3 ,-1 , 0
       0     .08       0 2644.48     .03       0 2656.55     .08       0
#XS Ineff= 4 ,-1
     .29 1900.33   70.48 1981.71 2329.51   69.25 2893.77 3058.72   69.73
 3207.64 4457.58   71.06
Permanent Ineff=
       F       F       F       F
#Block Obstruct= 2 , 0
                         3560.86           70.95
Bank Sta=2644.61,2656.24
XS Rating Curve= 0
Exp/Cntr=.5,.3

Type RM Length L Ch R = 3 ,7381.507,,,
BEGIN DESCRIPTION:
Structure 25 - wooden walk bridge
END DESCRIPTION:
Bridge Culvert--1,0,-1,-1, 0
Deck Dist Width WeirC Skew NumUp NumDn MinLoCord MaxHiCord MaxSubmerge Is_Ogee
4.2,4.3,2.6,0, 71, 66, , , .95, 0, 0,0,,
 2304.87  2322.6 2327.72 2341.76 2356.53 2360.52 2362.33 2370.19 2382.57 2391.43
 2401.22 2402.81 2412.67 2423.05 2423.56 2433.91 2443.29 2455.15 2477.76 2490.59
 2497.87 2508.25 2518.03  2532.6 2533.99 2544.33 2550.74 2564.29    2572 2580.78
 2602.59 2603.89 2609.25 2623.06 2624.17 2626.25 2632.72 2642.47 2643.97 2649.39
 2656.57 2672.33 2678.29 2684.05 2688.92 2694.46  2697.6  2701.1 2711.49 2723.97
 2728.84 2735.54 2752.69 2755.87 2761.88 2762.69 2763.85 2773.97 2783.41 2784.62
 2802.97 2809.44 2822.52 2832.82 2837.86 2842.08 2880.18 2880.46  2881.2 2891.11
 2908.95
   68.96   69.01   69.08   68.96   69.06   69.04      69   68.85   68.93   68.98
   68.81   68.78   68.76    68.7   68.71   69.02      69   68.92   69.01   68.94
      69   69.06   69.01   68.98   68.96   68.81   68.68   68.61   68.56   68.45
   68.02      68   67.78   67.21   67.16   67.06   64.92   63.97    64.2   64.45
   63.84   65.84   66.83   67.04   67.26   67.46   67.61   67.78   68.23   68.76
   68.86   68.96   69.04   69.06   68.95   68.94   68.96   68.99   69.12   69.18
   69.04   69.08   69.21   69.35   69.49   69.49   69.47   69.47   69.48    69.7
   69.67
                                                                                
                                                                                
                                                                                
                                                                    63.2   63.45
   62.84
                                                                                
                                                                                
        
 2330.75 2348.48  2353.6 2367.64 2382.41  2386.4 2388.21 2396.07 2408.45 2417.31
  2427.1 2428.69 2438.55 2448.93 2449.44 2459.79 2469.17 2481.03 2503.64 2516.47
 2523.75 2534.13 2543.91 2558.48 2559.87 2570.21 2576.62 2590.17 2597.88 2606.66
 2628.47 2629.77 2635.13 2648.94 2650.05 2652.13  2658.6 2668.35 2669.85 2675.27
 2682.45 2698.21 2704.17 2709.93  2714.8 2720.34 2723.48 2726.98 2737.37 2749.85
 2754.72 2761.42 2778.57 2781.75 2787.76 2788.57 2789.73 2799.85 2809.29  2810.5
 2828.85 2835.32  2848.4  2858.7 2863.74 2867.96
   68.96   69.01   69.08   68.96   69.06   69.04      69   68.85   68.93   68.98
   68.81   68.78   68.76    68.7   68.71   69.02      69   68.92   69.01   68.94
      69   69.06   69.01   68.98   68.96   68.81   68.68   68.61   68.56   68.45
   68.02      68   67.78   67.21   67.16   67.06   64.92   63.97    64.2   64.45
   63.84   65.84   66.83   67.04   67.26   67.46   67.61   67.78   68.23   68.76
   68.86   68.96   69.04   69.06   68.95   68.94   68.96   68.99   69.12   69.18
   69.04   69.08   69.21   69.35   69.49   69.49
                                                                                
                                                                                
                                                                                
                                                                    63.2   63.45
   62.84
                                                                                
                                                
BR Coef=-1 , 0 , 0 ,, 0 ,,,.8,-1,,0,
WSPro=,,,, 1 ,,,, 0 ,,,, 0 ,,,,-1 ,-1 ,-1 , 0 , 0 , 0 , 0 , 0
BC Design=,, 0 ,, 0 ,,,,,,
BC HTab HWMax=71.05

Type RM Length L Ch R = 1 ,7371.952,87.44,95.64,102.82
BEGIN DESCRIPTION:
Stations 2670.87 - 2689.82 developed from survey information (copied from cross-section 7414.01) , and the remainder developed from 2689.82 The elevation of survey points adjusted to match the overall stream slope of approx. .0064 ft/ft.
Blocked obstruction in the far overbank at basin divide.
END DESCRIPTION:
XS GIS Cut Line= 6
     3076460.792    13847182.084     3075991.396    13845701.159
     3075720.545    13844885.531     3075374.729    13844581.623
     3075155.312    13844167.536     3074664.109    13843184.748
#Sta/Elev= 30
       0   70.53  965.93   69.24 1139.88   70.55 1225.04   68.55 1524.01   69.91
 1950.63   69.05 1982.24   70.33 2134.21   68.32 2555.71   68.85 2626.71   68.03
 2670.87   65.21    2671   65.21 2674.29   60.93  2676.8   60.87  2679.7   60.96
 2682.34   64.25  2683.3   64.36 2683.52   64.38 2701.88   66.35 2791.29   69.39
 3236.02   71.01 3440.65   69.21  3524.5    69.4 3566.52   70.95 3784.24    69.2
 3971.32   70.61 4131.09   69.07  4228.8   70.12 4295.88   68.95 4440.71   69.06
#Mann= 3 ,-1 , 0
       0     .08       0    2671     .03       0 2683.52     .08       0
#XS Ineff= 3 ,-1
   -3.51 1982.42   70.33 2058.19 2343.18   69.16 2891.44 4440.71   69.78
Permanent Ineff=
       F       F       F
#Block Obstruct= 2 , 0
                         3546.08              71
Bank Sta=2670.87,2683.3
XS Rating Curve= 0
Exp/Cntr=.5,.3

Type RM Length L Ch R = 1 ,7276.310,81.73,82.08,82.85
BEGIN DESCRIPTION:
Stations 2697.57 - 2737.53 developed from survey information (copied from cross-section 7194.23) , and the remainder developed from LiDAR. The elevations of the copied surveyed portion adjusted such that slope is consistent with closest surveyed data.
Blocked obstruction in the far overbank at basin divide.
END DESCRIPTION:
XS GIS Cut Line= 6
     3076544.319     13847186.48     3075800.754    13844931.743
     3075644.481    13844776.907     3075577.856    13844634.966
      3075383.33    13844444.219      3074745.65    13843188.984
#Sta/Elev= 30
       0   70.81   97.01   69.76  254.88   70.96  428.53   69.81  854.76   70.42
  928.46    69.1  1154.7   70.07 1217.84   68.57 1652.59   69.86 1814.33   68.69
 1902.41    69.8 2131.69    67.8 2218.66   69.88 2697.57   67.55 2711.28   64.96
 2716.88   61.01 2719.48   60.73 2721.69   61.37 2727.94   66.83 2727.99   66.87
 2772.22   69.38 2895.41   68.83 3086.48   70.37 3463.51   68.98 3550.87   70.95
 3583.88   69.82 3773.76   71.09 3974.58   68.19 4083.69   69.81 4431.72   68.91
#Mann= 3 ,-1 , 0
       0     .08       0 2711.28     .03       0 2727.99     .08       0
#XS Ineff= 5 ,-1
    3.95 2213.74   69.88 2284.82 2503.97      69 2771.29 2931.47   69.41
 2941.11 3039.86   69.59 3085.89 4416.16   70.38
Permanent Ineff=
       F       F       F       F       F
#Block Obstruct= 2 , 0
                         3538.11            71.1
Bank Sta=2697.57,2727.94
XS Rating Curve= 0
Exp/Cntr=.3,.1

Type RM Length L Ch R = 1 ,7194.230,51.73,45.6,40.94
BEGIN DESCRIPTION:
Stations 2742.36 - 2782.32 developed from survey information, and the remainder developed from LiDAR
Blocked obstruction in the far overbank at basin divide.
END DESCRIPTION:
XS GIS Cut Line= 6
     3076671.717    13847193.692     3075905.461    13844939.728
     3075722.103    13844758.056     3075655.478    13844616.115
     3075386.697    13844359.551     3074790.303    13843191.304
#Sta/Elev= 30
       0   70.38 1144.77      70 1239.99   68.06 1355.79   69.79 1673.15      70
 1799.53   68.21  2074.5   68.88 2154.95   66.54 2207.58   68.25 2336.16      68
  2437.7   69.74 2725.78    67.7 2742.36   67.39  2756.2   64.77 2756.33   64.75
 2761.67   60.85 2764.27   60.57 2766.48   61.21 2772.19    66.2 2772.37   66.35
 2782.32   68.12 2831.93   69.06 3191.94    70.5 3525.27   68.92 3600.17   70.83
 3650.69   69.67 3856.67   70.91 4071.73   67.66 4192.68    70.7 4479.29   68.48
#Mann= 3 ,-1 , 0
       0     .08       0  2756.2     .03       0 2772.37     .08       0
#XS Ineff= 4 ,-1
  -10.55 2438.12   69.74 2474.15 2542.93   69.03 2836.32 3026.56   69.09
  3184.3 3757.68   70.54
Permanent Ineff=
       F       F       F       F
#Block Obstruct= 2 , 0
                         3764.51           70.95
Bank Sta=2756.33,2772.19
XS Rating Curve= 0
Exp/Cntr=.5,.3

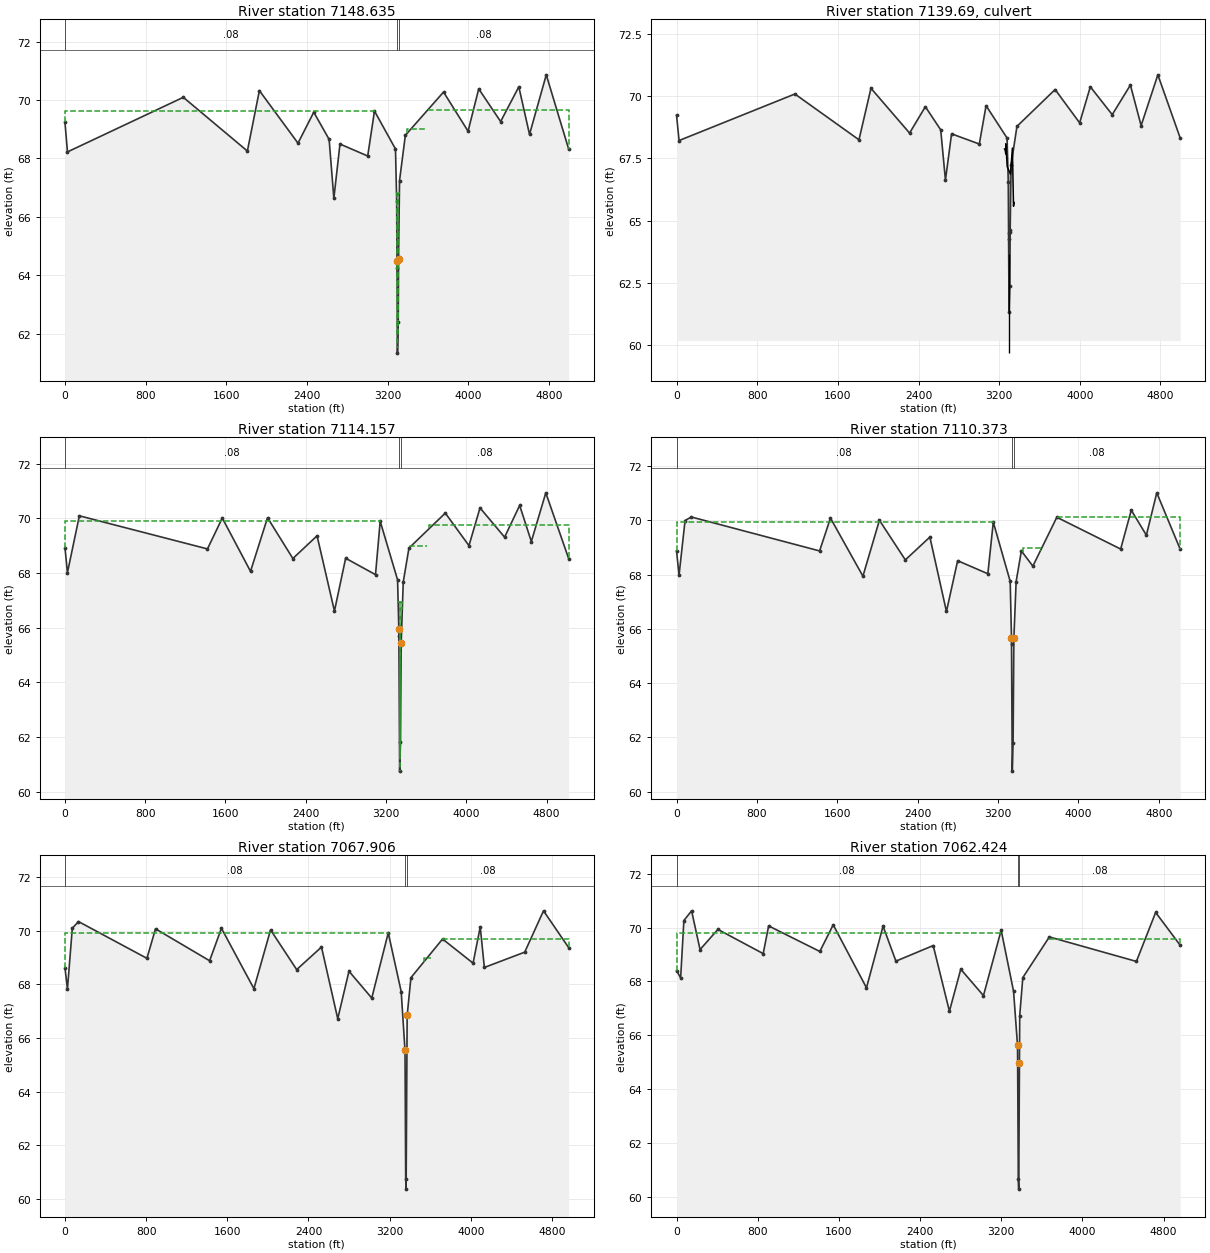
Type RM Length L Ch R = 1 ,7148.635,40.7,34.48,29.66
BEGIN DESCRIPTION:
Stations 3278.51 - 3318.7 developed from survey information (copied from cross-section 7114.16) , and the remainder developed from LiDAR.  The elevations of the copied surveyed portion adjusted such that slope is consistent with closest surveyed data.
Blocked obstruction in the far overbank at basin divide.
END DESCRIPTION:
XS GIS Cut Line= 6
      3076917.32     13847672.63     3075930.016    13844868.398
     3075685.418     13844596.94     3075608.036    13844540.165
     3075466.397    13844416.646     3074840.151    13843193.893
#Sta/Elev= 30
       0   69.23   24.72   68.22 1173.72   70.09 1809.35   68.25 1928.37   70.32
 2311.39   68.52 2467.88   69.58 2620.14   68.65  2667.1   66.63 2727.83   68.49
 3002.96   68.08 3070.19   69.62 3278.51   68.32 3290.25   66.55 3293.26    64.5
 3293.61   64.26 3297.92   61.33 3305.78   62.38    3309   64.56  3309.1   64.63
  3318.7   67.24 3376.37   68.79 3755.13   70.27 3998.41   68.93 4104.23   70.38
  4321.5   69.26 4501.84   70.45    4608   68.82 4774.14   70.86 4996.08   68.32
#Mann= 3 ,-1 , 0
       0     .08       0 3293.61     .03       0  3309.1     .08       0
#XS Ineff= 5 ,-1
       0 3070.36   69.62 3284.26 3297.67   66.81  3302.8 3325.67   66.82
 3395.45 3576.99   69.02 3600.38 5002.02   69.66
Permanent Ineff=
       F       F       F       F       F
#Block Obstruct= 2 , 0
                         4443.69            70.9
Bank Sta=3293.26,3309
XS Rating Curve= 0
Exp/Cntr=.5,.3

Type RM Length L Ch R = 2 ,7139.69 ,,,
BEGIN DESCRIPTION:
Structure 24 - concrete bridge
END DESCRIPTION:
Bridge Culvert--1,0,-1,-1, 0
Deck Dist Width WeirC Skew NumUp NumDn MinLoCord MaxHiCord MaxSubmerge Is_Ogee
6.88,10.1,2.6,0, 9, 9, , , .95, 0, 0,0,,
 3253.29 3259.83 3265.81 3266.02  3279.9 3312.67 3331.12  3342.3 3348.36
   67.88   67.83   67.68   68.09   67.17   66.87   67.92   65.58   65.73
                                                                        
 3291.22 3297.76 3303.74 3303.95 3317.83  3350.6 3369.05 3380.23 3386.29
   67.88   67.83   67.68   68.09   67.17   66.87   67.92   65.58   65.73
                                                                        
Culvert=2,4,4,10.1,.013,.5,1,8,2,59.68,3300.01,60.68,3337.94,Culvert #1  , 0 ,6.88
Culvert Bottom n=.013
BC Design=,, 0 ,, 0 ,,,,,,
BC HTab HWMax=70.86

Type RM Length L Ch R = 1 ,7114.157,3.72,3.78,3.84
BEGIN DESCRIPTION:
Stations 3315.21 - 3354.38 developed from survey information, and the remainder developed from LiDAR
Blocked obstruction in the far overbank at basin divide.
Blocked obstruction in the far overbank at basin divide.
END DESCRIPTION:
XS GIS Cut Line= 6
      3076962.24     13847672.32     3075939.796    13844824.972
     3075764.102     13844615.26     3075615.163    13844536.136
     3075481.625    13844419.193     3074855.685      13843194.7
#Sta/Elev= 30
       0   68.93   24.46   68.01  143.38   70.09 1420.29   68.88 1567.93   70.01
  1849.4   68.06 2018.89   70.02 2271.53   68.53 2512.61   69.36 2685.99   66.61
 2797.58   68.54 3095.21   67.94 3141.92   69.89 3315.21   67.75 3327.76   65.94
 3328.11   65.71 3335.85   60.76 3344.22   61.81  3350.8   65.37 3350.95   65.43
  3371.6   67.67 3428.56   68.91 3790.98   70.19 4026.82      69 4136.77   70.38
 4382.02   69.31 4532.21   70.47 4648.45   69.15 4792.63   70.93  5020.3   68.53
#Mann= 3 ,-1 , 0
       0     .08       0 3328.11     .06       0  3350.8     .08       0
#XS Ineff= 5 ,-1
       0 3142.77    69.9 3320.37  3335.9   66.95 3340.03 3362.35   66.95
 3436.39 3610.29   68.98  3631.5 5022.72   69.76
Permanent Ineff=
       F       F       F       F       F
#Block Obstruct= 2 , 0
                         4518.77              71
Bank Sta=3327.76,3350.95
XS Rating Curve= 0
Exp/Cntr=.5,.3

Type RM Length L Ch R = 1 ,7110.373,34.8,42.47,50.54
BEGIN DESCRIPTION:
Stations 3320.83 - 3363.6 developed from survey information (copied from cross-section 7114.16) , and the remainder developed from LiDAR.
Blocked obstruction in the far overbank at basin divide.
Blocked obstruction in the far overbank at basin divide.
END DESCRIPTION:
XS GIS Cut Line= 6
     3076970.229    13847672.265      3075946.29    13844823.349
     3075766.017    13844612.067     3075617.078    13844532.944
     3075493.301    13844412.574     3074870.826    13843195.487
#Sta/Elev= 30
       0   68.87    24.4   67.97   84.61   69.99  146.92   70.12 1423.71   68.87
  1531.8   70.08 1854.96   67.94  2019.1      70 2277.08   68.54 2521.27   69.38
 2686.34   66.64  2797.9   68.51 3098.39   68.03 3152.67   69.93 3320.83   67.75
 3333.82   65.66 3334.17   65.43 3341.48   60.76 3349.85   61.81 3357.43   65.64
 3357.58   65.66  3379.9   67.74 3432.24   68.87 3546.46   68.31 3785.08   70.11
 4420.45   68.94 4526.16   70.37 4676.36   69.45 4779.92   71.01 5013.42   68.93
#Mann= 3 ,-1 , 0
       0     .08       0 3334.17     .06       0 3357.43     .08       0
#XS Ineff= 3 ,-1
       0  3150.1   69.94 3443.68 3622.73   68.97 3793.06 5015.87   70.11
Permanent Ineff=
       F       F       F
#Block Obstruct= 2 , 0
                         4518.77           71.07
Bank Sta=3333.82,3357.58
XS Rating Curve= 0
Exp/Cntr=.3,.1

Type RM Length L Ch R = 1 ,7067.906,5.18,5.48,4.78
BEGIN DESCRIPTION:
Stations 3352.42 - 3388.94 developed from survey information, and the remainder developed from LiDAR
Blocked obstruction in the far overbank at basin divide.
Blocked obstruction in the far overbank at basin divide.
END DESCRIPTION:
XS GIS Cut Line= 6
     3076981.413    13847672.188     3076268.399     13845698.75
     3075930.862    13844774.502      3075724.33    13844521.603
     3075532.356    13844360.207     3074937.169    13843198.933
#Sta/Elev= 30
       0   68.62   24.34   67.82   72.18   70.09  133.22   70.34  807.91   68.97
  892.43   70.07 1425.72   68.88 1542.18   70.09 1862.34   67.84 2026.37   70.03
 2283.82   68.55 2528.38   69.39 2688.56   66.72 2799.28   68.49 3023.91   67.49
 3186.49   69.92 3314.03   67.73 3351.42   65.55 3351.62   65.53 3358.37   60.73
 3362.52   60.37 3372.82   66.84 3409.97   68.25 3721.84   69.69 4022.36   68.79
 4093.21   70.14  4133.8   68.63 4531.45    69.2 4716.86   70.74 4964.48   69.37
#Mann= 3 ,-1 , 0
       0     .08       0 3351.62     .06       0 3372.82     .08       0
#XS Ineff= 3 ,-1
       0 3183.92   69.92  3535.5 3605.64   68.98 3720.08 4971.57    69.7
Permanent Ineff=
       F       F       F
#Block Obstruct= 2 , 0
                         4715.59           70.78
Bank Sta=3351.42,3372.82
XS Rating Curve= 0
Exp/Cntr=.3,.1

Type RM Length L Ch R = 1 ,7062.424,13.52,13.4,13.38
BEGIN DESCRIPTION:
Stations 3361.75 - 3398.27 developed from survey information (copied from cross-section 7067.91) , and the remainder developed from LiDAR. The elevation of survey points adjusted to match the overall stream slope of approx. .0064 ft/ft.
Blocked obstruction in the far overbank at basin divide.
END DESCRIPTION:
XS GIS Cut Line= 6
     3076993.611    13847672.104     3076282.851    13845705.976
     3075944.806    13844784.109      3075726.16    13844516.373
     3075541.549    13844361.166     3074948.832    13843199.539
#Sta/Elev= 30
       0    68.4    40.2   68.13    72.1   70.26  148.21   70.62  231.41   69.18
  407.27   69.93  853.65   69.03  907.29   70.06  1411.9   69.11 1543.63    70.1
 1871.65   67.76 2034.94   70.05 2161.67   68.75 2529.14   69.33  2688.9   66.89
 2800.74   68.45 3024.41   67.47 3198.84    69.9 3321.07   67.63 3360.05   65.62
 3360.25    65.6  3367.7   60.64 3371.85   60.28 3379.06   64.98 3381.74   66.73
 3412.25   68.14 3673.47   69.65 4531.56   68.74 4721.27   70.56 4963.51   69.34
#Mann= 3 ,-1 , 0
       0     .08       0 3360.25     .06       0 3379.06     .08       0
#XS Ineff= 2 , 0
         3196.15    69.8 3673.34           69.56
Permanent Ineff=
       F       F
#Block Obstruct= 2 , 0
                         4715.59           70.47
Bank Sta=3360.05,3379.06
XS Rating Curve= 0
Exp/Cntr=.5,.3