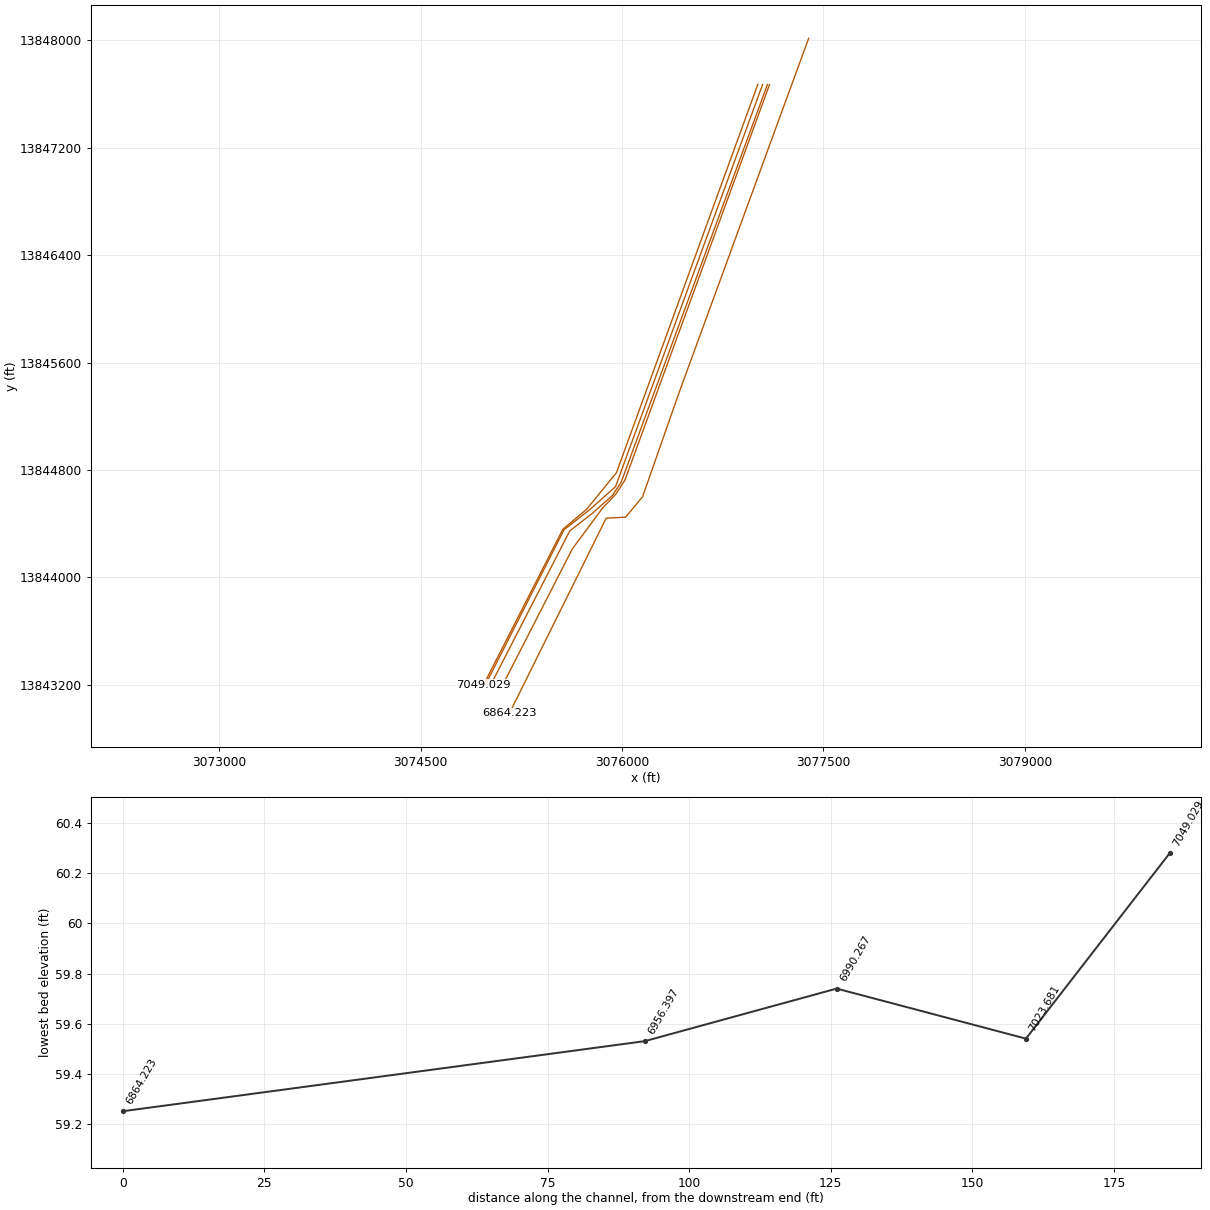
HEC-RAS study W141-00-00.prj: W141-00-00

--- W141-00-00.g01 (geometry) --- (continued)

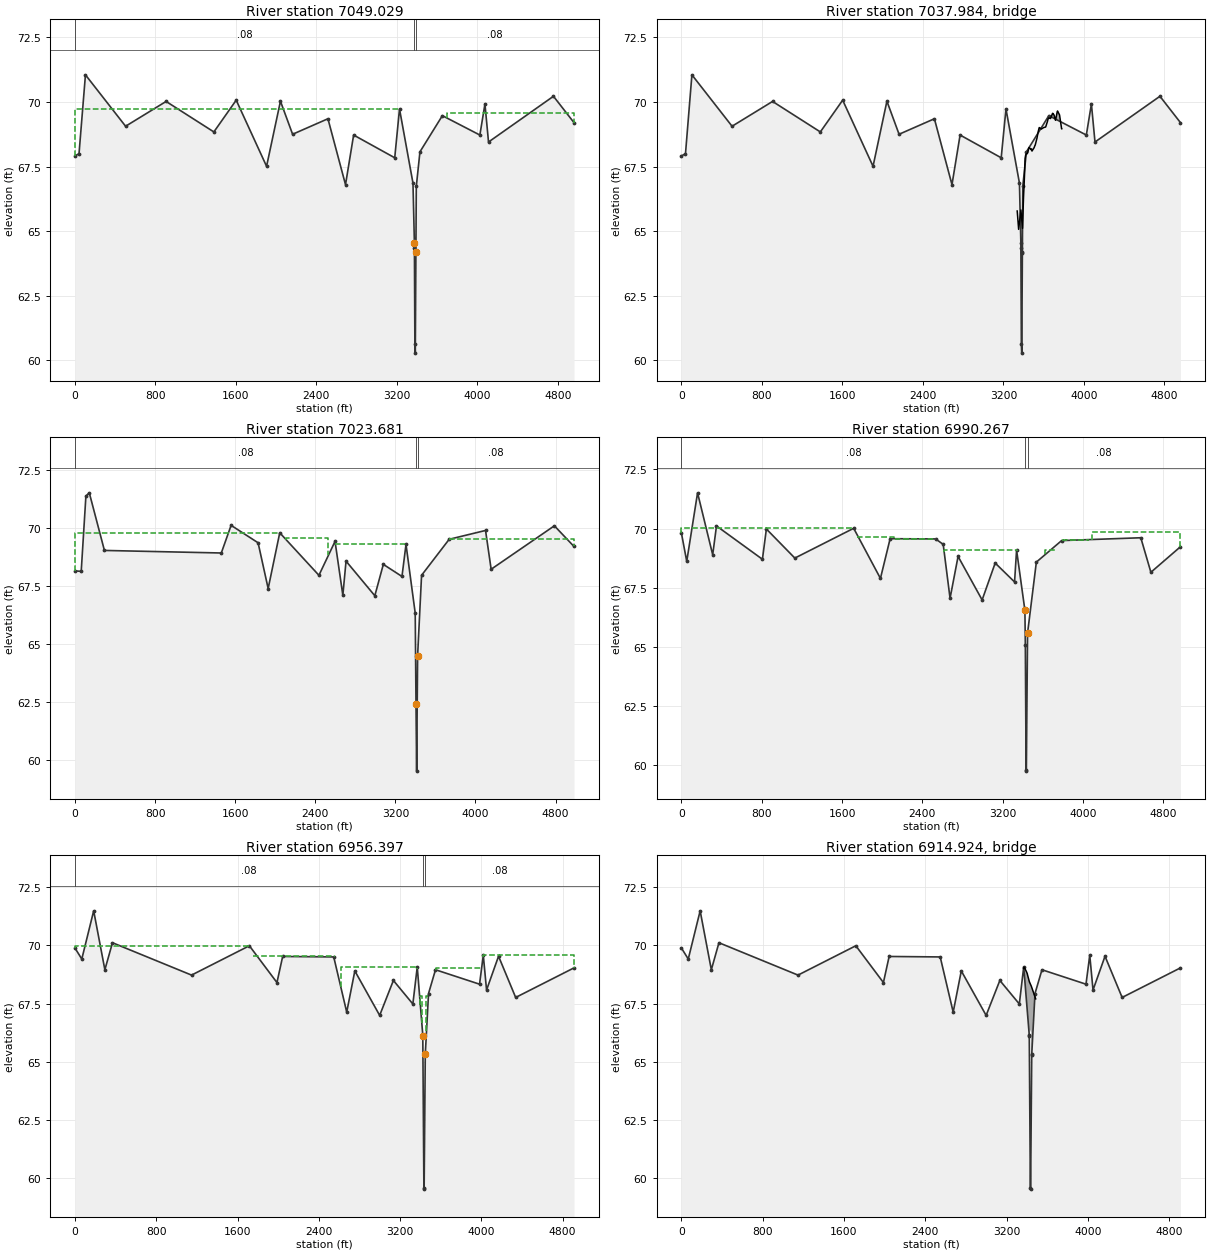
Type RM Length L Ch R = 1 ,7049.029,28.1,25.35,22.67
BEGIN DESCRIPTION:
Stations 3372.81 - 3409.32 developed from survey information (copied from cross-section 7067.91) , and the remainder developed from LiDAR. The elevation of survey points adjusted to match the overall stream slope of approx. .0064 ft/ft.
Blocked obstruction in the far overbank at basin divide.
END DESCRIPTION:
XS GIS Cut Line= 6
     3077011.417    13847671.981     3075958.521    13844779.789
     3075784.115    13844566.161     3075736.218    13844507.573
     3075559.561    13844359.054     3074969.095    13843200.591
#Sta/Elev= 30
       0   67.91    40.1      68  103.95   71.05  503.03   69.06  905.65   70.02
 1380.57   68.84 1602.62   70.07 1904.44   67.51 2042.31   70.03 2163.19   68.75
 2514.38   69.35 2689.14    66.8 2769.78   68.72 3178.42   67.84 3225.86   69.73
 3359.74   66.86 3373.81   64.55 3374.06   64.35 3378.75   60.64  3382.9   60.28
 3388.84   64.15 3388.89   64.19 3392.79   66.73 3429.02   68.07 3651.98   69.47
 4024.64   68.72 4075.15   69.92 4110.73   68.45 4756.28   70.22  4960.4    69.2
#Mann= 3 ,-1 , 0
       0     .08       0 3374.06     .06       0 3388.84     .08       0
#XS Ineff= 2 , 0
         3224.55   69.73 3693.79           69.56
Permanent Ineff=
       F       F
#Block Obstruct= 2 , 0
                         4647.33           70.24
Bank Sta=3373.81,3388.89
XS Rating Curve= 0
Exp/Cntr=.5,.3

Type RM Length L Ch R = 3 ,7037.984,,,
BEGIN DESCRIPTION:
Structure 22 - wooden walk bridge
END DESCRIPTION:
Bridge Culvert--1,0,-1,-1, 0
Deck Dist Width WeirC Skew NumUp NumDn MinLoCord MaxHiCord MaxSubmerge Is_Ogee
10,4.8,2.6,0, 47, 45, , , .95, 0, 0,0,,
 3337.52 3337.65 3344.05 3351.66 3374.15  3390.4 3400.06 3410.52 3416.09 3421.52
 3433.12 3435.78 3444.37 3452.36 3455.96 3465.45 3476.15  3480.2 3484.54 3505.51
  3514.2 3516.51 3534.04 3546.06 3556.46 3560.72 3577.07 3577.92 3579.94 3601.29
 3620.41 3637.62 3640.26 3643.09 3651.13 3668.55 3688.97 3694.76 3704.07 3718.36
  3735.8 3738.54 3758.22 3758.72 3763.32 3778.91 3779.25
   65.78   65.77   65.46   65.07   65.82   65.11   66.29    67.2   67.82   67.95
      68      68   68.07   68.21   68.24    68.2   68.15   68.18    68.1   68.23
   68.32   68.33    68.6   68.85   69.01      69   68.96   68.95   68.96   69.01
   69.03   69.24   69.28   69.33   69.38   69.36   69.56   69.55   69.49   69.29
   69.63   69.65    69.5   69.49   69.37   68.96   68.96
                                   65.22   64.51
                                                                                
                                                                                
                                                                                
                                                        
 3374.55 3382.16 3404.65  3420.9 3430.56 3441.02 3446.59 3452.02 3463.62 3466.28
 3474.87 3482.86 3486.46 3495.95 3506.65  3510.7 3515.04 3536.01  3544.7 3547.01
 3564.54 3576.56 3586.96 3591.22 3607.57 3608.42 3610.44 3631.79 3650.91 3668.12
 3670.76 3673.59 3681.63 3699.05 3719.47 3725.26 3734.57 3748.86  3766.3 3769.04
 3788.72 3789.22 3793.82 3809.41 3809.75
   65.46   65.07   65.82   65.11   66.29    67.2   67.82   67.95      68      68
   68.07   68.21   68.24    68.2   68.15   68.18    68.1   68.23   68.32   68.33
    68.6   68.85   69.01      69   68.96   68.95   68.96   69.01   69.03   69.24
   69.28   69.33   69.38   69.36   69.56   69.55   69.49   69.29   69.63   69.65
    69.5   69.49   69.37   68.96   68.96
                   65.22   64.51
                                                                                
                                                                                
                                                                                
                                        
BR Coef=-1 , 0 , 0 ,, 0 ,,,.8,-1,,0,
WSPro=,,,, 1 ,,,, 0 ,,,, 0 ,,,,-1 ,-1 ,-1 , 0 , 0 , 0 , 0 , 0
BC Design=,, 0 ,, 0 ,,,,,,
BC HTab HWMax=71.05

Type RM Length L Ch R = 1 ,7023.681,34.39,33.41,33.55
BEGIN DESCRIPTION:
Stations 3398.04 - 3427.67 developed from survey information (copied from cross-section 6990.27) , and the remainder developed from LiDAR. The elevation of survey points adjusted to match the overall stream slope of approx. .0064 ft/ft.
Blocked obstruction in the far overbank at basin divide.
END DESCRIPTION:
XS GIS Cut Line= 6
     3077047.293    13847671.734     3075951.976    13844676.504
      3075754.93    13844500.989     3075648.473    13844417.708
     3075568.994     13844356.55     3074983.144    13843201.321
#Sta/Elev= 30
       0   68.16   62.21   68.14  108.99   71.38  142.82   71.52  293.89   69.04
 1461.32   68.93 1559.15   70.12 1828.67   69.37 1929.29    67.4 2045.04    69.8
 2436.26   67.97  2597.2   69.43 2675.16   67.11  2707.1   68.58 2994.59   67.09
 3079.48   68.44 3265.74   67.92 3305.99    69.3 3398.04   66.34 3405.75   62.45
  3405.9   62.35 3412.38   59.54 3421.75   64.44 3421.85    64.5 3461.42   67.97
 3737.21   69.52 4100.32    69.9 4156.34   68.23 4787.78    70.1 4983.84   69.21
#Mann= 3 ,-1 , 0
       0     .08       0  3405.9     .06       0 3421.75     .08       0
#XS Ineff= 4 ,-1
   -4.11 2048.37   69.81 2110.94  2530.2   69.59  2601.6 3303.57   69.31
 3738.42 4983.84   69.52
Permanent Ineff=
       F       F       F       F
#Block Obstruct= 2 , 0
                         4761.09           70.18
Bank Sta=3405.75,3421.85
XS Rating Curve= 0
Exp/Cntr=.5,.3

Type RM Length L Ch R = 1 ,6990.267,28.19,33.87,39.21
BEGIN DESCRIPTION:
Stations 3422.58 - 3452.2 developed from survey information, and the remainder developed from LiDAR
Blocked obstruction in the far overbank at basin divide.
END DESCRIPTION:
XS GIS Cut Line= 6
     3077083.109    13847671.487     3075993.661    13844708.756
     3075928.597    13844610.771     3075776.931    13844475.844
     3075611.137    13844346.905     3075024.024    13843203.445
#Sta/Elev= 30
       0    69.8   52.65   68.61  160.44   71.51  311.32   68.89  349.05   70.11
  806.76    68.7  846.34   69.98 1129.84   68.75 1716.26   70.01 1982.86   67.89
 2079.45   69.57 2532.81   69.56 2608.44   69.33 2676.65   67.05 2756.56   68.82
 2996.29   66.98 3126.37   68.54 3319.46   67.74 3339.59   69.09 3422.58   66.54
 3426.75   65.09 3434.47   59.77 3436.92   59.74 3448.98   65.57 3449.08   65.58
 3536.61   68.58 3788.48   69.49 4577.46   69.61 4678.02   68.15 4972.72   69.23
#Mann= 3 ,-1 , 0
       0     .08       0 3426.75     .06       0 3449.08     .08       0
#XS Ineff= 7 ,-1
   -2.07 1717.24   70.02 1748.35 2122.23   69.64 2127.96    2533   69.56
 2618.17  3340.8   69.09 3627.45 3729.19   69.08 3802.87    4066   69.52
 4087.05 4974.68   69.87
Permanent Ineff=
       F       F       F       F       F       F       F
#Block Obstruct= 2 , 0
                         4590.44           69.78
Bank Sta=3422.58,3448.98
XS Rating Curve= 0
Exp/Cntr=.5,.3

Type RM Length L Ch R = 1 ,6956.397,110.88,92.17,74.39
BEGIN DESCRIPTION:
Stations 3422.82 - 3451.43 developed from survey information (copied from cross-section 6990.27) , and the remainder developed from LiDAR. The elevation of survey points adjusted to match the overall stream slope of approx. .0064 ft/ft.
Blocked obstruction in the far overbank at basin divide.
END DESCRIPTION:
XS GIS Cut Line= 6
     3077098.827    13847671.378     3076021.759    13844724.701
     3075953.777    13844620.182     3075855.431    13844516.962
     3075630.831    13844213.822     3075115.885    13843208.217
#Sta/Elev= 30
       0   69.88   67.03   69.41  183.98   71.48  294.13   68.95  368.95   70.11
 1147.34   68.72 1716.39   69.98 1987.89    68.4 2044.22   69.52 2546.87    69.5
 2674.63   67.13 2754.48    68.9    2999   66.99 3134.03   68.49 3325.69   67.48
 3368.83   69.07 3423.32   66.15 3423.47    66.1 3434.31   59.56 3436.67   59.53
 3447.88    65.3 3448.13   65.33    3480   67.93 3548.52   68.95 3981.91   68.33
 4019.01   69.57  4051.1   68.08 4169.07   69.53 4337.59   67.76 4911.79   69.03
#Mann= 3 ,-1 , 0
       0     .08       0 3423.32     .06       0 3447.88     .08       0
#XS Ineff= 7 ,-1
   -2.83 1710.43   69.99 1755.39 2545.47   69.54 2615.85 3370.41   69.08
 3398.98 3413.59   67.82 3455.79 3478.51   67.81  3557.4 4002.25   69.01
 4016.26 4909.48   69.57
Permanent Ineff=
       F       F       F       F       F       F       F
#Block Obstruct= 2 , 0
                         4754.27           69.78
Bank Sta=3423.47,3448.13
XS Rating Curve= 0
Exp/Cntr=.5,.3

Type RM Length L Ch R = 3 ,6914.924,,,
BEGIN DESCRIPTION:
Structures 20 & 21 combined as one bridge - Hedwig Road
Downstream cross-section was surveyed and taken across the road, therefore, the road profile was allowed to be shown to drop off as it does. Surveyed top of road data was used over the main channel.
END DESCRIPTION:
Bridge Culvert--1,0,-1,-1, 0
Deck Dist Width WeirC Skew NumUp NumDn MinLoCord MaxHiCord MaxSubmerge Is_Ogee
13.5,48,2.6,0, 10, 9, , , .95, 0, 0,0,,
    3368 3374.52 3398.62  3404.6 3405.24 3425.98 3426.96 3442.06 3443.25 3486.73
      69   69.06   68.84   68.77   68.75   68.41   68.41   68.26   68.25    67.7
                                                   66.41   66.26
 3875.99 3884.78 3901.35  3928.1 3937.22 3938.63 3952.32 3962.97 4011.49
   69.15   69.06   69.29   68.95   68.96   68.96    68.9    68.9   68.93
                                   66.96   66.96    66.9
BR Coef=-1 , 0 , 0 ,, 0 ,,,.8,-1,,0,
WSPro=,,,, 1 ,,,, 0 ,,,, 0 ,,,,-1 ,-1 ,-1 , 0 , 0 , 0 , 0 , 0
BC Design=,, 0 ,, 0 ,,,,,,
BC HTab HWMax=71.48

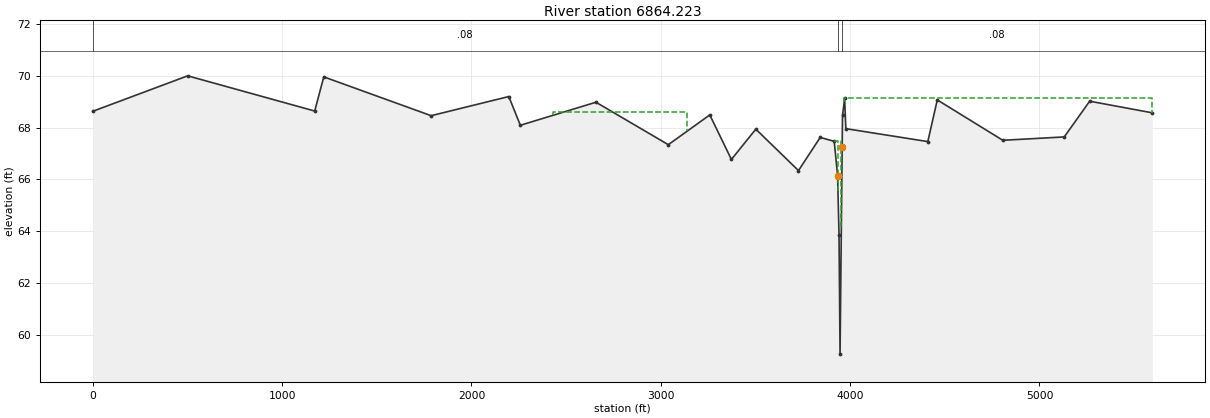
Type RM Length L Ch R = 1 ,6864.223,31.96,30.57,35.32
BEGIN DESCRIPTION:
Stations 3933.36 - 3972.99 developed from survey information (copied from cross-section 6833.65), and the remainder developed from LiDAR. The elevation of survey points adjusted to match the overall stream slope of approx. .0064 ft/ft.
END DESCRIPTION:
XS GIS Cut Line= 6
     3077390.065    13848015.107     3076426.224    13845379.717
     3076153.387    13844601.284     3076026.507    13844449.028
     3075882.344    13844441.743      3075161.13    13842987.833
#Sta/Elev= 30
       0   68.63  501.31      70 1172.12   68.64 1220.03   69.96 1787.11   68.46
  2197.2    69.2  2258.2   68.09 2657.49   68.98 3039.68   67.34 3258.72   68.49
 3372.85   66.77 3501.85   67.94 3727.14   66.34 3841.83   67.62 3915.84   67.47
 3933.56   66.17 3933.67   66.13 3941.25   63.87 3946.71   59.25 3957.73   67.18
 3957.85   67.26 3959.76   68.47 3970.92   69.13 3977.14   67.96 4410.15   67.46
 4460.22   69.07 4806.28   67.51 5130.81   67.64    5265   69.02  5596.5   68.57
#Mann= 3 ,-1 , 0
       0     .08       0 3933.56     .06       0 3957.73     .08       0
#XS Ineff= 4 ,-1
 2431.16  3137.4   68.62 3914.44 3935.99   67.49 3953.53 3959.44   67.48
 3968.34 5630.91   69.13
Permanent Ineff=
       F       F       F       F
Bank Sta=3933.67,3957.85
XS Rating Curve= 0
Exp/Cntr=.5,.3