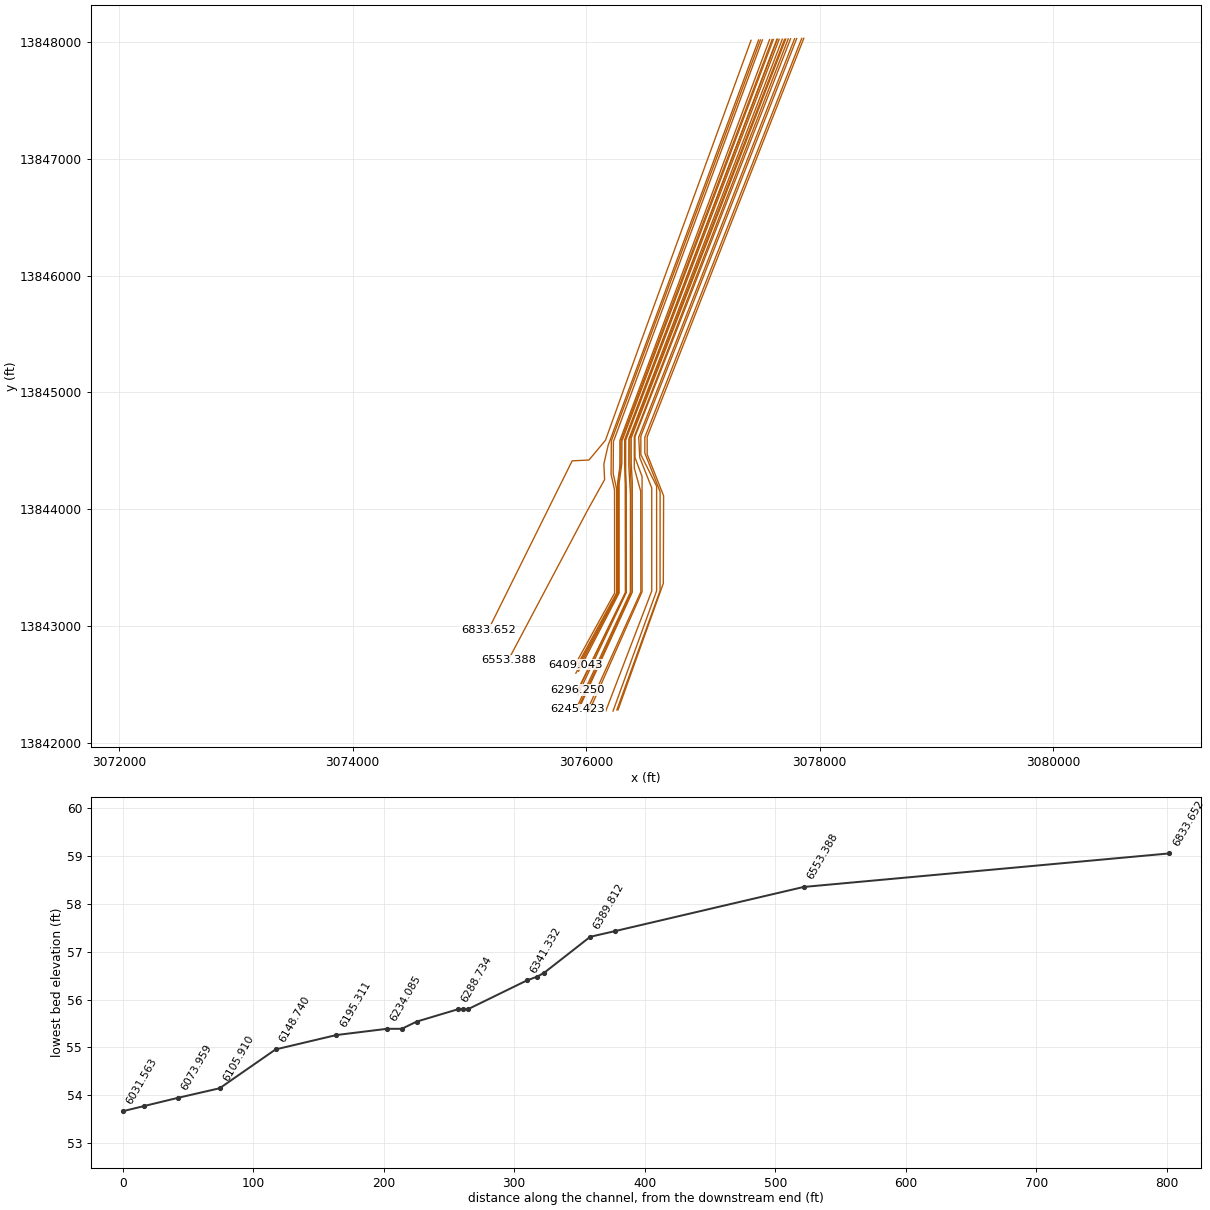
HEC-RAS study W141-00-00.prj: W141-00-00

--- W141-00-00.g01 (geometry) --- (continued)

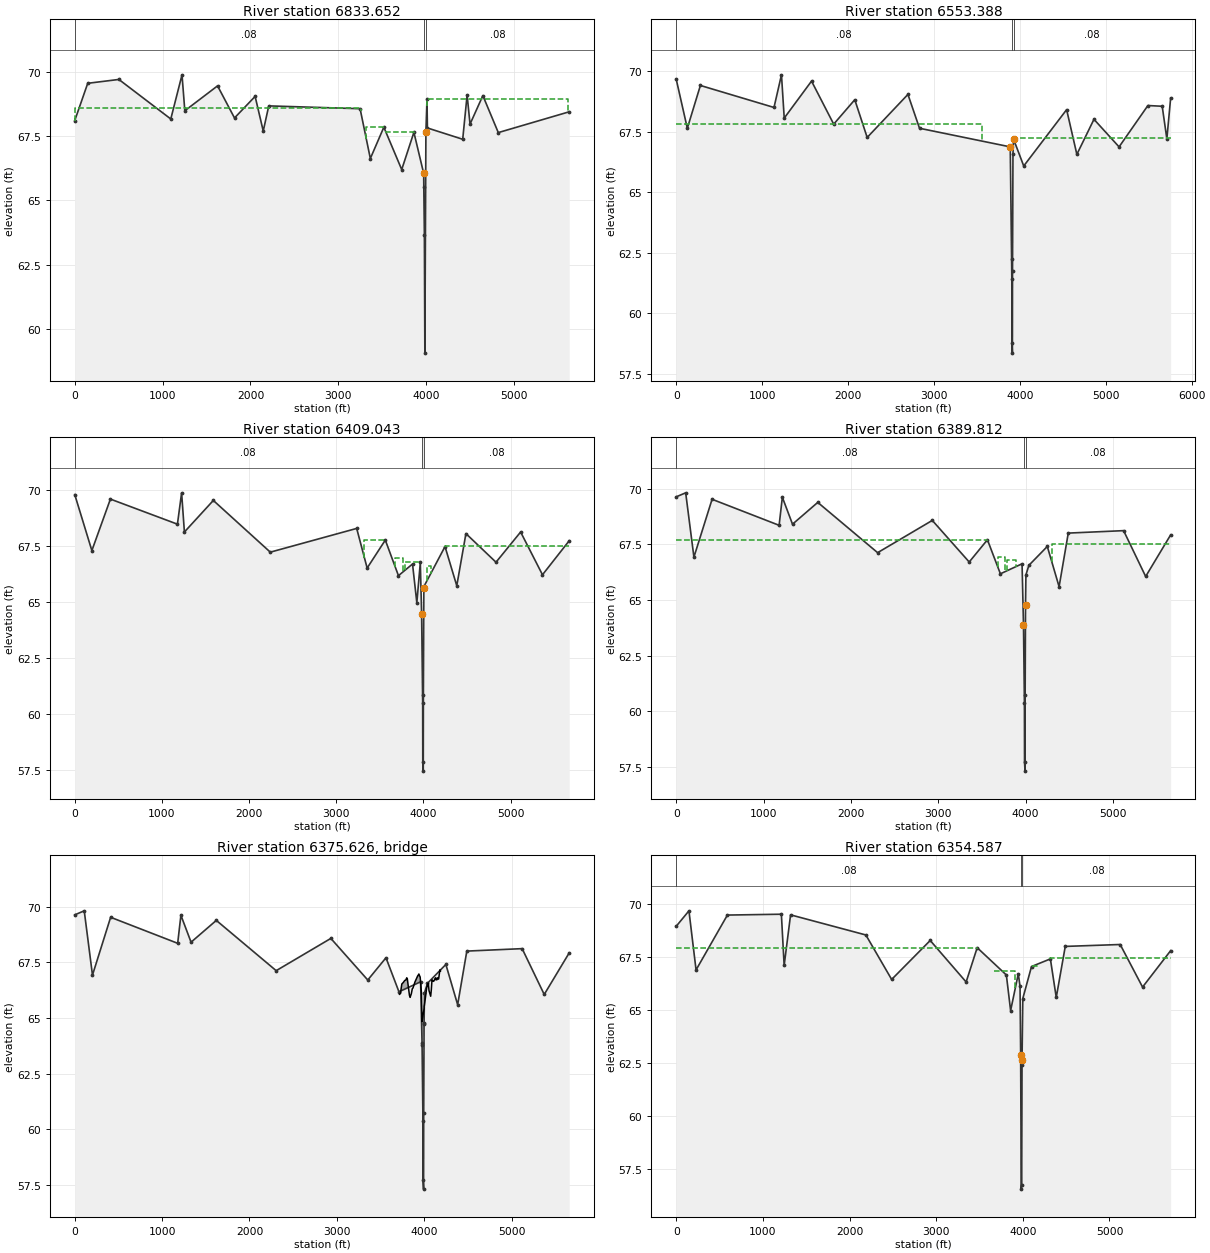
Type RM Length L Ch R = 1 ,6833.652,247.57,280.26,315.26
BEGIN DESCRIPTION:
Stations 3971.55 - 4011.19 developed from survey information, and the remainder developed from LiDAR
END DESCRIPTION:
XS GIS Cut Line= 6
     3077412.642    13848015.943      3076453.59    13845390.663
     3076165.914    13844590.146     3076024.289    13844420.197
     3075880.126    13844412.912     3075162.038     13842964.42
#Sta/Elev= 30
       0   68.11  147.65   69.56  502.13   69.71    1093   68.17 1220.76   69.89
  1252.7   68.49 1625.32   69.46 1818.23   68.21 2052.92   69.05 2145.33    67.7
 2208.21   68.68 3247.75   68.57 3364.34   66.63 3518.06   67.85 3721.46    66.2
 3860.25   67.65 3971.55   66.05 3972.98   65.51 3979.44   63.67 3984.91   59.05
 3996.84   67.64 3996.89   67.67 4009.06   68.93 4014.03   67.82 4415.74   67.38
 4465.81    69.1 4499.19   67.97  4645.1   69.08 4820.78   67.64 5627.92   68.45
#Mann= 3 ,-1 , 0
       0     .08       0 3972.98     .06       0 3996.84     .08       0
#XS Ineff= 4 ,-1
   -6.23 3252.68   68.58 3317.87  3514.2   67.85 3532.89 3856.99   67.65
 4010.27 5611.58   68.94
Permanent Ineff=
       F       F       F       F
Bank Sta=3971.55,3996.89
XS Rating Curve= 0
Exp/Cntr=.3,.1

Type RM Length L Ch R = 1 ,6553.388,134.92,144.35,134.54
BEGIN DESCRIPTION:
Stations 3879.99 - 3931.85 developed from survey information (copied from cross-section 6409.04), and the remainder developed from LiDAR. The elevation of survey points adjusted to match the overall stream slope of approx. .0064 ft/ft.
END DESCRIPTION:
XS GIS Cut Line= 6
     3077477.131    13848018.339     3076188.329    13844545.076
     3076151.935    13844386.649     3076158.186    13844252.024
      3076017.21    13843999.211      3075332.51    13842705.259
#Sta/Elev= 30
       0   69.68  129.35   67.65  281.57   69.42 1138.31   68.51 1225.35   69.86
 1257.34   68.07 1575.23    69.6  1833.2   67.82 2078.62   68.83 2222.94   67.27
 2697.24   69.05 2832.09   67.65 3888.23   66.88 3904.06   62.25 3906.58    61.4
 3907.84   58.77 3913.32   58.35 3914.67   61.75 3919.94   66.58 3926.51    67.2
 3926.62    67.2 4045.19   66.09 4544.63   68.42 4663.68   66.57  4862.7   68.02
 5155.02   66.88 5490.61   68.59 5657.09   68.56 5711.23   67.21  5755.4    68.9
#Mann= 3 ,-1 , 0
       0     .08       0 3904.06    .015       0 3926.51     .08       0
#XS Ineff= 2 , 0
         3559.94   67.82 3930.95           67.25
Permanent Ineff=
       F       F
Bank Sta=3888.23,3926.62
XS Rating Curve= 0
Exp/Cntr=.3,.1

Type RM Length L Ch R = 1 ,6409.043,19.24,19.23,19.19
BEGIN DESCRIPTION:
Stations 3964.43 - 4016.37 developed from survey information, and the remainder developed from LiDAR
END DESCRIPTION:
XS GIS Cut Line= 6
     3077493.044     13848018.93     3076215.879    13844584.269
     3076213.703    13844296.941     3076243.236    13844165.447
      3076243.84    13843280.075     3075905.613    13842666.484
#Sta/Elev= 30
       0   69.78  196.19   67.28   408.9   69.58 1177.88   68.46 1225.87   69.86
 1257.85   68.11 1589.73   69.52 2243.45   67.21 3234.47   68.27 3354.45    66.5
 3562.87   67.75 3713.54   66.16 3875.04   66.68 3924.49   64.95 3964.43   66.75
 3979.27   64.46 3979.44   64.43 3991.43   60.48 3992.71   57.85 3998.27   57.43
 3999.65   60.83 4004.96   65.63 4005.08   65.67 4247.73   67.46 4382.73   65.71
 4487.73   68.04 4832.73   66.76 5115.26   68.11 5366.02    66.2 5672.59   67.72
#Mann= 3 ,-1 , 0
       0     .08       0 3979.44    .015       0 4005.08     .08       0
#XS Ineff= 5 ,-1
 3323.71 3563.41   67.76 3678.65 3761.62   66.96 3793.89 3964.44   66.76
  4038.2 4084.29   66.58 4250.33 5690.25   67.47
Permanent Ineff=
       F       F       F       F       F
Bank Sta=3979.27,4004.96
XS Rating Curve= 0
Exp/Cntr=.5,.3

Type RM Length L Ch R = 1 ,6389.812,43.64,35.22,30.91
BEGIN DESCRIPTION:
Stations 3958.83 - 4011.51 developed from survey information (copied from cross-section 6409.04), and the remainder developed from LiDAR. The elevation of survey points adjusted to match the overall stream slope of approx. .0064 ft/ft.
END DESCRIPTION:
XS GIS Cut Line= 6
     3077510.347    13848019.573     3076233.554    13844577.569
     3076231.776    13844303.227     3076261.309    13844171.733
     3076261.473    13843281.545     3075931.864    13842676.328
#Sta/Elev= 30
       0   69.64  108.42   69.82  202.79   66.93  410.61   69.53 1177.96   68.36
 1215.07   69.62 1331.25   68.41 1620.32   69.39 2305.58   67.13 2931.34   68.58
 3353.92   66.71 3562.43   67.71 3710.86   66.18 3958.83   66.63 3975.26   63.88
 3975.49   63.81 3985.84   60.36 3987.11   57.73 3992.68   57.31 3994.06   60.71
 3998.52   64.75 3998.58    64.8 4003.04   66.13 4036.77   66.56  4247.8   67.41
  4382.8    65.6  4487.8   68.01 5121.14   68.12 5373.75   66.06  5659.7   67.93
#Mann= 3 ,-1 , 0
       0     .08       0 3975.49    .015       0 3998.52     .08       0
#XS Ineff= 4 ,-1
   -2.08 3554.45   67.71 3681.51 3766.49   66.92 3786.49 3891.47   66.79
 4300.23 5690.95   67.51
Permanent Ineff=
       F       F       F       F
Bank Sta=3975.26,3998.58
XS Rating Curve= 0
Exp/Cntr=.5,.3

Type RM Length L Ch R = 3 ,6375.626,,,
BEGIN DESCRIPTION:
Structure 18 - wooden walkway
END DESCRIPTION:
Bridge Culvert--1,0,-1,-1, 0
Deck Dist Width WeirC Skew NumUp NumDn MinLoCord MaxHiCord MaxSubmerge Is_Ogee
9.3,4,2.6,0, 55, 55, , , .95, 0, 0,0,,
 3717.74 3728.57 3733.85 3743.59 3760.64 3777.24 3789.17 3800.28 3806.87 3831.01
 3838.68 3848.69 3853.04 3863.71 3871.37 3893.74 3921.24 3922.57 3924.87 3938.79
  3949.2 3951.89  3953.8 3967.88 3968.82 3974.53 3974.87  3999.3 3999.37 4001.52
 4006.34 4012.71 4025.03  4028.9 4038.68 4039.31 4043.92 4046.46  4055.2 4073.99
 4081.66 4089.02 4095.78 4104.05  4109.9 4129.53 4134.11 4145.61 4149.14 4150.74
 4164.18 4166.37 4179.21 4180.48 4186.34
   66.07   66.11   66.27   66.53    66.6   66.69   66.71   66.81   66.76   66.02
   65.93   66.05    66.1   66.32   66.35   66.62   66.86   66.88   66.88   66.98
   66.88   66.86   66.84   66.17   66.14   64.91   64.84   65.44   65.54   65.56
    65.7   65.88   66.26   66.37    66.5   66.51   66.54   66.57   66.23   65.98
   66.28   66.72   66.69   66.65   66.66   66.81   66.72   66.72    66.8   66.81
   66.75   66.79   67.16   67.17   67.12
                                                                                
                                                                                
                                           63.91   63.84   64.44   64.54   64.56
    64.7
                                                                                
                                        
 3711.07  3721.9 3727.18 3736.92 3753.97 3770.57  3782.5 3793.61  3800.2 3824.34
 3832.01 3842.02 3846.37 3857.04  3864.7 3887.07 3914.57  3915.9  3918.2 3932.12
 3942.53 3945.22 3947.13 3961.21 3962.15 3967.72 3992.19 3992.23  3992.7 3994.85
 3999.67 4006.04 4018.36 4022.23 4032.01 4032.64 4037.25 4039.79 4048.53 4067.32
 4074.99 4082.35 4089.11 4097.38 4103.23 4122.86 4127.44 4138.94 4142.47 4144.07
 4157.51  4159.7 4172.54 4173.81 4179.67
   66.07   66.11   66.27   66.53    66.6   66.69   66.71   66.81   66.76   66.02
   65.93   66.05    66.1   66.32   66.35   66.62   66.86   66.88   66.88   66.98
   66.88   66.86   66.84   66.17   66.14   64.79   65.48   65.54   65.54   65.56
    65.7   65.88   66.26   66.37    66.5   66.51   66.54   66.57   66.23   65.98
   66.28   66.72   66.69   66.65   66.66   66.81   66.72   66.72    66.8   66.81
   66.75   66.79   67.16   67.17   67.12
                                                                                
                                                                                
                                           63.79   64.48   64.54   64.54   64.56
    64.7
                                                                                
                                        
BR Coef=-1 , 0 , 0 ,, 0 ,,,.8,-1,,0,
WSPro=,,,, 1 ,,,, 0 ,,,, 0 ,,,,-1 ,-1 ,-1 , 0 , 0 , 0 , 0 , 0
BC Design=,, 0 ,, 0 ,,,,,,
BC HTab HWMax=69.82

Type RM Length L Ch R = 1 ,6354.587,5.28,5.27,5.28
BEGIN DESCRIPTION:
Stations 3961.51 - 4009.99 developed from survey information, and the remainder developed from LiDAR
END DESCRIPTION:
XS GIS Cut Line= 6
     3077571.441    13848021.843     3076289.392    13844587.917
     3076288.821     13844363.11     3076269.588    13844222.674
     3076270.289    13843281.545      3075922.02    13842636.951
#Sta/Elev= 30
       0   68.97  147.02    69.7  229.13   66.91  590.79    69.5 1213.64   69.54
 1245.64   67.12 1319.78   69.51 2188.52   68.56 2486.25   66.46 2931.22    68.3
 3345.74   66.34 3473.32   67.96 3809.98   66.67 3859.08   64.99 3947.72   66.73
 3967.86   66.13 3974.83   62.89 3974.89   62.84 3981.86   56.56 3986.82   56.77
 3990.64    62.4 3990.87   62.66 3999.67   65.56 4100.16   67.07 4317.98   67.43
 4385.69   65.61 4489.69   68.02 5123.46   68.11 5381.75    66.1  5705.8   67.82
#Mann= 3 ,-1 , 0
       0     .08       0 3974.89    .015       0 3990.64     .08       0
#XS Ineff= 4 ,-1
       0 3468.49   67.95 3668.07 3909.39   66.86 4101.63 4191.61   67.08
 4311.24 5726.45   67.46
Permanent Ineff=
       F       F       F       F
Bank Sta=3974.83,3990.87
XS Rating Curve= 0
Exp/Cntr=.5,.3

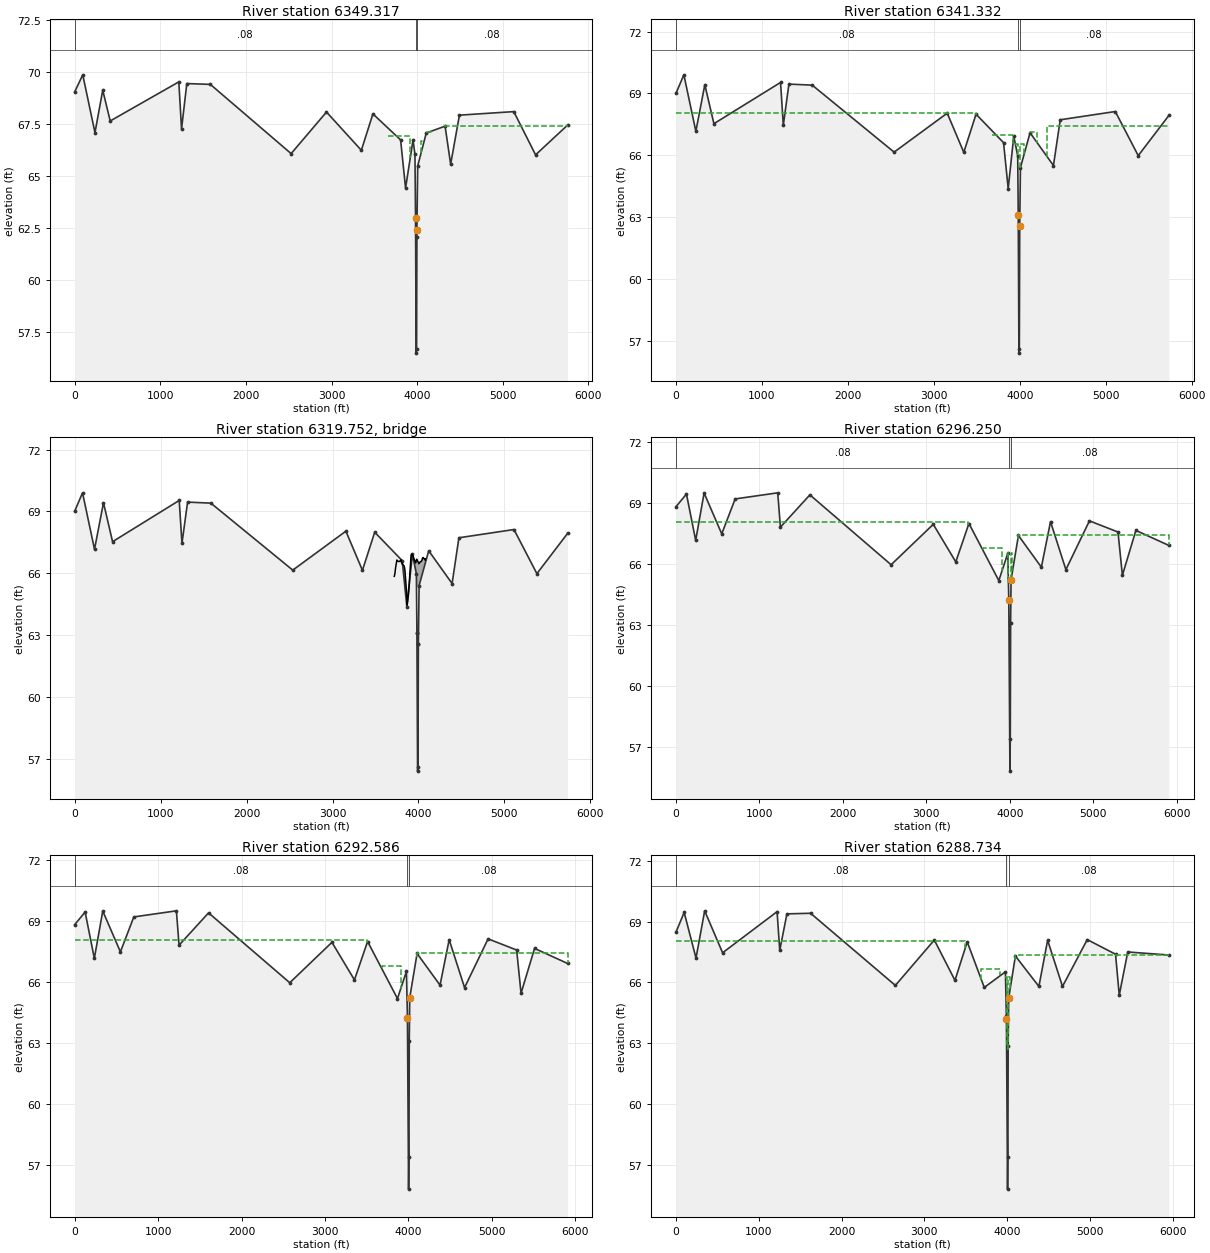
Type RM Length L Ch R = 1 ,6349.317,8,7.99,8
BEGIN DESCRIPTION:
Stations 3967.8 - 4016.34 developed from survey information (copied from cross-section 6354.59), and the remainder developed from LiDAR. The elevation of survey points adjusted to match the overall stream slope of approx. .0064 ft/ft.
END DESCRIPTION:
XS GIS Cut Line= 6
     3077593.608    13848022.666     3076297.869    13844584.267
     3076297.835    13844390.846     3076274.818     13844222.02
     3076275.672    13843281.631     3075912.176    13842594.294
#Sta/Elev= 30
       0   69.05   94.39   69.87  236.95   67.09  327.74   69.13  414.85   67.65
 1215.98   69.53 1248.03   67.27 1309.71   69.45  1584.5   69.41  2527.9   66.08
 2940.92   68.08 3347.99   66.24    3483   67.99  3806.5   66.74 3864.42   64.42
 3951.43   66.73 3974.15   66.05 3980.86   62.97 3988.15   56.48  3993.1   56.69
 3996.75   62.07 3996.98    62.4 4005.95   65.48 4105.98   67.07 4325.93    67.4
 4390.98   65.57 4493.53   67.93 5128.35    68.1 5382.87   66.02 5756.19   67.45
#Mann= 3 ,-1 , 0
       0     .08       0 3980.86    .015       0 3996.75     .08       0
#XS Ineff= 5 ,-1
       0 3484.19   67.98 3661.69 3919.83   66.91  4046.7 4078.97   66.67
 4111.24 4198.82    67.1 4316.26 5763.67   67.43
Permanent Ineff=
       F       F       F       F       F
Bank Sta=3980.86,3996.98
XS Rating Curve= 0
Exp/Cntr=.5,.3

Type RM Length L Ch R = 1 ,6341.332,40.51,45.08,47.78
BEGIN DESCRIPTION:
Stations 3969.57 - 4017.78 developed from survey information (copied from cross-section 6354.59), and the remainder developed from LiDAR. The elevation of survey points adjusted to match the overall stream slope of approx. .0064 ft/ft.
END DESCRIPTION:
XS GIS Cut Line= 6
     3077603.717    13848023.042     3076306.708    13844582.444
     3076305.535    13844388.177     3076282.755    13844221.116
     3076282.852    13843281.755     3075935.145    13842610.701
#Sta/Elev= 30
       0   69.01   91.27    69.9  230.73   67.16   335.1   69.42  440.77   67.53
 1216.27   69.53 1248.31   67.45 1313.62   69.45 1584.76    69.4 2537.74   66.15
 3155.66   68.04 3348.39   66.14 3491.05   67.99 3811.12   66.61 3865.11   64.38
 3929.94   66.92 3975.92   65.97 3982.15   63.12  3982.2   63.09 3989.92    56.4
 3994.87   56.61 3999.07   62.55 3999.18   62.59 4007.72    65.4 4119.52   67.09
 4391.66    65.5 4470.83   67.72 5111.49   68.12  5378.3   65.98 5734.99   67.93
#Mann= 3 ,-1 , 0
       0     .08       0 3982.15    .015       0 3999.07     .08       0
#XS Ineff= 6 ,-1
  -28.92 3488.64   68.03 3680.85 3920.81   66.98 3942.98 3976.03   66.55
 4007.95 4052.46   66.55 4119.03 4200.44   67.11 4320.29 5751.47   67.42
Permanent Ineff=
       F       F       F       F       F       F
Bank Sta=3982.2,3999.18
XS Rating Curve= 0
Exp/Cntr=.5,.3

Type RM Length L Ch R = 3 ,6319.752,,,
BEGIN DESCRIPTION:
Structure 17 - wood driveway
END DESCRIPTION:
Bridge Culvert--1,0,-1,-1, 0
Deck Dist Width WeirC Skew NumUp NumDn MinLoCord MaxHiCord MaxSubmerge Is_Ogee
15,12,2.6,0, 42, 48, , , .95, 0, 0,0,,
 3719.13 3726.37 3733.66 3748.87 3765.08 3778.88 3791.83 3796.08  3808.9 3832.21
 3837.16 3842.59 3864.54 3868.93  3873.6 3883.94 3893.63 3898.94 3904.61 3913.95
 3924.61 3933.17 3945.14 3955.02 3958.97 3966.68  3977.2 3979.43 4002.75 4003.25
 4003.28 4003.67 4009.67 4018.98 4027.19 4037.57 4040.56 4048.98 4055.33  4072.9
 4078.98 4081.95
   65.85   65.99   66.25   66.64   66.57   66.57   66.62   66.65   66.46   66.36
   66.29   66.15   64.93   64.46   64.61   64.97   65.51   65.92   66.27   66.86
   66.93   66.87   66.74   66.62   66.58    66.5   66.65   66.68   66.49   66.46
   66.46   66.46    66.5   66.55   66.55   66.61   66.63   66.75   66.76   66.67
   66.63    66.7
                                                                                
                                                                                
                                                    65.4   65.43   65.24   65.21
   65.21   65.21   65.25
                
 3725.61 3732.85 3740.14 3755.35 3771.56 3785.36 3798.31 3802.56 3815.38 3838.69
 3843.64 3849.07 3871.02 3875.41 3880.08 3890.42 3900.11 3905.42 3911.09 3920.43
 3931.09 3939.65 3951.62  3961.5 3965.45 3973.16 3983.68 3985.91 4009.23 4009.73
 4009.76 4010.15 4016.15 4025.46 4033.67 4044.05 4047.04 4055.46 4061.81 4079.38
 4085.46 4088.43 4100.46 4106.14 4115.47 4125.08 4135.69 4144.05
   65.85   65.99   66.25   66.64   66.57   66.57   66.62   66.65   66.46   66.36
   66.29   66.15   64.93   64.46   64.61   64.97   65.51   65.92   66.27   66.86
   66.93   66.87   66.74   66.62   66.58    66.5   66.65   66.68   66.49   66.46
   66.46   66.46    66.5   66.55   66.55   66.61   66.63   66.75   66.76   66.67
   66.63    66.7   66.79   66.94   67.16    67.3   67.24   67.18
                                                                                
                                                                                
                                                    65.4   65.43   65.24   65.21
   65.21   65.21   65.25
                                                                
BR Coef=-1 , 0 , 0 ,, 0 ,,,.8,-1,,0,
WSPro=,,,, 1 ,,,, 0 ,,,, 0 ,,,,-1 ,-1 ,-1 , 0 , 0 , 0 , 0 , 0
BC Design=,, 0 ,, 0 ,,,,,,
BC HTab HWMax=69.9

Type RM Length L Ch R = 1 ,6296.250,3.59,3.67,3.65
BEGIN DESCRIPTION:
Stations 3976.83 - 4022.61 developed from survey information, and the remainder developed from LiDAR
END DESCRIPTION:
XS GIS Cut Line= 6
     3077634.313    13848024.178     3076330.262    13844593.383
     3076330.025    13844389.165     3076335.019     13844219.68
     3076336.016     13843284.71     3075928.583    13842449.914
#Sta/Elev= 30
       0   68.82  125.12   69.44   235.6   67.16   336.6   69.49  548.07   67.48
  708.92    69.2 1219.12    69.5 1251.21   67.81 1604.71    69.4 2578.24   65.96
 3083.75   67.95 3353.42    66.1 3511.07   67.99 3869.27   65.18 3976.83   66.52
 3988.39   64.33 3988.81    64.2 4002.44    55.8 4006.71   57.38 4010.73   63.11
 4016.16   65.22 4104.28    67.4 4379.44   65.84    4489   68.08 4673.36   65.72
 4955.52   68.12 5297.95   67.57  5350.5   65.44 5512.52   67.65 5907.94   66.91
#Mann= 3 ,-1 , 0
       0     .08       0 3988.39     .06       0 4010.73     .08       0
#XS Ineff= 5 ,-1
       0 3505.56   68.06 3679.27 3907.54   66.76  3976.1 3984.38   66.52
 4016.32 4032.49   66.52 4097.76 5933.42   67.41
Permanent Ineff=
       F       F       F       F       F
Bank Sta=3988.81,4016.16
XS Rating Curve= 0
Exp/Cntr=.5,.3

Type RM Length L Ch R = 1 ,6292.586,3.79,3.85,3.81
BEGIN DESCRIPTION:
Stations 3976.83 - 4022.61 developed from survey information, and the remainder developed from LiDAR.
Section data copied from 6296.25
END DESCRIPTION:
XS GIS Cut Line= 6
     3077637.844    13848024.821     3076333.794    13844594.025
     3076333.557    13844389.807     3076338.551    13844220.322
     3076339.548    13843285.352     3075932.115    13842450.556
#Sta/Elev= 30
       0   68.82  125.12   69.44   235.6   67.16   336.6   69.49  548.07   67.48
  708.92    69.2 1219.12    69.5 1251.21   67.81 1604.71    69.4 2578.24   65.96
 3083.75   67.95 3353.42    66.1 3511.07   67.99 3869.27   65.18 3976.83   66.52
 3988.39   64.33 3988.81    64.2 4002.44    55.8 4006.71   57.38 4010.73   63.11
 4016.16   65.22 4104.28    67.4 4379.44   65.84    4489   68.08 4673.36   65.72
 4955.52   68.12 5297.95   67.57  5350.5   65.44 5512.52   67.65 5907.94   66.91
#Mann= 3 ,-1 , 0
       0     .08       0 3988.39     .06       0 4010.73     .08       0
#XS Ineff= 3 ,-1
       0 3505.56   68.06 3679.27 3907.54   66.76 4097.76 5933.42   67.41
Permanent Ineff=
       F       F       F
Bank Sta=3988.81,4016.16
XS Rating Curve= 0
Exp/Cntr=.5,.3

Type RM Length L Ch R = 1 ,6288.734,30.88,31.94,31.95
BEGIN DESCRIPTION:
Stations 3979.39 - 4025.2 developed from survey information (copied from cross-section 6296.25), and the remainder developed from LiDAR. The elevation of survey points adjusted to match the overall stream slope of approx. .0064 ft/ft.
END DESCRIPTION:
XS GIS Cut Line= 6
     3077653.734      13848024.9      3076338.63    13844589.741
      3076338.79    13844314.014     3076343.761    13844179.777
     3076343.981    13843285.094     3075928.583    13842407.256
#Sta/Elev= 30
       0   68.48   98.33   69.45  241.47    67.2  346.05   69.53  562.58   67.46
 1220.86   69.49 1252.97   67.58 1339.73   69.38 1625.67   69.41 2649.79   65.85
  3120.3   68.09 3369.77    66.1 3517.94      68 3723.74   65.75 3979.39   66.52
 3990.98   64.32  3991.4   64.19    4005    55.8 4009.26   57.38 4012.65   62.86
 4018.71   65.22 4099.97    67.3 4383.83    65.8 4489.31   68.08 4668.83    65.8
 4967.87   68.11 5309.58   67.39 5354.64   65.37 5457.36    67.5  5954.2   67.35
#Mann= 3 ,-1 , 0
       0     .08       0 3990.98     .06       0 4018.71     .08       0
#XS Ineff= 5 ,-1
       0 3493.42   68.02 3688.71 3919.84   66.68 3979.91 3993.49   66.28
 4012.52 4034.13   66.29 4093.19 5965.33   67.36
Permanent Ineff=
       F       F       F       F       F
Bank Sta=3991.4,4018.71
XS Rating Curve= 0
Exp/Cntr=.5,.3

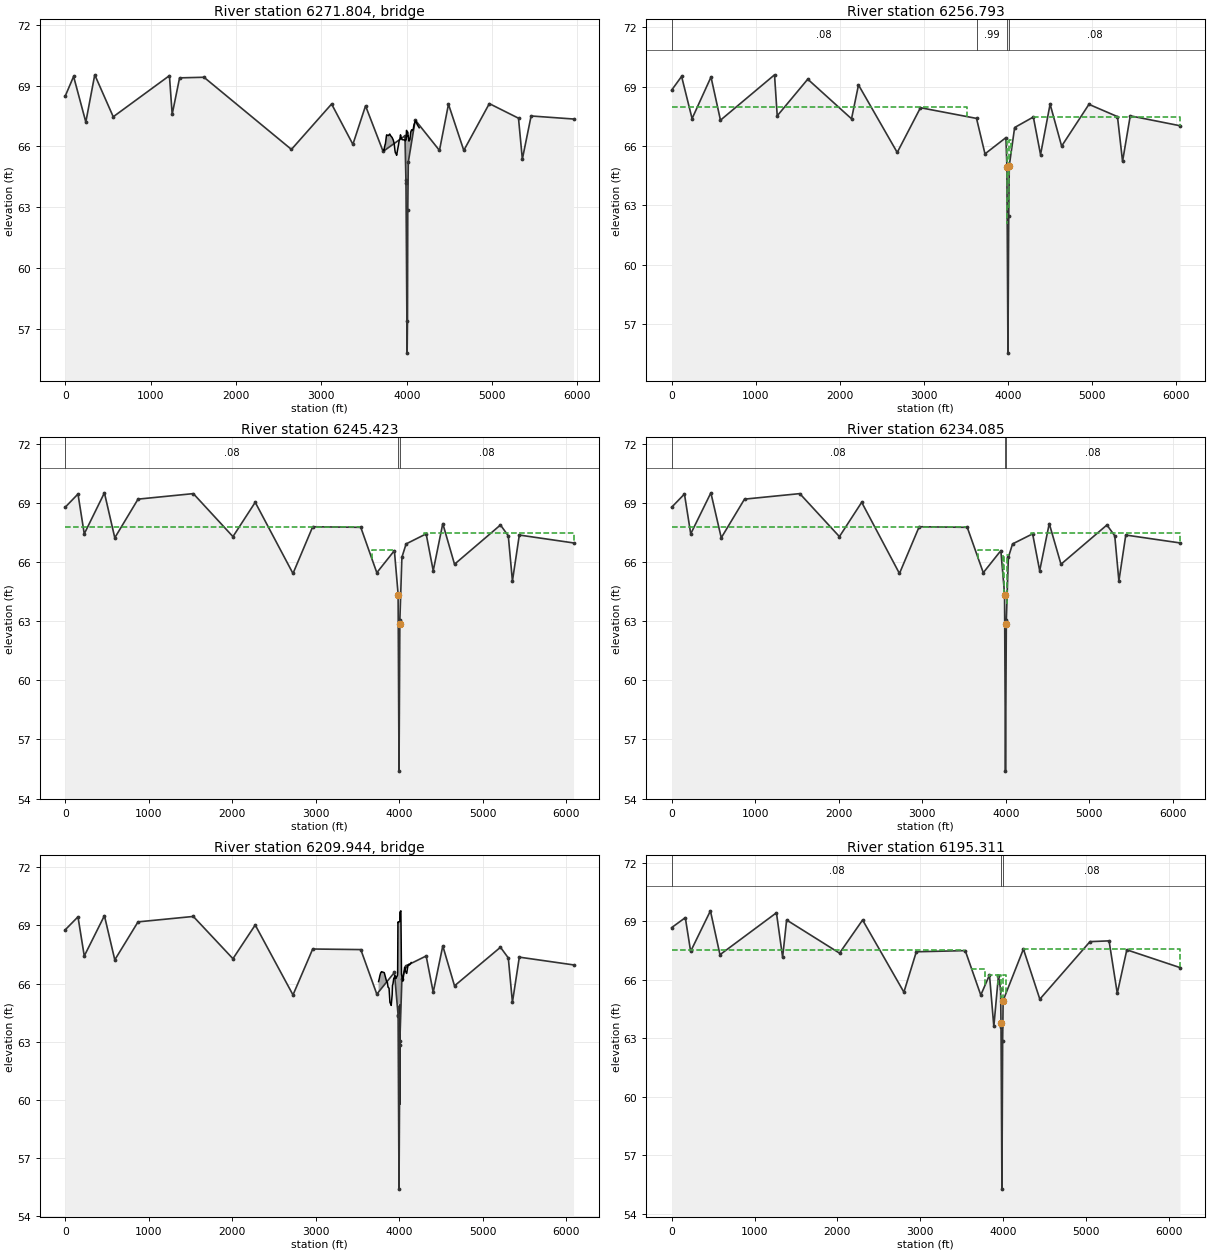
Type RM Length L Ch R = 3 ,6271.804,,,
BEGIN DESCRIPTION:
Structure 16 - wood drive
END DESCRIPTION:
Bridge Culvert--1,0,-1,-1, 0
Deck Dist Width WeirC Skew NumUp NumDn MinLoCord MaxHiCord MaxSubmerge Is_Ogee
11.5,11.2,2.6,0, 53, 46, , , .95, 0, 0,0,,
 3728.17  3732.4 3733.57 3747.41 3750.08 3762.41  3765.4 3783.24 3801.78 3807.42
 3828.86 3841.97 3852.43 3862.46 3867.43  3872.6 3882.43 3887.92 3897.44 3903.23
 3912.44 3918.55 3927.44  3938.2 3946.61 3954.18 3980.27 3983.94 3987.47 3990.16
 3991.79 3993.46 3997.37 4013.91 4015.64  4016.9 4017.49 4022.34 4027.03  4032.5
 4037.58 4046.61 4047.51 4058.21 4066.53 4077.53 4084.24 4101.41 4107.55 4120.56
 4122.56 4125.31 4146.61
   65.83   65.79   65.83    66.1   66.11   66.52   66.57   66.53   66.61   66.55
   66.44   66.32   66.16    65.8   65.68   65.66   65.56    65.7   65.93   66.05
    66.3   66.33   66.57   66.39   66.33   66.33   66.31   66.27   66.33   66.33
   66.33   66.33   66.79   66.69   66.49    66.5    66.5   66.38   66.26    66.3
   66.34   66.67   66.71   66.82   66.78   66.87   67.05   67.25   67.27    67.1
   67.09   67.06   66.92
                                                                                
                                                                                
                                                                           62.08
   62.08   62.08   62.54   62.44   62.24   62.25   62.25   62.13
                                                                                
                        
 3793.48 3799.12 3820.56 3833.67 3844.13 3854.16 3859.13  3864.3 3874.13 3879.62
 3889.14 3894.93 3904.14 3910.25 3919.14  3929.9 3938.31 3945.88 3971.97 3975.64
 3979.17 3981.86 3983.49 3985.16 3986.51 4004.87 4005.61 4007.34  4008.6 4009.19
 4014.04 4018.73  4024.2 4029.28 4038.31 4039.21 4049.91 4058.23 4069.23 4075.94
 4093.11 4099.25 4112.26 4114.26 4117.01 4138.31
   66.55   66.55   66.44   66.32   66.16    65.8   65.68   65.66   65.56    65.7
   65.93   66.05    66.3   66.33   66.57   66.39   66.33   66.33   66.31   66.27
   66.33   66.33   66.33   66.33   66.84   66.91   66.69   66.49    66.5    66.5
   66.38   66.26    66.3   66.34   66.67   66.71   66.82   66.78   66.87   67.05
   67.25   67.27    67.1   67.09   67.06   66.92
                                                                                
                                                                                
           62.08   62.08   62.08   62.59   62.66   62.44   62.24   62.25   62.25
   63.13
                                                
BR Coef=-1 , 0 , 0 ,, 0 ,,,.8,-1,,0,
WSPro=,,,, 1 ,,,, 0 ,,,, 0 ,,,,-1 ,-1 ,-1 , 0 , 0 , 0 , 0 , 0
BC Design=,, 0 ,, 0 ,,,,,,
BC HTab HWMax=69.53

Type RM Length L Ch R = 1 ,6256.793,11.2,11.37,11.25
BEGIN DESCRIPTION:
Stations 3974.1 - 4027.29 developed from survey information (copied from cross-section 6234.09), and the remainder developed from LiDAR. The elevation of survey points adjusted to match the overall stream slope of approx. .0064 ft/ft. 0.99 mannings n added to simulate ineffective flow area. Utilizing ineffective flow option for this area was causing calculation instability.
END DESCRIPTION:
XS GIS Cut Line= 6
     3077680.716    13848025.902     3076365.874    13844599.581
     3076365.618     13844366.42     3076379.674    13844127.205
     3076379.199    13843286.998     3075931.864    13842325.222
#Sta/Elev= 30
       0   68.82  117.95   69.51  242.71   67.38  467.65   69.48  580.11    67.3
 1222.77   69.59 1254.91   67.52 1617.86   69.37 2138.38   67.37 2221.15   69.08
 2681.69   65.67 2957.96   67.93 3624.44   67.39 3725.22    65.6  3974.1   66.42
 3985.12   65.02 3985.43   64.93 3998.11   55.54 4007.37   62.45 4014.03   65.01
 4077.59   66.93 4300.16   67.46 4385.64   65.56 4499.16   68.11 4636.38   65.99
 4961.01    68.1 5300.23   67.48 5360.79   65.22 5452.16   67.52 6043.65   67.02
#Mann= 4 ,-1 , 0
       0     .08       0 3624.44     .99       0 3985.12     .06       0
 4007.37     .08       0
#XS Ineff= 4 ,-1
       0 3515.75   67.99 3975.52  3989.3   66.27 4008.48 4034.01   66.29
 4294.27 6059.87   67.47
Permanent Ineff=
       F       F       F       F
Bank Sta=3985.43,4014.03
XS Rating Curve= 0
Exp/Cntr=.5,.3

Type RM Length L Ch R = 1 ,6245.423,11.15,11.34,11.38
BEGIN DESCRIPTION:
Stations 3972.16 - 4025.35 developed from survey information, and the remainder developed from LiDAR.
Section data copied from cross-section 6234.085
END DESCRIPTION:
XS GIS Cut Line= 6
     3077699.434    13848023.305     3076375.106    13844605.407
     3076375.445    13844387.455     3076384.562    13844230.528
     3076384.624    13843284.257     3075927.671    13842285.434
#Sta/Elev= 30
       0   68.77     153   69.44  228.11   67.42   469.4    69.5  593.59   67.22
  871.85   69.18 1533.62   69.46 2008.08   67.28 2274.75   69.02 2726.87   65.41
 2962.83   67.78 3538.52   67.75  3730.3   65.45 3940.64   66.57  3984.9   64.38
 3985.14   64.31 3996.17   55.39 4006.07   62.84 4006.32   63.05 4030.54   66.23
 4080.97   66.91    4321   67.42 4405.56   65.55 4520.12   67.94 4660.56   65.88
  5210.6   67.87 5304.33   67.32 5353.82   65.03  5436.3   67.36  6085.3   66.96
#Mann= 3 ,-1 , 0
       0     .08       0  3984.9     .06       0 4006.32     .08       0
#XS Ineff= 3 ,-1
       0 3524.91   67.77 3672.62  3930.3   66.62 4296.11 6099.88   67.48
Permanent Ineff=
       F       F       F
Bank Sta=3985.14,4006.07
XS Rating Curve= 0
Exp/Cntr=.5,.3

Type RM Length L Ch R = 1 ,6234.085,34.27,38.77,42.47
BEGIN DESCRIPTION:
Stations 3972.16 - 4025.35 developed from survey information, and the remainder developed from LiDAR
END DESCRIPTION:
XS GIS Cut Line= 6
      3077710.19    13848026.997     3076385.862    13844609.099
     3076386.202    13844391.148     3076395.318     13844234.22
     3076395.381     13843287.95     3075938.427    13842289.127
#Sta/Elev= 30
       0   68.77     153   69.44  228.11   67.42   469.4    69.5  593.59   67.22
  871.85   69.18 1533.62   69.46 2008.08   67.28 2274.75   69.02 2726.87   65.41
 2962.83   67.78 3538.52   67.75  3730.3   65.45 3940.64   66.57  3984.9   64.38
 3985.14   64.31 3996.17   55.39 4006.07   62.84 4006.32   63.05 4030.54   66.23
 4080.97   66.91    4321   67.42 4405.56   65.55 4520.12   67.94 4660.56   65.88
  5210.6   67.87 5304.33   67.32 5353.82   65.03  5436.3   67.36  6085.3   66.96
#Mann= 3 ,-1 , 0
       0     .08       0  3984.9     .06       0 4006.32     .08       0
#XS Ineff= 5 ,-1
       0 3524.91   67.77 3672.62  3930.3   66.62 3967.81 3982.67   66.33
 4012.39 4043.71   66.33 4296.11 6099.88   67.48
Permanent Ineff=
       F       F       F       F       F
Bank Sta=3985.14,4006.07
XS Rating Curve= 0
Exp/Cntr=.5,.3

Type RM Length L Ch R = 3 ,6209.944,,,
BEGIN DESCRIPTION:
Structure 15 - wood walk
END DESCRIPTION:
Bridge Culvert--1,0,-1,-1, 0
Deck Dist Width WeirC Skew NumUp NumDn MinLoCord MaxHiCord MaxSubmerge Is_Ogee
19.2,5.6,2.6,0, 49, 43, , , .95, 0, 0,0,,
 3751.55 3761.31 3766.55 3776.05 3781.56 3787.26 3819.47 3848.35  3852.5 3856.57
 3864.49 3868.58 3876.99 3887.08 3899.33  3902.5 3914.33 3917.92 3923.76 3933.34
 3939.23 3948.77 3958.02 3961.78 3976.18 3977.52 3979.61 3983.06 3984.44 4005.51
 4005.83 4011.53 4012.86 4018.53 4025.88 4026.36 4028.38  4041.3 4042.08 4045.36
  4063.7 4072.15 4085.89  4088.6 4102.99 4113.49 4118.41 4125.94 4142.08
    66.1   66.28    66.4   66.54   66.58   66.61   66.56   66.09   66.06   66.06
   65.81    65.8   65.75   65.03   64.91   64.87   65.43    65.9   65.98   66.27
   66.26   66.41   66.26   66.29   66.41   66.42   66.55   69.17   69.15    69.2
   69.67   69.71   69.72   69.75   66.47   66.46   66.42   66.12   66.14   66.24
   66.84   66.65   66.52   66.53   66.95   66.99   66.95   66.98   67.08
                                                                                
                                                                                
                                   62.16   62.17    62.3   64.92    64.9   64.95
   64.95   64.95
                                                                        
 3836.22 3840.37 3844.44 3852.36 3856.45 3864.86 3874.95  3887.2 3890.37  3902.2
 3905.79 3911.63 3921.21  3927.1 3936.64 3945.89 3949.65 3964.05 3965.39 3967.48
 3970.13 3974.54    3995 3995.21  3999.4 4001.68 4005.75 4008.17 4013.75 4014.23
 4016.25 4029.17 4029.95 4033.23 4051.57 4060.02 4073.76 4076.47 4090.86 4101.36
 4106.28 4113.81 4129.95
   66.09   66.06   66.06   65.81    65.8   65.75   65.03   64.91   64.87   65.43
    65.9   65.98   66.27   66.26   66.41   66.26   66.29   66.41   66.42   66.55
   69.13   69.05   69.09   69.72   69.73   69.73   69.62   69.59   66.47   66.46
   66.42   66.12   66.14   66.24   66.84   66.65   66.52   66.53   66.95   66.99
   66.95   66.98   67.05
                                                                                
                                                           62.16   62.17    62.3
   64.88    64.8   64.84   64.84   64.84
                                                                                
                        
Pier Skew, UpSta & Num, DnSta & Num=  ,3984.75, 2 ,3974.54, 2 , 0 , 0 , 0 ,,
     .65     .65
   63.23   65.46
     .65     .65
   63.23   65.46
Pier Skew, UpSta & Num, DnSta & Num=  ,4002.02, 2 ,3991.86, 2 , 0 , 0 , 0 ,,
     .65     .65
   60.74   65.46
     .65     .65
   60.74   65.46
BR Coef= 1 , 1 , 1 ,1.25, 0 ,,,.8,-1,2,0,
WSPro=,,,, 1 ,,,, 0 ,,,, 0 ,,,,-1 ,-1 ,-1 , 0 , 0 , 0 , 0 , 0
BC Design=,, 0 ,, 0 ,,,,,,
BC HTab HWMax=69.54

Type RM Length L Ch R = 1 ,6195.311,44.69,46.57,47.89
BEGIN DESCRIPTION:
Stations 3964.04 - 4012.02 developed from survey information, and the remainder developed from LiDAR
END DESCRIPTION:
XS GIS Cut Line= 6
     3077731.117    13848027.775     3076412.514    13844620.092
     3076412.621    13844350.918     3076467.704    13844151.515
     3076468.672    13843290.805     3075997.491     13842249.75
#Sta/Elev= 30
       0   68.67  164.56   69.18   228.9   67.45  467.52   69.53  582.74   67.28
 1264.09   69.43 1338.68   67.15 1386.93   69.06 2025.26   67.36 2303.71   69.06
 2802.02   65.36 2951.95   67.43 3542.17   67.49  3729.7   65.21  3834.7   66.24
 3887.07    63.6 3942.54    66.2 3968.89    65.5 3973.45   63.76 3973.88   63.56
 3984.91   55.26 3993.44   62.88 3999.39   64.93 4244.11   67.57 4442.17      65
  5047.2   67.95  5277.7   67.99 5376.49    65.3 5491.75   67.53 6133.38   66.62
#Mann= 3 ,-1 , 0
       0     .08       0 3973.88     .06       0 3993.44     .08       0
#XS Ineff= 6 ,-1
       0 3531.21    67.5 3614.71 3784.38   66.56 3826.79 3932.83   66.22
 3941.82 3970.06   66.24 3999.76 4031.16   66.24  4242.9 6130.45   67.59
Permanent Ineff=
       F       F       F       F       F       F
Bank Sta=3973.45,3999.39
XS Rating Curve= 0
Exp/Cntr=.5,.3

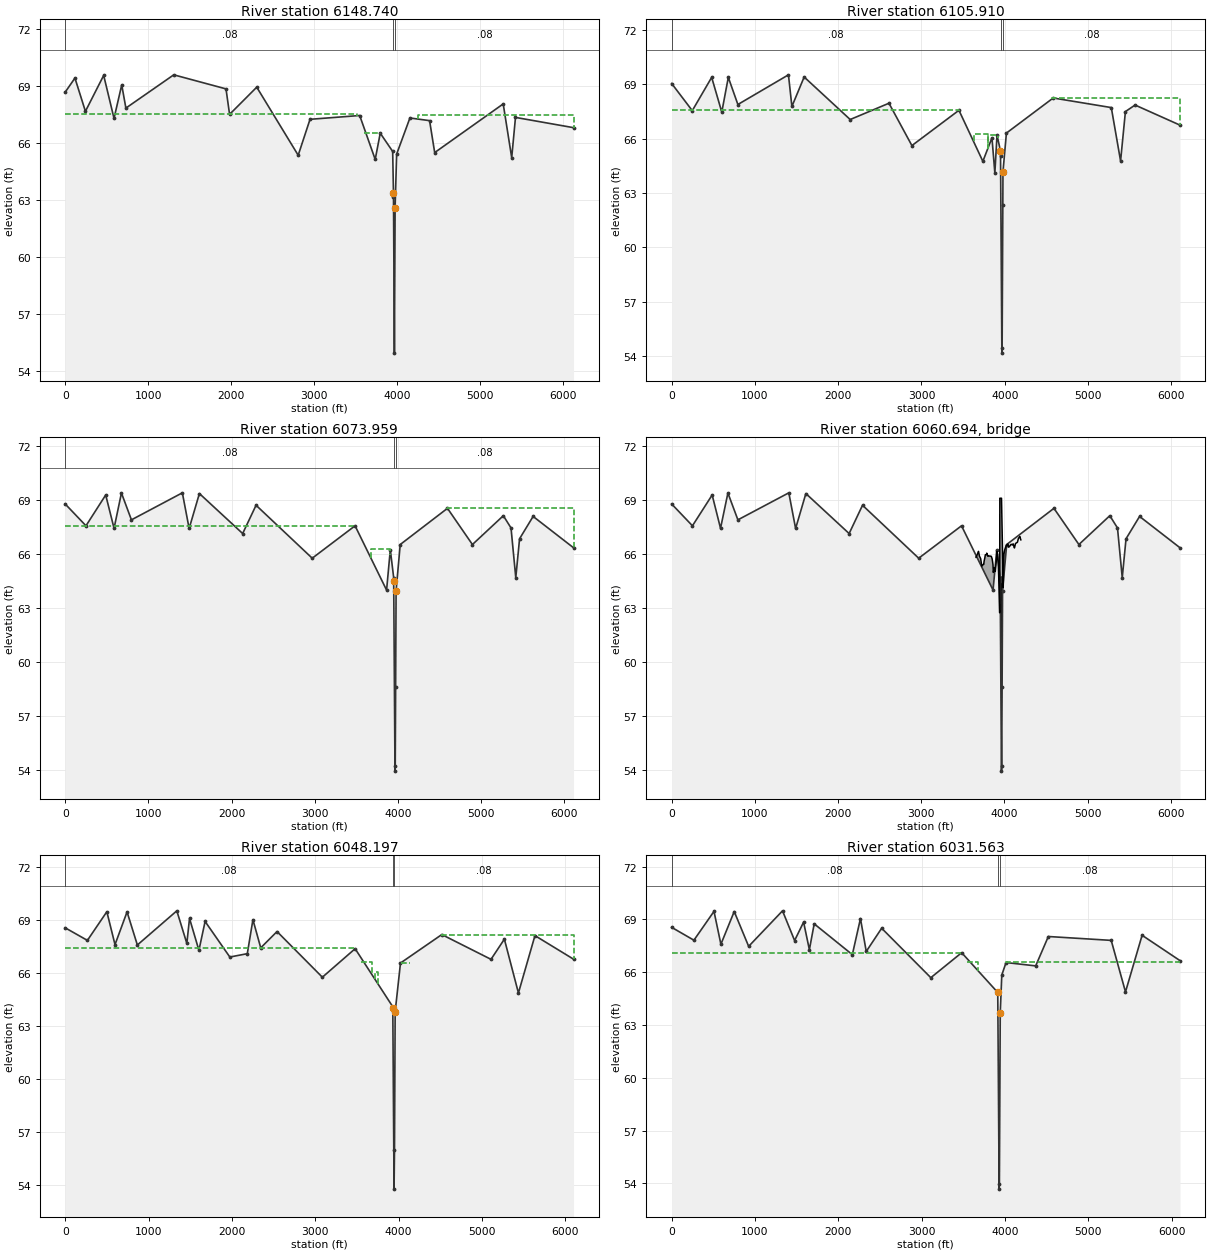
Type RM Length L Ch R = 1 ,6148.740,41.12,42.83,46.46
BEGIN DESCRIPTION:
Stations 3945.27 - 3993.06 developed from survey information (copied from cross-section 6195.31), and the remainder developed from LiDAR. The elevation of survey points adjusted to match the overall stream slope of approx. .0064 ft/ft.
END DESCRIPTION:
XS GIS Cut Line= 6
     3077751.175     13848028.52     3076418.431    13844619.791
     3076418.574    13844441.672     3076479.171    13844279.098
     3076479.142    13843291.757     3076023.742    13842262.876
#Sta/Elev= 30
       0   68.69  117.27   69.43  243.51   67.68   463.5   69.57  588.14   67.31
  680.97   69.07  731.14   67.85 1307.85    69.6 1937.22   68.86 1980.31   67.52
 2307.65   68.95 2806.93   65.37 2949.51   67.26 3547.79   67.46 3734.77   65.15
  3795.5   66.53 3945.27   65.57  3954.9   63.36 3955.14   63.19 3966.06   54.96
 3974.56   62.58  3974.8   62.67 3993.06   65.43 4152.98   67.33 4389.84   67.19
 4451.42   65.51 5276.92   68.07 5379.25   65.24 5424.74   67.36 6124.13   66.82
#Mann= 3 ,-1 , 0
       0     .08       0 3955.14     .06       0  3974.8     .08       0
#XS Ineff= 3 ,-1
       0 3511.51   67.54  3604.3 3798.35   66.55 4253.05 6138.18   67.47
Permanent Ineff=
       F       F       F
Bank Sta=3954.9,3974.56
XS Rating Curve= 0
Exp/Cntr=.3,.1

Type RM Length L Ch R = 1 ,6105.910,30.78,31.95,33.8
BEGIN DESCRIPTION:
Stations 3947.23 - 3991.32 developed from survey information, and the remainder developed from LiDAR
END DESCRIPTION:
XS GIS Cut Line= 6
       3077785.8    13848029.806     3076450.265    13844614.932
     3076459.504    13844440.569     3076561.906    13844181.132
     3076561.952    13843297.468     3076168.122    13842269.439
#Sta/Elev= 30
       0   69.05  247.51   67.55  480.46   69.39  601.85   67.47   680.2   69.39
  795.12   67.89 1402.58   69.53 1443.77   67.78 1591.13   69.41 2143.87   67.06
 2609.57   67.96 2885.17   65.62 3450.15   67.57 3737.38   64.75 3846.73   66.05
 3881.43    64.1 3907.41    66.2  3949.1   65.32 3949.65   65.04 3965.73   54.15
 3968.72   54.45 3977.06   62.33 3978.96   64.17 4020.15   66.31 4582.31   68.25
 5280.01   67.72 5391.41   64.77 5449.48    67.5 5565.62   67.86 6105.02   66.75
#Mann= 3 ,-1 , 0
       0     .08       0 3949.65     .06       0 3977.06     .08       0
#XS Ineff= 4 ,-1
       0 3456.44    67.6 3625.31 3796.49   66.27 3796.49 3916.32   66.21
  4571.1 6154.54   68.25
Permanent Ineff=
       F       F       F       F
Bank Sta=3949.1,3978.96
XS Rating Curve= 0
Exp/Cntr=.5,.3

Type RM Length L Ch R = 1 ,6073.959,28.19,25.76,25.34
BEGIN DESCRIPTION:
Stations 3946.13 - 3990.05 developed from survey information (copied from cross-section 6105.91), and the remainder developed from LiDAR. The elevation of survey points adjusted to match the overall stream slope of approx. .0064 ft/ft.
END DESCRIPTION:
XS GIS Cut Line= 6
     3077803.661     13848030.47     3076468.672    13844624.646
     3076468.672    13844466.324     3076603.897    13844196.511
     3076603.833    13843299.372     3076230.468    13842269.439
#Sta/Elev= 30
       0   68.78  249.69   67.57  486.77   69.28  587.27   67.43  676.04   69.39
  796.07    67.9  1408.3    69.4  1489.9   67.42 1613.21   69.36  2133.3   67.14
 2294.41   68.71  2969.6   65.77 3484.51   67.57 3863.48      64 3908.28   66.24
 3948.74   64.69 3948.99   64.51 3964.56   53.95 3967.54   54.25 3972.27   58.64
 3977.74   63.97 4027.48   66.53 4595.45   68.54 4895.45   66.53 5267.08   68.13
  5359.4   67.45 5416.62   64.69  5462.2   66.85 5625.01   68.09  6110.9   66.35
#Mann= 3 ,-1 , 0
       0     .08       0 3948.74     .06       0 3972.27     .08       0
#XS Ineff= 4 ,-1
       0 3468.87   67.55 3676.56  3902.4   66.26 4203.89 4297.51   66.96
 4586.18  6115.3   68.54
Permanent Ineff=
       F       F       F       F
Bank Sta=3948.99,3977.74
XS Rating Curve= 0
Exp/Cntr=.5,.3

Type RM Length L Ch R = 3 ,6060.694,,,
BEGIN DESCRIPTION:
Structure 14 - end of hedwig green
END DESCRIPTION:
Bridge Culvert--1,0,-1,-1, 0
Deck Dist Width WeirC Skew NumUp NumDn MinLoCord MaxHiCord MaxSubmerge Is_Ogee
8,4.7,2.6,0, 65, 66, , , .95, 0, 0,0,,
 3659.24 3659.29 3684.35 3688.51 3692.36 3699.27 3714.42 3728.25  3744.5 3751.77
 3755.65 3764.69 3770.73 3783.71  3785.8 3787.69 3800.87 3803.14 3823.33  3840.4
  3843.7 3852.86  3862.6 3866.84 3877.61 3889.97 3906.02 3910.96 3918.57 3927.08
 3932.55 3936.24  3943.2 3944.86 3965.18 3970.36 3985.76 3991.56 3994.08 4000.49
 4003.79 4005.64 4012.39 4023.82 4028.76 4039.95 4041.22 4051.87 4065.85 4072.22
 4076.51 4081.93 4100.76 4104.49 4119.31 4120.63 4122.64 4132.75 4146.04 4155.86
 4169.03 4178.97 4185.17 4190.53 4197.51
   65.82   65.82    66.1   66.15   66.07   65.89   65.75   65.33   65.42   65.43
    65.6   65.79   65.96   65.97      66   66.05   65.88    65.9   65.89   65.88
   65.86   65.73   65.42   64.98   65.24   65.04   65.78   66.15   65.98   65.46
   64.57   63.97   62.74    69.1    69.1   67.85   64.13   65.72   65.99   66.16
   66.23   66.26   66.35    66.5    66.5   66.55   66.53   66.38   66.45   66.48
   66.53   66.54   66.51   66.57   66.35   66.34   66.37   66.58   66.63   66.65
   66.88   66.93   66.98   66.89   66.79
                                                                                
                                                                                
                                                                                
                            64.8    64.8   63.56
                                                                                
                                                                                
                                        
 3639.35  3639.4 3664.46 3668.62 3672.47 3679.38 3694.53 3708.36 3724.61 3731.88
 3735.76  3744.8 3750.84 3763.82 3765.91  3767.8 3780.98 3783.25 3803.44 3820.51
 3823.81 3832.97 3842.71 3846.95 3857.72 3870.08 3886.13 3891.07 3898.68 3907.19
 3912.66 3916.35 3923.31 3923.64  3924.2 3944.64 3962.42 3965.87 3971.67 3974.19
  3980.6  3983.9 3985.75  3992.5 4003.93 4008.87 4020.06 4021.33 4031.98 4045.96
 4052.33 4056.62 4062.04 4080.87  4084.6 4099.42 4100.74 4102.75 4112.86 4126.15
 4135.97 4149.14 4159.08 4165.28 4170.64 4177.62
   65.82   65.82    66.1   66.15   66.07   65.89   65.75   65.33   65.42   65.43
    65.6   65.79   65.96   65.97      66   66.05   65.88    65.9   65.89   65.88
   65.86   65.73   65.42   64.98   65.24   65.04   65.78   66.15   65.98   65.46
   64.57   63.97   62.74      65   69.12   69.09   64.94   64.13   65.72   65.99
   66.16   66.23   66.26   66.35    66.5    66.5   66.55   66.53   66.38   66.45
   66.48   66.53   66.54   66.51   66.57   66.35   66.34   66.37   66.58   66.63
   66.65   66.88   66.93   66.98   66.89   66.79
                                                                                
                                                                                
                                                                                
                            60.7   64.82   64.79   60.64
                                                                                
                                                                                
                                                
Pier Skew, UpSta & Num, DnSta & Num=  ,3954.05, 2 ,3935.93, 2 , 0 , 0 , 0 ,,
      .3      .3
   60.21    64.8
      .3      .3
   60.21    64.8
Pier Skew, UpSta & Num, DnSta & Num=  ,3955.82, 2 ,3933.46, 2 , 0 , 0 , 0 ,,
      .3      .3
   60.08    64.8
      .3      .3
   60.08    64.8
BR Coef=-1 , 1 , 1 ,1.25, 0 ,,,.8,-1,2,0,
WSPro=,,,, 1 ,,,, 0 ,,,, 0 ,,,,-1 ,-1 ,-1 , 0 , 0 , 0 , 0 , 0
BC Design=,, 0 ,, 0 ,,,,,,
BC HTab HWMax=69.45

Type RM Length L Ch R = 1 ,6048.197,22.37,16.63,16.4
BEGIN DESCRIPTION:
Stations 3926.17 - 3970.26 developed from survey information (copied from cross-section 6105.91), and the remainder developed from LiDAR. The elevation of survey points adjusted to match the overall stream slope of approx. .0064 ft/ft.
END DESCRIPTION:
XS GIS Cut Line= 6
     3077846.719     13848032.07     3076502.938    13844614.939
     3076502.524    13844480.743      3076633.74    13844148.607
      3076633.34    13843300.324     3076263.282    13842279.283
#Sta/Elev= 30
       0   68.54  266.24   67.83  499.42   69.45  597.37   67.59  741.87   69.44
   865.6   67.57 1338.84    69.5 1458.98   67.66 1491.22   69.07 1603.86   67.27
 1678.02    68.9 1974.76   66.89  2184.3   67.08 2251.71      69 2345.48   67.41
 2540.92   68.33 3084.66   65.75 3477.67   67.36  3929.4   64.08 3929.46   64.03
 3944.67   53.78 3949.83   55.97  3957.9    63.8 4021.69   66.55 4517.48   68.16
 5107.59   66.76 5267.82    67.9 5436.49   64.86 5634.78    68.1 6097.48   66.77
#Mann= 3 ,-1 , 0
       0     .08       0  3929.4     .06       0 3949.83     .08       0
#XS Ineff= 6 ,-1
       0 3482.95   67.39 3550.12 3685.21   66.63 3713.25 3756.58   66.05
 4023.85 4132.16   66.58 4165.49 4390.45   66.96  4507.1 6148.48   68.14
Permanent Ineff=
       F       F       F       F       F       F
Bank Sta=3929.46,3957.9
XS Rating Curve= 0
Exp/Cntr=.5,.3

Type RM Length L Ch R = 1 ,6031.563,101.38,104.99,101.94
BEGIN DESCRIPTION:
Stations 3912.32 - 3956.41 developed from survey information (copied from cross-section 6105.91), and the remainder developed from LiDAR. The elevation of survey points adjusted to match the overall stream slope of approx. .0064 ft/ft.
END DESCRIPTION:
XS GIS Cut Line= 6
     3077864.514    13848032.731     3076522.927    13844618.822
     3076523.069    13844469.235     3076663.754    13844113.372
       3076661.2     13843363.55     3076273.126    13842279.283
#Sta/Elev= 30
       0   68.55  266.93   67.82  508.01   69.46  590.93   67.59  750.72   69.45
  924.06   67.47 1330.63   69.49 1475.68    67.8 1583.55   68.85 1652.98   67.28
 1710.81   68.75 2168.69      67 2266.17   69.05 2335.59   67.18 2520.71    68.5
 3110.78   65.69 3481.02   67.11 3913.98   64.85 3914.23   64.84 3930.82   53.67
 3933.82   53.97 3944.05   63.69 3962.66   65.84 4013.72   66.55 4369.39   66.36
  4521.4   68.03 5276.06   67.81 5447.51   64.88 5646.88    68.1 6101.77   66.66
#Mann= 3 ,-1 , 0
       0     .08       0 3914.23     .06       0 3944.05     .08       0
#XS Ineff= 3 ,-1
       0 3483.23   67.12 3543.75 3679.31   66.57 4015.74  6107.2    66.6
Permanent Ineff=
       F       F       F
Bank Sta=3913.98,3944.05
XS Rating Curve= 0
Exp/Cntr=.3,.1