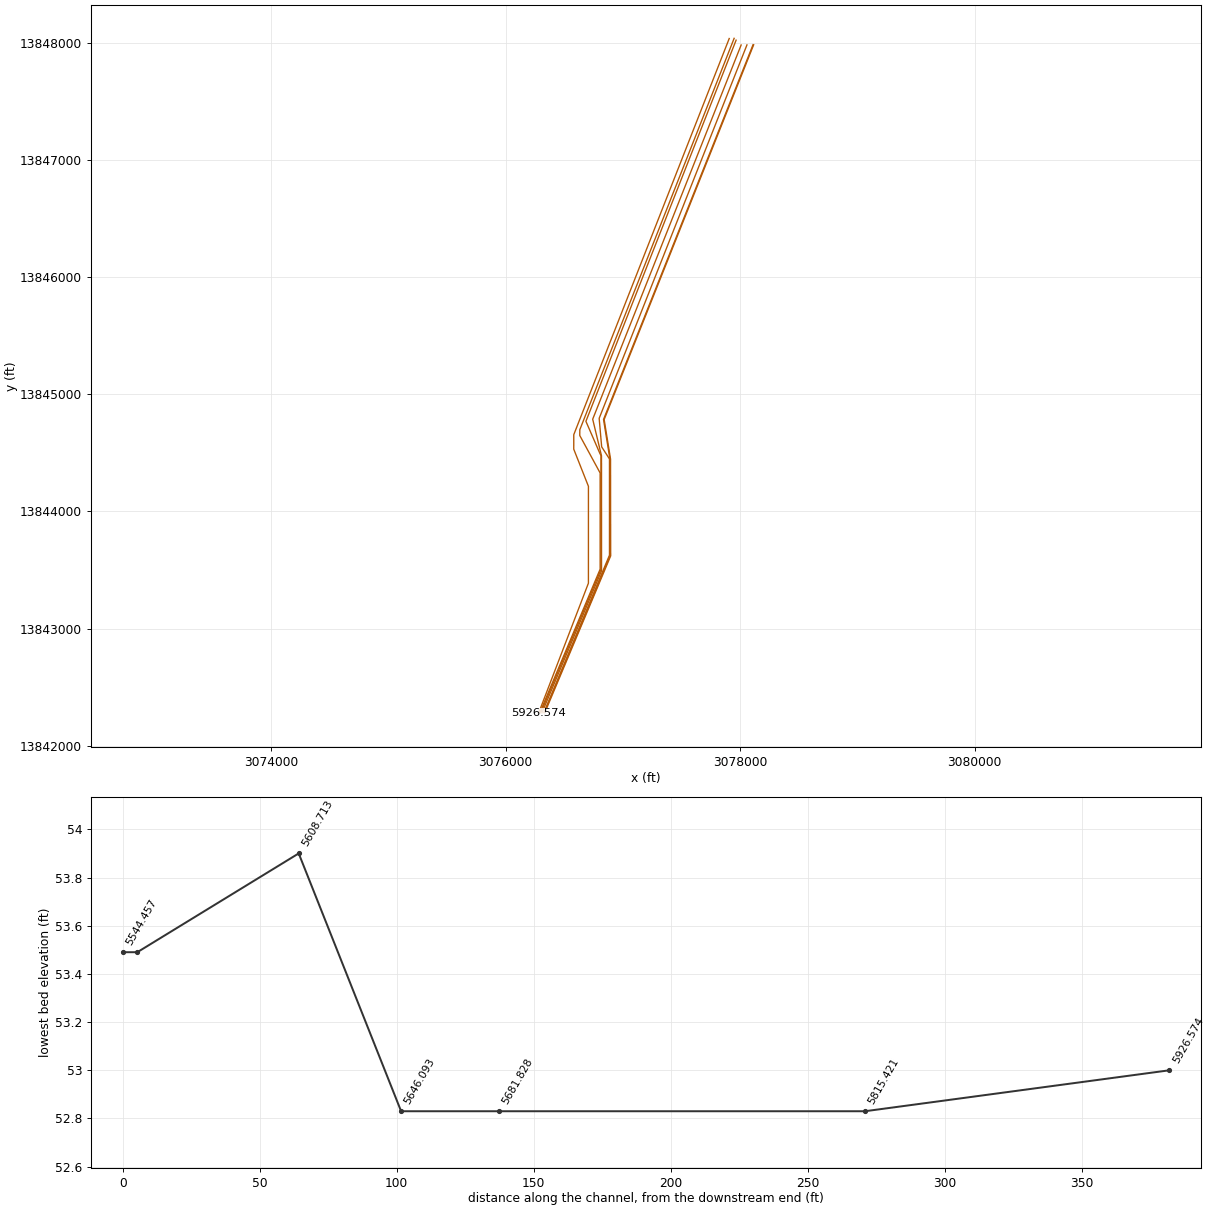
HEC-RAS study W141-00-00.prj: W141-00-00

--- W141-00-00.g01 (geometry) --- (continued)

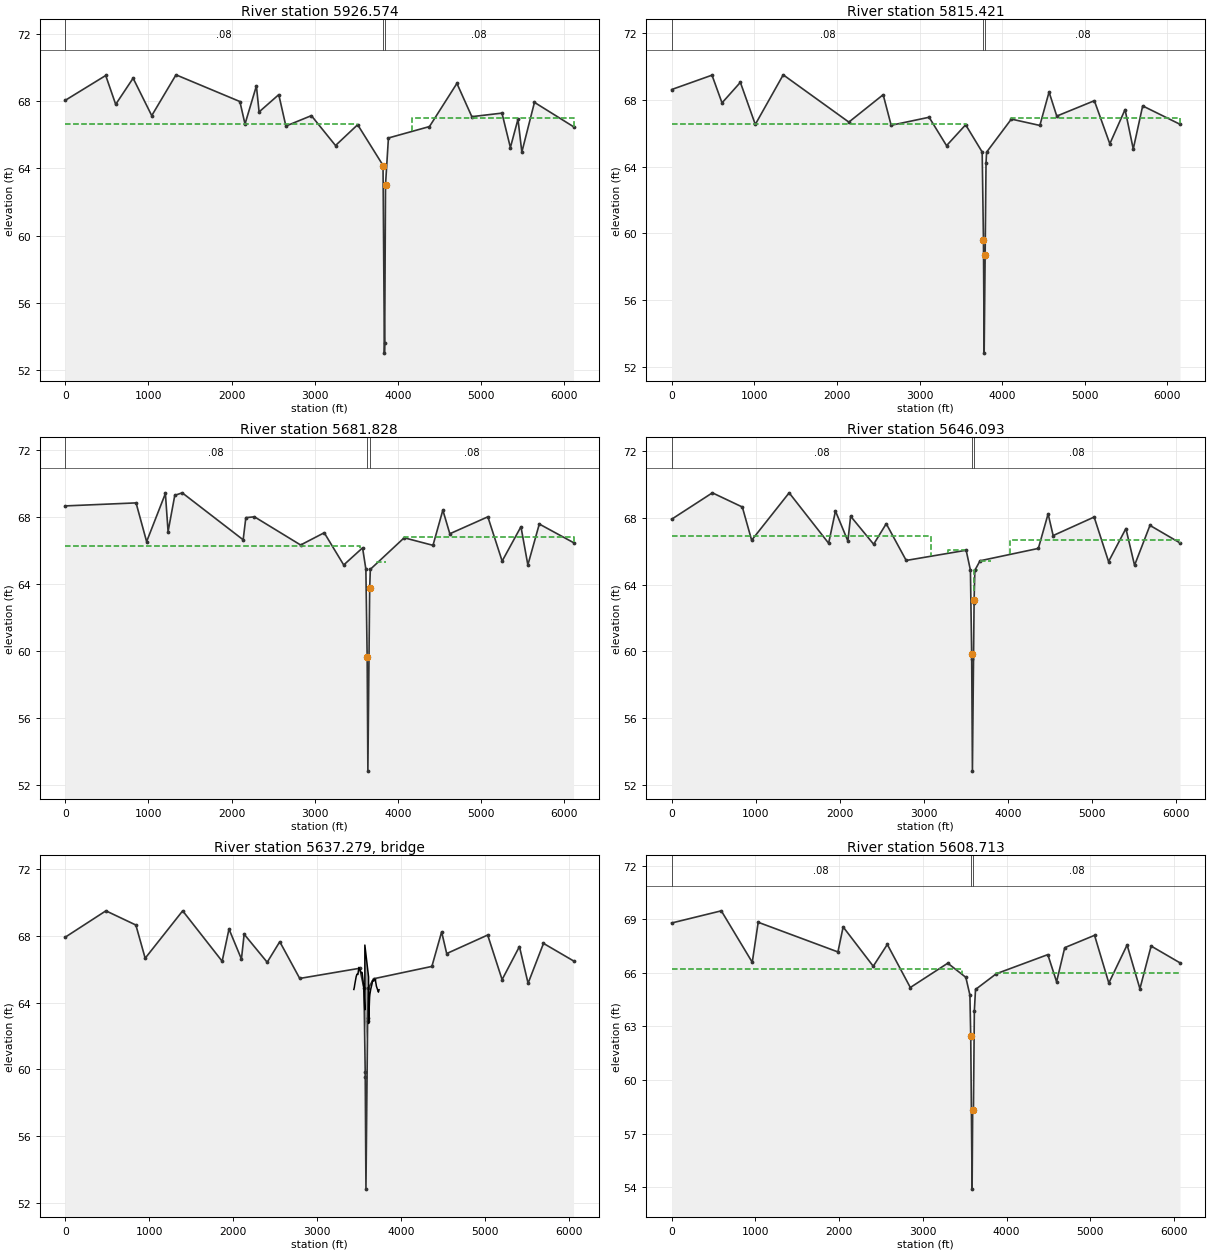
Type RM Length L Ch R = 1 ,5926.574,108.63,111.15,114.29
BEGIN DESCRIPTION:
Stations 3819.53 - 3863.63 developed from survey information (copied from cross-section 6105.91), and the remainder developed from LiDAR. The elevation of survey points adjusted to match the overall stream slope of approx. .0064 ft/ft.
END DESCRIPTION:
XS GIS Cut Line= 6
     3077907.048    13848034.311     3076580.653     13844653.77
     3076580.526    13844530.289     3076705.781    13844213.553
     3076705.679    13843386.941     3076279.689    13842276.001
#Sta/Elev= 30
       0   68.05  487.07   69.53  606.95   67.81  816.42   69.37 1040.44   67.14
 1332.04   69.57 2100.21   67.98 2161.86   66.64 2298.84   68.91 2331.07   67.36
 2567.82   68.39 2653.33   66.52    2960   67.14  3250.1   65.36 3516.28    66.6
 3821.26   64.18 3821.38   64.17 3838.03      53 3841.43   53.61 3851.26   63.02
 3886.31   65.81 4379.78   66.49 4709.78   69.06 4889.04   67.08 5251.49   67.29
 5352.77   65.24 5444.07   66.93 5490.47   64.97 5642.17   67.93 6111.97   66.48
#Mann= 3 ,-1 , 0
       0     .08       0 3821.26     .06       0 3841.43     .08       0
#XS Ineff= 2 , 0
         3511.51   66.64 4167.76           66.99
Permanent Ineff=
       F       F
Bank Sta=3821.38,3851.26
XS Rating Curve= 0
Exp/Cntr=.3,.1

Type RM Length L Ch R = 1 ,5815.421,129.1,133.59,126.81
BEGIN DESCRIPTION:
Stations 3758.5 - 3818.67 developed from survey information (copied from cross-section 5681.83), and the remainder developed from LiDAR.
END DESCRIPTION:
XS GIS Cut Line= 6
     3077948.992    13848035.869     3076632.318     13844696.48
     3076631.764    13844647.207     3076805.622    13844327.355
     3076805.622     13843506.41     3076290.814    13842281.049
#Sta/Elev= 30
       0   68.61  488.08   69.47  609.32   67.81  831.55   69.04 1012.12   66.52
 1350.09   69.49 2144.74   66.66 2560.01    68.3 2656.75   66.47 3115.97   66.95
 3327.13   65.25 3558.41    66.5  3758.5   64.87 3773.92   59.59 3773.99   59.54
  3782.5   52.83 3794.11   58.59 3794.29   58.68 3805.04   64.21 3811.87   64.86
 4111.65   66.84 4456.65   66.46 4568.02   68.46 4661.31   67.02 5116.23   67.94
 5303.51   65.36  5487.8   67.41 5587.24   65.05 5701.19   67.63 6152.97   66.53
#Mann= 3 ,-1 , 0
       0     .08       0 3773.99     .06       0 3794.11     .08       0
#XS Ineff= 2 , 0
         3559.99   66.57 4109.29           66.88
Permanent Ineff=
       F       F
Bank Sta=3773.92,3794.29
XS Rating Curve= 0
Exp/Cntr=.3,.1

Type RM Length L Ch R = 1 ,5681.828,39.7,35.74,30.25
BEGIN DESCRIPTION:
Stations 3615.65 - 3676.05 developed from survey information, and the remainder developed from LiDAR
END DESCRIPTION:
XS GIS Cut Line= 6
     3077965.842     13848020.22      3076684.28    13844768.108
     3076804.287    13844492.347     3076812.761    13844475.366
     3076812.761    13843504.384     3076298.909    13842281.333
#Sta/Elev= 30
       0   68.64  852.01   68.82   979.1   66.51 1204.82   69.38 1237.06   67.11
 1317.67   69.27 1407.23   69.42 2139.93   66.62 2172.18   67.94 2275.89   67.99
 2831.02   66.31 3114.78   67.04 3349.13   65.12 3576.01   66.14 3615.65   64.87
 3631.08   59.64 3631.14   59.59 3639.75   52.83 3661.46   63.74 3669.23   64.86
  4076.3   66.74 4422.72   66.29  4541.3   68.39 4625.22   66.98 5082.49   67.99
 5254.35   65.35  5480.5    67.4 5563.67   65.12 5701.16   67.56 6112.83   66.45
#Mann= 3 ,-1 , 0
       0     .08       0 3631.14     .06       0 3661.46     .08       0
#XS Ineff= 5 ,-1
       0 3545.44   66.23 3671.84 3725.02   64.86 3748.66 3855.02   65.32
 3967.29  4038.2   65.93 4073.39 6129.74   66.77
Permanent Ineff=
       F       F       F       F       F
Bank Sta=3631.08,3661.46
XS Rating Curve= 0
Exp/Cntr=.5,.3

Type RM Length L Ch R = 1 ,5646.093,36.2,37.38,33.08
BEGIN DESCRIPTION:
Stations 3556.05 - 3615.54 developed from survey information (copied from cross-section 5681.83), and the remainder developed from LiDAR.
END DESCRIPTION:
XS GIS Cut Line= 6
     3078008.798    13847979.139     3076742.135    13844785.956
     3076817.179    13844473.808      3076817.52    13843828.117
      3076817.52    13843492.225     3076309.427    13842281.703
#Sta/Elev= 30
       0   67.92  484.56    69.5  840.98   68.65  951.91   66.66 1398.24    69.5
 1868.21   66.48 1949.57   68.41 2097.64   66.61 2129.92    68.1 2404.25   66.42
 2554.04   67.65 2791.54   65.45 3505.27   66.06 3556.05   64.87 3571.06   59.82
 3571.36   59.54 3579.78   52.83 3599.55   62.91 3599.92   63.09 3608.81   64.86
 3670.64   65.43 4364.57   66.17 4480.79   68.24 4540.79   66.94 5028.75   68.05
  5200.4   65.38 5406.65   67.36 5509.78   65.16 5693.11   67.55 6050.69    66.5
#Mann= 3 ,-1 , 0
       0     .08       0 3571.36     .06       0 3599.55     .08       0
#XS Ineff= 5 ,-1
       0 3081.28    66.9 3291.55 3496.06   66.08 3602.56 3643.46   64.86
 3670.73 3800.25   65.44 4027.79 6045.62   66.65
Permanent Ineff=
       F       F       F       F       F
Bank Sta=3571.06,3599.92
XS Rating Curve= 0
Exp/Cntr=.5,.3

Type RM Length L Ch R = 3 ,5637.279,,,
BEGIN DESCRIPTION:
Structure 13 - rock walkway
END DESCRIPTION:
Bridge Culvert--1,0,-1,-1, 0
Deck Dist Width WeirC Skew NumUp NumDn MinLoCord MaxHiCord MaxSubmerge Is_Ogee
8,4,2.6,0, 38, 38, , , .95, 0, 0,0,,
 3435.55  3441.6    3445 3463.54 3472.45 3484.38 3495.25 3521.76 3534.16 3535.55
 3542.07 3549.59 3553.29 3554.19 3565.02 3566.63 3566.82  3592.4 3610.98  3611.3
 3623.31 3626.73 3628.82 3636.29 3637.52 3653.69 3657.58 3663.93 3673.01 3684.24
 3688.44    3691 3701.69 3703.86 3704.55 3728.32 3734.72 3736.29
   64.79   64.92   65.04   65.56    65.7   65.69   66.11    65.8   65.81   65.75
   65.45    65.1   64.94    64.9   63.65   63.57   67.45   66.34   65.54   62.75
   64.33   64.51   64.57   64.79   64.82   65.16   65.32   65.28   65.37   65.41
   65.38   65.37   65.07   64.99   64.98   64.63   64.76   64.77
                                                                                
                   60.39   60.35    59.1   59.02    62.9   61.79
                                                                                
                                                                
 3443.57 3449.62 3453.02 3471.56 3480.47  3492.4 3503.27 3529.78 3542.18 3543.57
 3550.09 3557.61 3561.31 3562.21 3564.97 3600.42  3608.9 3608.98 3611.02 3619.32
 3631.33 3634.75 3636.84 3644.31 3645.54 3661.71  3665.6 3671.95 3681.03 3692.26
 3696.46 3699.02 3709.71 3711.88 3712.57 3736.34 3742.74 3744.31
   64.79   64.92   65.04   65.56    65.7   65.69   66.11    65.8   65.81   65.75
   65.45    65.1   64.94    64.9   67.32   65.88   65.53    62.6   62.94   62.75
   64.33   64.51   64.57   64.79   64.82   65.16   65.32   65.28   65.37   65.41
   65.38   65.37   65.07   64.99   64.98   64.63   64.76   64.77
                                                                                
                   60.39   60.35   62.77   61.33
                                                                                
                                                                
BR Coef=-1 , 0 , 0 ,, 0 ,,,.8,-1,,0,
WSPro=,,,, 1 ,,,, 0 ,,,, 0 ,,,,-1 ,-1 ,-1 , 0 , 0 , 0 , 0 , 0
BC Design=,, 0 ,, 0 ,,,,,,
BC HTab HWMax=69.5

Type RM Length L Ch R = 1 ,5608.713,52.51,58.91,64.43
BEGIN DESCRIPTION:
Stations 3561.65 - 3628.66 developed from survey information (copied from cross-section 5544.46), and the remainder developed from LiDAR. The elevation of survey points adjusted to match the overall stream slope of approx. .0064 ft/ft.
END DESCRIPTION:
XS GIS Cut Line= 6
     3078058.474    13847979.996     3076797.398    13844793.553
     3076818.633    13844550.315     3076885.339    13844446.811
     3076885.339    13843625.969     3076325.897    13842282.283
#Sta/Elev= 30
       0   68.79  592.71   69.47  962.56   66.59  1033.2   68.83 1985.68   67.17
 2047.69   68.57 2407.29   66.37 2575.23   67.59 2850.12   65.18 3297.24   66.54
 3513.02   65.75 3561.65   64.76 3571.49   62.45  3571.8   62.33 3587.99    53.9
 3594.72    58.3 3603.79   58.34 3603.85   58.35 3614.88   63.88 3628.66   65.07
 3876.74   65.95 4492.08   67.02 4596.94    65.5 4694.36   67.41 5050.36    68.1
  5220.8   65.43 5439.01   67.56 5591.95   65.11  5725.8    67.5 6070.77   66.56
#Mann= 3 ,-1 , 0
       0     .08       0  3571.8     .06       0 3603.79     .08       0
#XS Ineff= 2 , 0
         3469.82    66.2  3877.7           65.99
Permanent Ineff=
       F       F
Bank Sta=3571.49,3603.85
XS Rating Curve= 0
Exp/Cntr=.5,.3

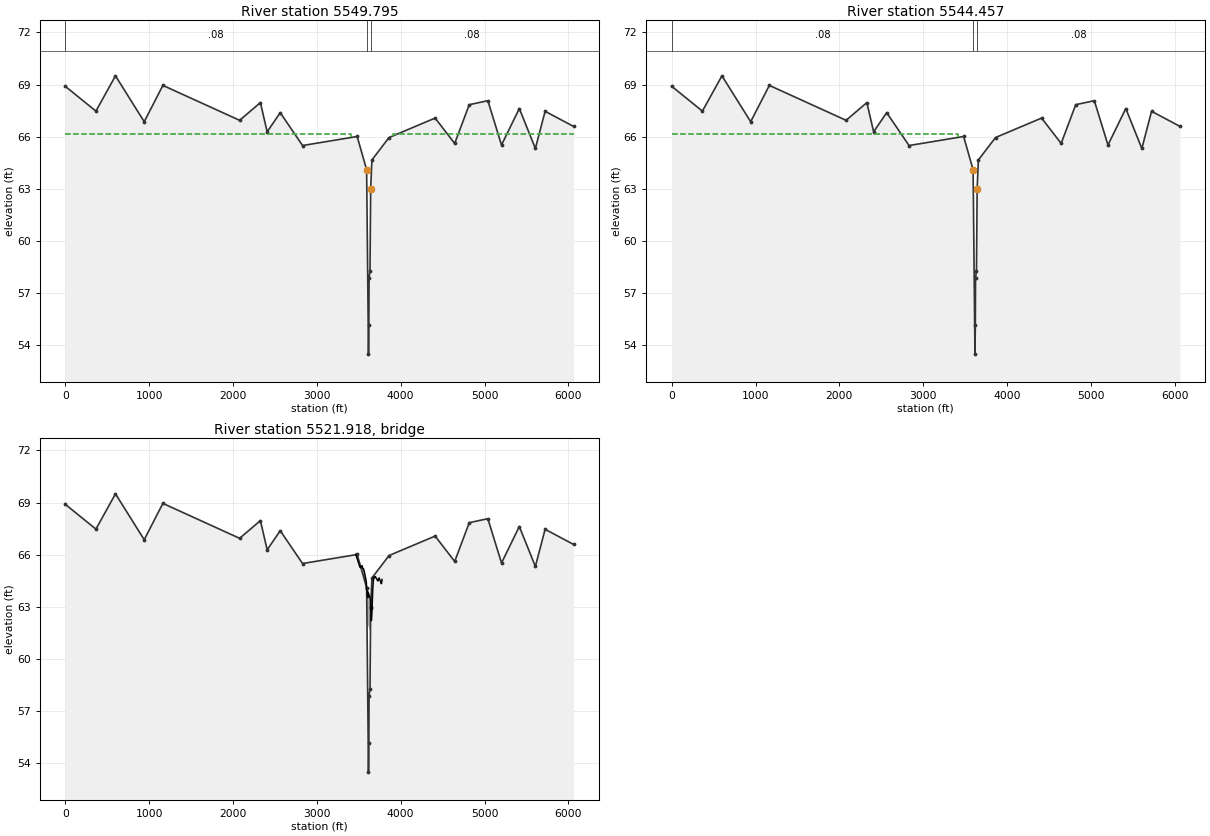
Type RM Length L Ch R = 1 ,5549.795,5.75,5.34,5.29
BEGIN DESCRIPTION:
Stations 3589.9 - 3657.03 developed from survey information, and the remainder developed from LiDAR.
Section data copied from cross-section 5544.46
END DESCRIPTION:
XS GIS Cut Line= 6
     3078110.353    13847981.262     3076834.593    13844783.577
     3076889.111    13844445.833     3076889.534     13843986.64
     3076890.293     13843620.17 3076328.348783113842282.8450031
#Sta/Elev= 30
       0    68.9   366.3   67.47  599.35    69.5  942.14   66.86 1164.59   68.95
 2079.79   66.94 2327.37   67.96 2408.12   66.28 2563.88   67.38 2830.16   65.49
 3481.17   66.01 3593.85    64.1 3594.09   64.09  3616.3   53.49 3620.76   55.15
 3623.04   57.89 3634.33   58.26 3642.27   62.92  3642.4   62.99 3657.03   64.66
 3861.37   65.95 4410.89   67.07 4644.12   65.61 4817.75   67.84 5039.66   68.07
 5202.36   65.52 5414.85   67.62 5606.14   65.32  5722.3   67.46 6061.16   66.59
#Mann= 3 ,-1 , 0
       0     .08       0 3593.85     .06       0 3642.27     .08       0
#XS Ineff= 2 , 0
       0  3410.7   66.16 3903.79       0   66.16
Permanent Ineff=
       F       F
Bank Sta=3594.09,3642.4
XS Rating Curve= 0
Exp/Cntr=.5,.3

Type RM Length L Ch R = 1 ,5544.457,35.11,32.86,31.45
BEGIN DESCRIPTION:
Stations 3589.9 - 3657.03 developed from survey information, and the remainder developed from LiDAR
END DESCRIPTION:
XS GIS Cut Line= 6
     3078115.676    13847980.982     3076839.916    13844783.297
     3076894.434    13844445.553     3076894.857     13843986.36
     3076895.616     13843619.89     3076333.668    13842282.556
#Sta/Elev= 30
       0    68.9   366.3   67.47  599.35    69.5  942.14   66.86 1164.59   68.95
 2079.79   66.94 2327.37   67.96 2408.12   66.28 2563.88   67.38 2830.16   65.49
 3481.17   66.01 3593.85    64.1 3594.09   64.09  3616.3   53.49 3620.76   55.15
 3623.04   57.89 3634.33   58.26 3642.27   62.92  3642.4   62.99 3657.03   64.66
 3861.37   65.95 4410.89   67.07 4644.12   65.61 4817.75   67.84 5039.66   68.07
 5202.36   65.52 5414.85   67.62 5606.14   65.32  5722.3   67.46 6061.16   66.59
#Mann= 3 ,-1 , 0
       0     .08       0 3593.85     .06       0 3642.27     .08       0
#XS Ineff= 2 , 0
          3410.7   66.16 3903.79           66.02
Permanent Ineff=
       F       F
Bank Sta=3594.09,3642.4
XS Rating Curve= 0
Exp/Cntr=.5,.3

Type RM Length L Ch R = 3 ,5521.918,,,
BEGIN DESCRIPTION:
Structure 12 - wood drive
END DESCRIPTION:
Bridge Culvert--1,0,-1,-1, 0
Deck Dist Width WeirC Skew NumUp NumDn MinLoCord MaxHiCord MaxSubmerge Is_Ogee
15,14,2.6,0, 43, 43, , , .95, 0, 0,0,,
 3465.88 3471.33 3513.81 3516.17 3521.77 3538.85 3546.35 3555.73 3565.88 3566.02
 3576.54 3589.69 3591.63 3593.18 3603.29 3604.54 3606.72 3607.16 3609.22 3638.79
 3647.02 3647.33 3647.52    3652 3656.14  3657.6 3667.09 3674.68 3678.18 3682.19
 3688.27 3697.28 3723.02 3726.55 3727.46 3728.28 3742.55 3742.58 3742.63 3742.99
 3769.76 3772.74 3778.18
   66.02   65.92   65.29   65.27   65.26   65.37   65.22    65.2   65.03   65.02
   64.79   64.45   64.35   64.07   63.68   63.63   63.55   63.52   63.87   63.48
   62.24   62.27   62.28   62.21   62.59   62.72   64.04   64.55   64.62    64.7
   64.72   64.74   64.53    64.5   64.49   64.49   64.66   64.66   64.66   64.66
   64.33   64.38   64.57
                                                                                
                                           61.73   61.65   61.62   61.97   61.58
   60.34   60.37   60.38   60.31   60.69
                                                                                
                        
 3461.54 3504.02 3506.38 3511.98 3529.06 3536.56 3545.94 3556.09 3556.23 3566.75
  3579.9 3581.84 3583.39 3589.05  3593.5 3594.75 3596.93 3597.37  3600.4 3629.63
 3637.23 3637.54 3637.73 3640.35 3642.21 3647.81  3657.3 3664.89 3668.39  3672.4
 3678.48 3687.49 3713.23 3716.76 3717.67 3718.49 3732.76 3732.79 3732.84  3733.2
 3759.97 3762.95 3768.39
    65.8   65.29   65.27   65.26   65.37   65.22    65.2   65.03   65.02   64.79
   64.45   64.35   64.07   63.85   63.68   63.63   63.55   63.52   63.92   63.62
   62.24   62.27   62.28   62.24   62.21   62.72   64.04   64.55   64.62    64.7
   64.72   64.74   64.53    64.5   64.49   64.49   64.66   64.66   64.66   64.66
   64.33   64.38   64.57
                                                                                
                           61.95   61.78   61.73   61.65   61.62   62.02   61.72
   60.34   60.37   60.38   60.34
                                                                                
                        
BR Coef=-1 , 0 , 0 ,, 0 ,,,.8,-1,,0,
WSPro=,,,, 1 ,,,, 0 ,,,, 0 ,,,,-1 ,-1 ,-1 , 0 , 0 , 0 , 0 , 0
BC Design=,, 0 ,, 0 ,,,,,,
BC HTab HWMax=69.5