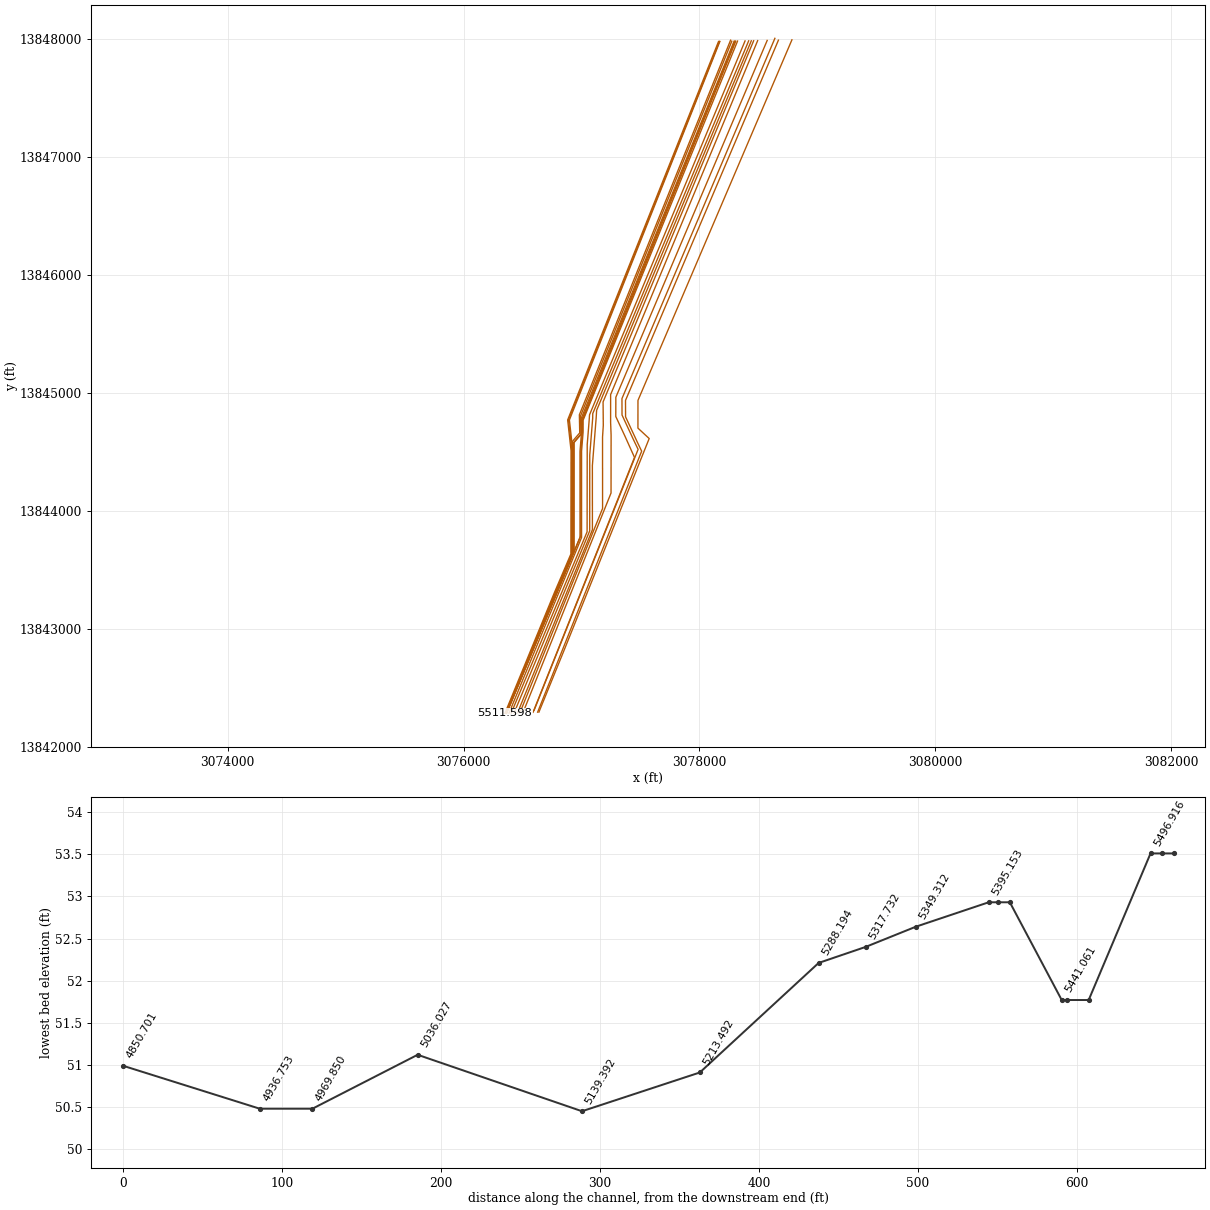
HEC-RAS study W141-00-00.prj: W141-00-00

--- W141-00-00.g01 (geometry) --- (continued)

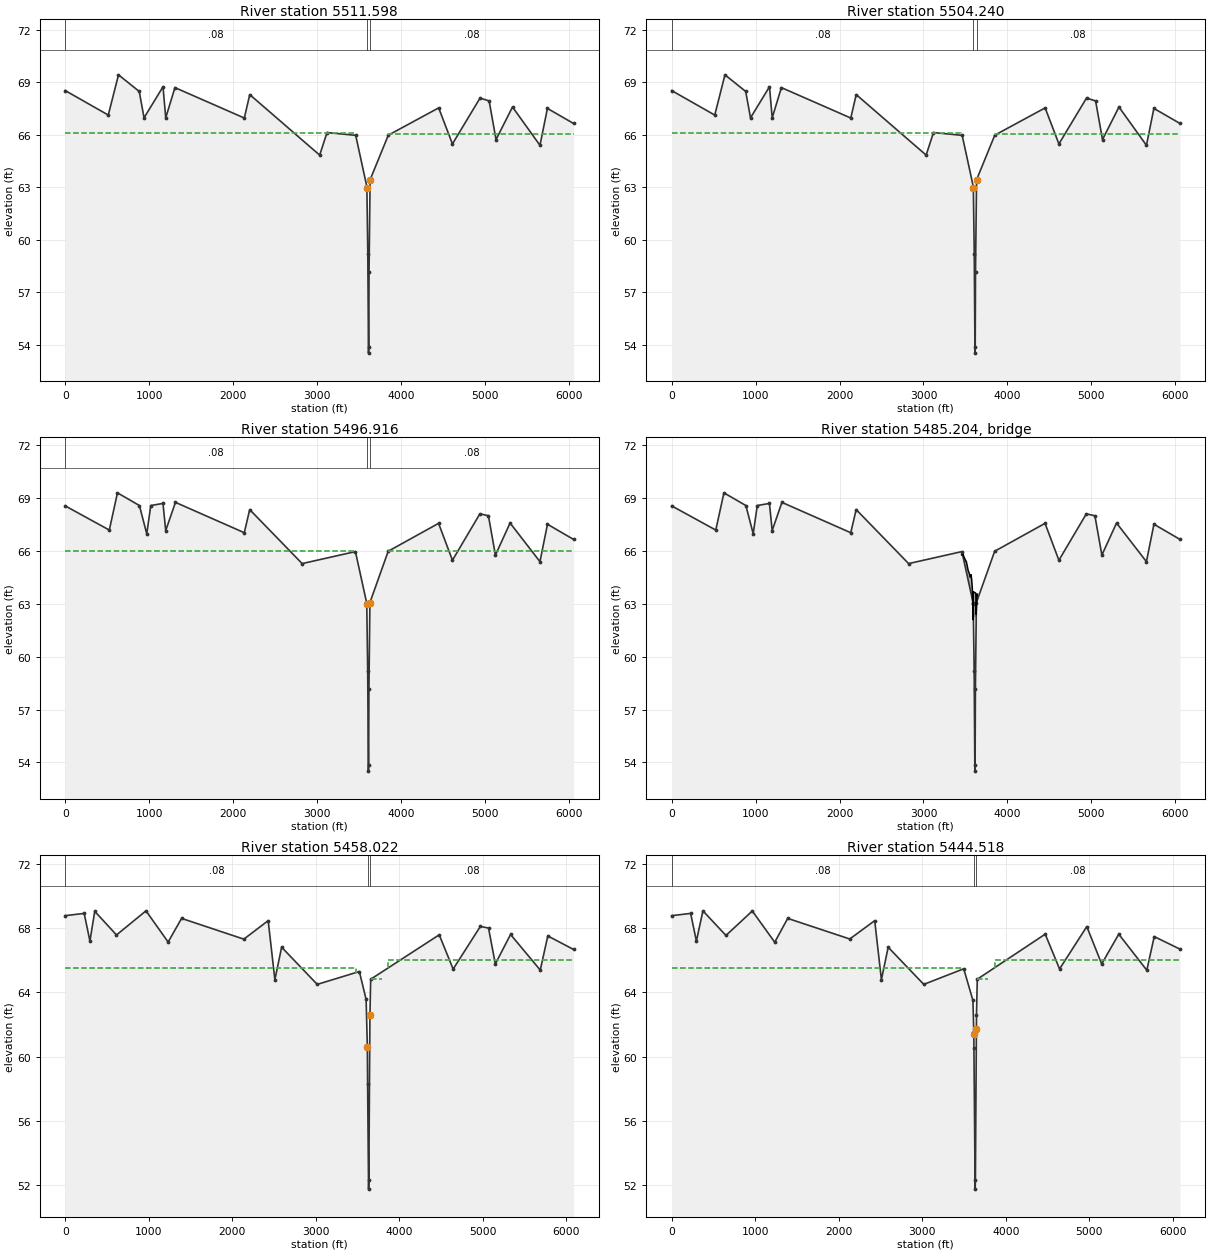
Type RM Length L Ch R = 1 ,5511.598,7.39,7.36,7.36
BEGIN DESCRIPTION:
Stations 3581.73 - 3653.37 developed from survey information, and the remainder developed from LiDAR.
Section data copied from cross-section 5504.24
END DESCRIPTION:
XS GIS Cut Line= 6
     3078162.681    13847981.656     3076882.898    13844771.488
     3076911.766    13844510.849     3076910.298    13843634.273
     3076769.075     13843303.22     3076350.666    13842283.391
#Sta/Elev= 30
       0   68.52  513.34   67.12  634.85   69.42  882.06   68.47  939.41   66.96
 1165.48   68.74 1197.78   66.96 1307.43   68.69 2134.13   66.95 2198.96   68.29
 3032.05   64.83  3119.4   66.12 3461.38   65.96 3594.48   63.02 3594.66   62.93
 3605.53   59.16  3613.9   53.51 3616.87   53.87 3620.31   58.14 3632.88   63.42
 3849.91   65.97 4449.91   67.53 4614.02   65.47 4942.84   68.09  5051.1   67.93
 5133.53   65.72 5329.71   67.58 5657.15   65.39 5745.72    67.5 6056.92   66.64
#Mann= 3 ,-1 , 0
       0     .08       0 3594.48     .06       0 3632.88     .08       0
#XS Ineff= 2 , 0
       0 3451.22   66.07 3848.58       0   66.04
Permanent Ineff=
       F       F
Bank Sta=3594.66,3632.88
XS Rating Curve= 0
Exp/Cntr=.5,.3

Type RM Length L Ch R = 1 ,5504.240,7.35,7.32,7.32
BEGIN DESCRIPTION:
Stations 3581.73 - 3653.37 developed from survey information, and the remainder developed from LiDAR
END DESCRIPTION:
XS GIS Cut Line= 6
     3078170.039    13847981.919     3076890.256    13844771.751
     3076919.124    13844511.112     3076917.656    13843634.536
     3076776.433    13843303.483     3076358.025    13842283.654
#Sta/Elev= 30
       0   68.52  513.34   67.12  634.85   69.42  882.06   68.47  939.41   66.96
 1165.48   68.74 1197.78   66.96 1307.43   68.69 2134.13   66.95 2198.96   68.29
 3032.05   64.83  3119.4   66.12 3461.38   65.96 3594.48   63.02 3594.66   62.93
 3605.53   59.16  3613.9   53.51 3616.87   53.87 3620.31   58.14 3632.88   63.42
 3849.91   65.97 4449.91   67.53 4614.02   65.47 4942.84   68.09  5051.1   67.93
 5133.53   65.72 5329.71   67.58 5657.15   65.39 5745.72    67.5 6056.92   66.64
#Mann= 3 ,-1 , 0
       0     .08       0 3594.48     .06       0 3632.88     .08       0
#XS Ineff= 2 , 0
         3451.22   66.07 3848.58           66.04
Permanent Ineff=
       F       F
Bank Sta=3594.66,3632.88
XS Rating Curve= 0
Exp/Cntr=.5,.3

Type RM Length L Ch R = 1 ,5496.916,60.12,38.9,6.19
BEGIN DESCRIPTION:
Stations 3580.17 - 3651.8 developed from survey information (copied from cross-section 5504.24), and the remainder developed from LiDAR.
END DESCRIPTION:
XS GIS Cut Line= 6
     3078174.102    13847981.989     3076897.678    13844771.256
      3076920.99     13844560.52      3076919.96    13843633.262
     3076779.833    13843302.208     3076358.217     13842283.42
#Sta/Elev= 30
       0   68.54  525.58   67.17  622.55   69.28  884.02   68.56  971.41   66.96
 1019.83   68.56 1165.11   68.68 1197.39   67.14 1313.47   68.74 2133.62   67.02
 2198.19   68.33 2823.02   65.27 3457.78   65.95  3592.9   63.02 3593.02   62.96
 3603.96   59.16 3612.33   53.51  3615.3   53.87 3618.74   58.14 3630.45   63.06
 3848.39   65.97 4448.39   67.55 4613.68   65.46 4940.79   68.09 5042.57   67.98
 5125.66   65.75 5300.53   67.57 5656.47   65.38 5746.03    67.5  6056.5   66.64
#Mann= 3 ,-1 , 0
       0     .08       0  3592.9     .06       0 3630.45     .08       0
#XS Ineff= 2 , 0
          3459.7   65.99 3851.15           65.99
Permanent Ineff=
       F       F
Bank Sta=3593.02,3630.45
XS Rating Curve= 0
Exp/Cntr=.5,.3

Type RM Length L Ch R = 3 ,5485.204,,,
BEGIN DESCRIPTION:
Structure 11 - wood plank driveway
END DESCRIPTION:
Bridge Culvert--1,0,-1,-1, 0
Deck Dist Width WeirC Skew NumUp NumDn MinLoCord MaxHiCord MaxSubmerge Is_Ogee
4,14.45,2.6,0, 25, 22, , , .95, 0, 0,0,,
 3454.52 3457.27 3472.66 3482.32 3507.56 3510.52 3532.68 3549.06 3552.57 3554.52
 3559.84 3567.57 3574.94 3582.58  3587.4  3590.6 3593.49 3593.65 3623.94 3627.59
 3630.41 3631.21 3632.11 3636.74  3642.6
   65.76   65.77   65.79   65.65   65.39   65.39   64.88   64.67   64.54   64.53
   64.51   64.64   64.34   63.83   62.93   62.34   62.08   63.68   63.59   62.39
   62.68   62.77   62.86   63.35   63.54
                                                                                
                                   61.53   60.94   60.68   62.28   62.19   60.99
   61.28   61.37   61.46
    3500 3528.72 3531.68 3553.84 3570.22 3573.73 3575.68    3581 3588.73  3596.1
 3603.74 3608.56 3611.76 3614.65 3615.24  3616.1 3647.32 3648.75 3651.57 3652.37
  3657.9 3663.76
   65.12   65.39   65.39   64.88   64.67   64.54   64.53   64.51   64.64   64.34
   63.83   62.93   62.34   62.08   62.03   63.65   63.66   62.39   62.68   62.77
   63.35   63.54
                                                                                
           61.53   60.94   60.68   60.63   62.25   62.26   60.99   61.28   61.37
   61.46   61.46
BR Coef=-1 , 0 , 0 ,, 0 ,,,.8,-1,,0,
WSPro=,,,, 1 ,,,, 0 ,,,, 0 ,,,,-1 ,-1 ,-1 , 0 , 0 , 0 , 0 , 0
BC Design=,, 0 ,, 0 ,,,,,,
BC HTab HWMax=69.28

Type RM Length L Ch R = 1 ,5458.022,13.94,13.5,22.21
BEGIN DESCRIPTION:
Stations 3612.33 - 3666.72 developed from survey information (copied from cross-section 5441.06), and the remainder developed from LiDAR.
END DESCRIPTION:
XS GIS Cut Line= 6
     3078264.857    13847992.677     3076982.217    13844815.034
     3076985.247    13844661.648      3076923.16    13844589.274
     3076923.285    13843632.875 3076361.620251613842288.2589281
#Sta/Elev= 30
       0   68.76  227.36    68.9  296.03   67.18  353.92   69.03  614.42   67.56
  967.73   69.06 1232.79   67.12 1394.13   68.59 2140.08    67.3 2431.46   68.45
 2511.61   64.78 2592.64    66.8 3019.04   64.49 3523.61   65.29 3604.58   63.56
 3619.44    60.6 3622.49    58.3 3634.11   51.77 3637.19   52.34 3650.31   62.58
 3659.51   64.81 4480.47   67.57 4646.98   65.44  4972.9   68.09 5070.98   67.99
 5152.41   65.76  5334.9   67.59 5690.63   65.38 5780.97    67.5 6089.23   66.66
#Mann= 3 ,-1 , 0
       0     .08       0 3622.49     .06       0 3650.31     .08       0
#XS Ineff= 3 ,-1
       0 3481.44   65.48 3662.24 3790.56   64.82 3866.33 6082.62      66
Permanent Ineff=
       F       F       F
Bank Sta=3619.44,3650.31
XS Rating Curve= 0
Exp/Cntr=.5,.3

Type RM Length L Ch R = 1 ,5444.518,4.68,3.46,3.46
BEGIN DESCRIPTION:
Stations 3612.33 - 3666.72 developed from survey information (copied from cross-section 5441.06), and the remainder developed from LiDAR.
END DESCRIPTION:
XS GIS Cut Line= 6
      3078275.04    13847983.807       3076992.4    13844806.165
     3076995.431    13844652.779     3076933.343    13844580.404
     3076933.304    13843653.242     3076361.068    13842283.424
#Sta/Elev= 30
       0   68.76  227.36    68.9  296.03   67.18  374.19   69.06  650.22   67.53
   965.5   69.05 1234.23   67.11 1389.52   68.59 2132.73   67.31 2431.46   68.45
 2511.61   64.78 2592.64    66.8 3019.04   64.49 3497.42   65.46 3607.87   63.49
  3618.3   61.42 3619.52   60.54 3634.11   51.77 3637.19   52.34 3649.16   61.69
 3650.32   62.59 3659.51   64.81 4473.33   67.61 4645.17   65.45 4971.05   68.08
 5149.69   65.76 5353.92   67.61  5689.9   65.37 5778.79   67.46 6087.32   66.68
#Mann= 3 ,-1 , 0
       0     .08       0 3619.52     .06       0 3650.32     .08       0
#XS Ineff= 3 ,-1
       0 3481.44   65.48 3662.24 3790.56   64.82 3866.33 6082.62      66
Permanent Ineff=
       F       F       F
Bank Sta=3618.3,3649.16
XS Rating Curve= 0
Exp/Cntr=.5,.3

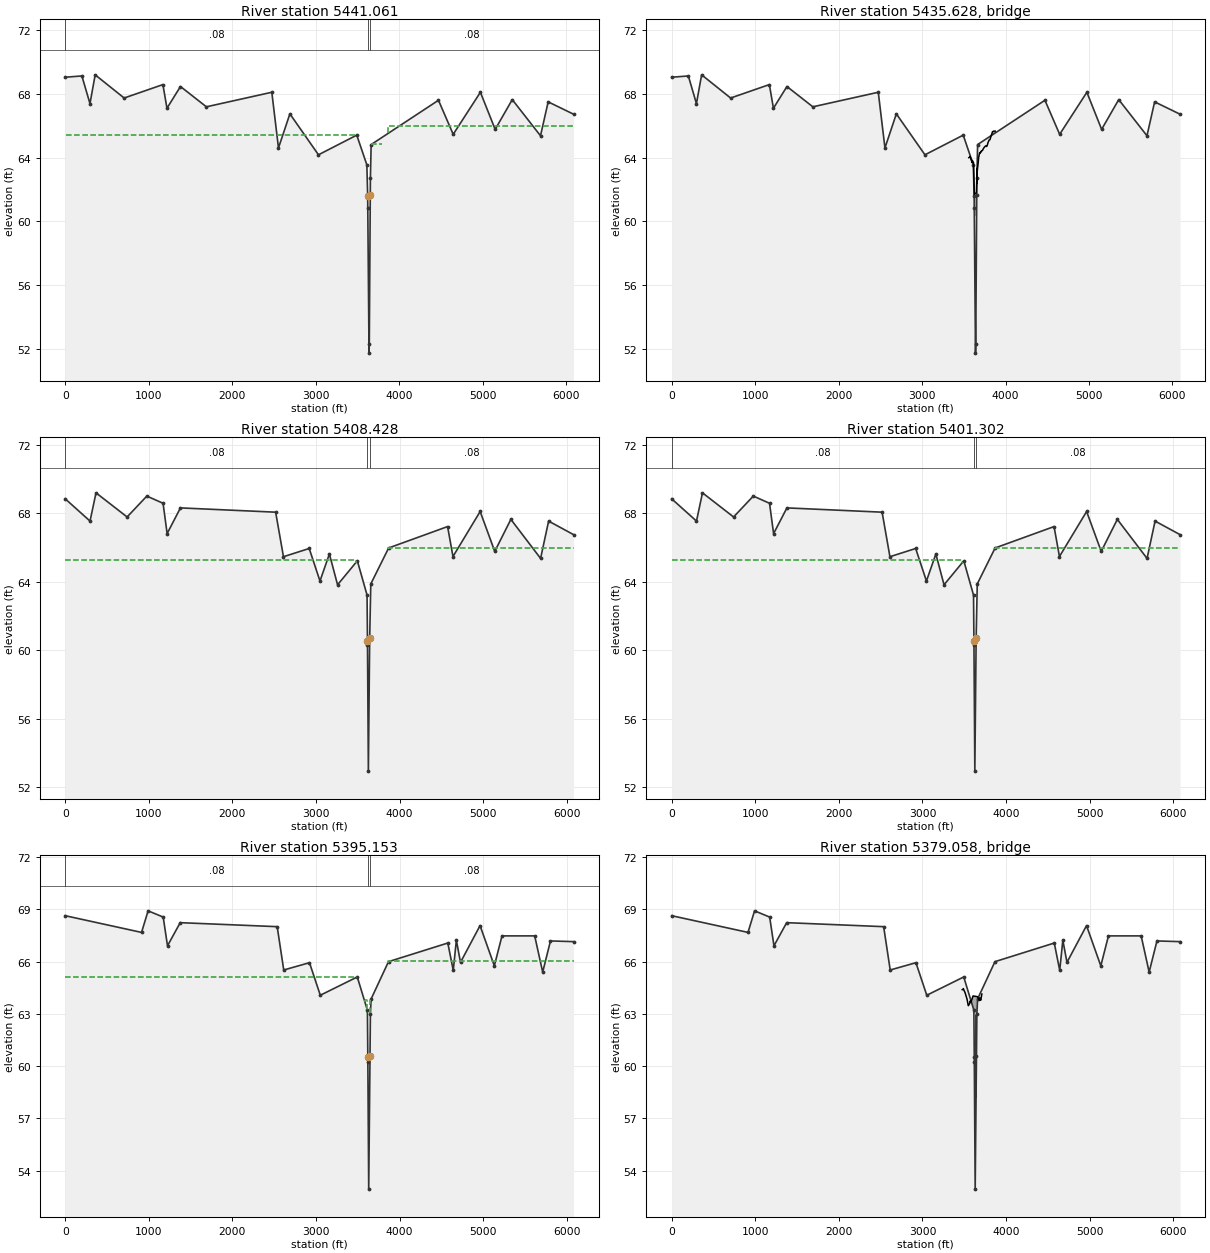
Type RM Length L Ch R = 1 ,5441.061,15.56,32.63,49.99
BEGIN DESCRIPTION:
Stations 3618.62 - 3673.01 developed from survey information, and the remainder developed from LiDAR
END DESCRIPTION:
XS GIS Cut Line= 6
       3078294.8    13847984.258     3076997.875    13844784.266
     3076997.882    13844650.327     3076937.852    13844580.351
     3076937.574    13843659.155     3076363.452    13842283.604
#Sta/Elev= 30
       0   69.02  199.75    69.1  296.68   67.37  359.04   69.17  706.26   67.72
 1170.68   68.56 1219.23   67.08 1381.09   68.44 1691.58   67.17 2475.58   68.08
 2555.45    64.6 2692.08   66.73 3034.67   64.17 3493.38    65.4  3614.4   63.54
 3623.98   61.59 3625.38   60.87  3640.4   51.77 3643.48   52.34  3655.4   61.65
 3656.74   62.69  3665.8   64.81 4472.37   67.58 4648.88   65.45  4974.8   68.08
 5151.66   65.76 5356.56   67.62 5694.97   65.36 5786.73   67.48 6090.71   66.71
#Mann= 3 ,-1 , 0
       0     .08       0 3625.38     .06       0 3656.74     .08       0
#XS Ineff= 3 ,-1
   14.85 3488.79   65.41 3666.94 3793.13   64.82  3870.3 6156.57   65.99
Permanent Ineff=
       F       F       F
Bank Sta=3623.98,3655.4
XS Rating Curve= 0
Exp/Cntr=.5,.3

Type RM Length L Ch R = 3 ,5435.628,,,
BEGIN DESCRIPTION:
Structure 10 - wood walkbridge
END DESCRIPTION:
Bridge Culvert--1,0,-1,-1, 0
Deck Dist Width WeirC Skew NumUp NumDn MinLoCord MaxHiCord MaxSubmerge Is_Ogee
5,4.9,2.6,0, 42, 44, , , .95, 0, 0,0,,
 3560.47 3569.41 3575.51  3580.8 3586.76 3591.74 3598.44 3602.34 3616.58 3625.73
 3625.99 3626.34  3651.6  3651.8 3658.77 3659.65 3660.62 3670.79  3671.1 3671.45
 3678.26 3690.56 3694.49 3697.76 3707.36 3708.28 3716.33 3723.25 3737.55  3748.9
 3763.54 3774.46 3782.85 3789.51 3802.95 3813.05 3842.73 3843.01 3843.25 3843.66
 3858.35 3876.86
   63.99   64.02   64.07   63.99   63.87   63.81   63.69   63.82   63.68   61.94
   61.84    61.7   61.81   61.88   63.34   62.37   63.12   63.59    63.6   63.61
   64.01    64.3    64.3   64.28   64.38   64.37   64.42   64.44   64.58   64.66
   64.73   64.69   64.79   64.92   65.09   65.11   65.59    65.6    65.6   65.61
   65.65   65.65
                                                                                
   60.42   60.28   60.39
                                                                                
                                                                                
                
 3545.98 3554.92 3561.02 3566.31 3572.27 3577.25 3583.95 3587.85 3602.09 3611.24
  3611.5 3611.85 3637.11 3637.31 3644.28 3645.16 3646.13  3656.3 3656.61 3656.96
 3663.77 3676.07    3680 3683.27 3692.87 3693.79 3701.84 3708.76 3723.06 3734.41
 3749.05 3759.97 3768.36 3775.02 3788.46 3798.56 3828.24 3828.52 3828.76 3829.17
 3843.86 3862.37 3877.38 3881.09
   63.99   64.02   64.07   63.99   63.87   63.81   63.69   63.82   63.68   61.94
   61.84    61.7   61.81   61.88   63.34   62.37   63.12   63.59    63.6   63.61
   64.01    64.3    64.3   64.28   64.38   64.37   64.42   64.44   64.58   64.66
   64.73   64.69   64.79   64.92   65.09   65.11   65.59    65.6    65.6   65.61
   65.65   65.89    65.7    65.7
                                                                                
   60.42   60.28   60.39
                                                                                
                                                                                
                                
BR Coef=-1 , 0 , 0 ,, 0 ,,,.8,-1,,0,
WSPro=,,,, 1 ,,,, 0 ,,,, 0 ,,,,-1 ,-1 ,-1 , 0 , 0 , 0 , 0 , 0
BC Design=,, 0 ,, 0 ,,,,,,
BC HTab HWMax=69.15

Type RM Length L Ch R = 1 ,5408.428,7.12,7.13,7.16
BEGIN DESCRIPTION:
Stations 3610.81 - 3664.96 developed from survey information (copied from cross-section 5317.73), and the remainder developed from LiDAR. The elevation of survey points adjusted to match the overall stream slope of approx. .0064 ft/ft.
END DESCRIPTION:
XS GIS Cut Line= 6
       3078301.7    13847984.578     3077001.494    13844769.907
      3077001.48    13844679.446     3076987.543    13844504.908
     3076987.666    13843775.625 3076363.822975513842282.4926591
#Sta/Elev= 30
       0   68.83  296.94   67.53  368.53   69.18  740.51   67.77  976.52   68.99
 1170.69   68.57 1219.23    66.8 1378.52    68.3 2517.29   68.05 2610.75   65.45
 2918.74   65.93 3047.62   64.03 3160.29   65.61 3257.97   63.81 3494.61   65.21
 3610.81   63.21 3615.71   60.54 3616.01   60.31 3626.47   52.93 3642.16   60.69
 3655.51   63.86 3869.04   65.96  4574.1   67.21 4638.67   65.46 4963.74   68.09
 5138.31   65.76 5331.12   67.63 5686.63   65.35 5782.59   67.53 6080.71   66.74
#Mann= 3 ,-1 , 0
       0     .08       0 3616.01     .06       0 3642.16     .08       0
#XS Ineff= 2 , 0
       0 3477.88   65.23 3863.88       0   65.98
Permanent Ineff=
       F       F
Bank Sta=3615.71,3642.16
XS Rating Curve= 0
Exp/Cntr=.5,.3

Type RM Length L Ch R = 1 ,5401.302,6.15,6.15,6.18
BEGIN DESCRIPTION:
Stations 3610.81 - 3664.96 developed from survey information (copied from cross-section 5317.73), and the remainder developed from LiDAR. The elevation of survey points adjusted to match the overall stream slope of approx. .0064 ft/ft.
END DESCRIPTION:
XS GIS Cut Line= 6
     3078308.802    13847984.578     3077008.596    13844769.907
     3077008.582    13844679.446     3076994.645    13844504.908
     3076994.806    13843790.857     3076365.123    13842283.663
#Sta/Elev= 30
       0   68.83  296.94   67.53  368.53   69.18  740.51   67.77  976.52   68.99
 1170.69   68.57 1219.23    66.8 1378.52    68.3 2517.29   68.05 2610.75   65.45
 2918.74   65.93 3047.62   64.03 3160.29   65.61 3257.97   63.81 3494.61   65.21
 3610.81   63.21 3615.71   60.54 3616.01   60.31 3626.47   52.93 3642.16   60.69
 3655.51   63.86 3869.04   65.96  4574.1   67.21 4638.67   65.46 4963.74   68.09
 5138.31   65.76 5331.12   67.63 5686.63   65.35 5782.59   67.53 6080.71   66.74
#Mann= 3 ,-1 , 0
       0     .08       0 3616.01     .06       0 3642.16     .08       0
#XS Ineff= 2 , 0
         3477.88   65.23 3863.88           65.98
Permanent Ineff=
       F       F
Bank Sta=3615.71,3642.16
XS Rating Curve= 0
Exp/Cntr=.5,.3

Type RM Length L Ch R = 1 ,5395.153,46.27,45.84,45.32
BEGIN DESCRIPTION:
Stations 3614.47 - 3668.62 developed from survey information (copied from cross-section 5317.73), and the remainder developed from LiDAR. The elevation of survey points adjusted to match the overall stream slope of approx. .0064 ft/ft.
END DESCRIPTION:
XS GIS Cut Line= 6
      3078323.94    13847984.923     3077013.959    13844769.141
     3077013.552    13844664.928     3077000.836    13844505.684
     3077000.935    13843773.966     3076385.306    13842284.372
#Sta/Elev= 30
       0   68.64  913.09   67.68  991.36   68.92 1172.24   68.56 1223.47   66.91
 1375.59   68.24 2535.45   68.01 2613.76   65.52  2921.5   65.94 3051.08   64.07
 3493.27   65.12 3614.47   63.21 3619.41   60.51 3619.77   60.23 3630.13   52.93
 3645.61   60.59 3650.46   63.02 3659.16   63.86 3866.77      66 4576.21   67.07
 4641.33    65.5 4678.48   67.23 4727.97   65.96  4961.8   68.07 5132.63   65.76
 5224.29   67.48 5615.41   67.48 5710.83    65.4 5804.14   67.19 6079.87   67.15
#Mann= 3 ,-1 , 0
       0     .08       0 3619.77     .06       0 3645.61     .08       0
#XS Ineff= 4 ,-1
       0 3485.46   65.14 3584.67 3614.75   63.78 3650.91 3658.73   63.78
 3861.76 6079.87   66.01
Permanent Ineff=
       F       F       F       F
Bank Sta=3619.41,3645.61
XS Rating Curve= 0
Exp/Cntr=.5,.3

Type RM Length L Ch R = 3 ,5379.058,,,
BEGIN DESCRIPTION:
Structure 9 - unnamed wood walk
END DESCRIPTION:
Bridge Culvert--1,0,-1,-1, 0
Deck Dist Width WeirC Skew NumUp NumDn MinLoCord MaxHiCord MaxSubmerge Is_Ogee
9,13.2,2.6,0, 23, 33, , , .95, 0, 0,0,,
 3475.25 3485.71 3488.36 3500.87 3503.41 3509.92  3533.5 3542.67 3548.55 3555.44
  3563.6 3570.54 3575.25 3578.64  3604.8  3653.6 3659.19 3682.02 3683.98 3688.08
 3695.96 3699.03 3709.89
   64.39   64.41   64.45    64.3   64.28   64.21   63.83   63.59   63.47   63.53
   63.58   63.74   63.69   63.66   64.03   63.99   63.98   63.77   63.92   63.87
   63.78   63.84   64.14
                                                                                
                                   63.03   62.99
                        
 3474.72 3485.18 3487.83 3500.34 3502.88 3509.39 3532.97 3542.14 3548.02 3554.91
 3563.07 3570.01 3574.72 3578.11 3602.55 3653.07 3656.76 3681.49 3683.45 3687.55
 3695.43  3698.5 3709.36 3713.54  3723.3 3728.59  3734.8 3743.64 3751.17 3767.51
 3773.73 3779.04 3787.55
   64.39   64.41   64.45    64.3   64.28   64.21   63.83   63.59   63.47   63.53
   63.58   63.74   63.69   63.66   63.99   63.94   63.94   63.77   63.92   63.87
   63.78   63.84   64.14    64.2   64.27   64.23   64.33   64.56   64.46   64.44
   64.45   64.59    64.7
                                                                                
                                   62.99   62.94
                                                                                
                        
Pier Skew, UpSta & Num, DnSta & Num=  ,3625.8, 2 ,3620.78, 2 , 0 , 0 , 0 ,,
       1       1
   59.61   63.03
       1       1
   53.17   63.03
Pier Skew, UpSta & Num, DnSta & Num=  ,3640.8, 2 ,3638.5, 2 , 0 , 0 , 0 ,,
       1       1
   53.06   63.03
       1       1
   53.17   63.03
BR Coef=-1 , 1 , 1 ,1.25, 0 ,,,.8,-1,1.2,0,
WSPro=,,,, 1 ,,,, 0 ,,,, 0 ,,,,-1 ,-1 ,-1 , 0 , 0 , 0 , 0 , 0
BC Design=,, 0 ,, 0 ,,,,,,
BC HTab HWMax=69.15

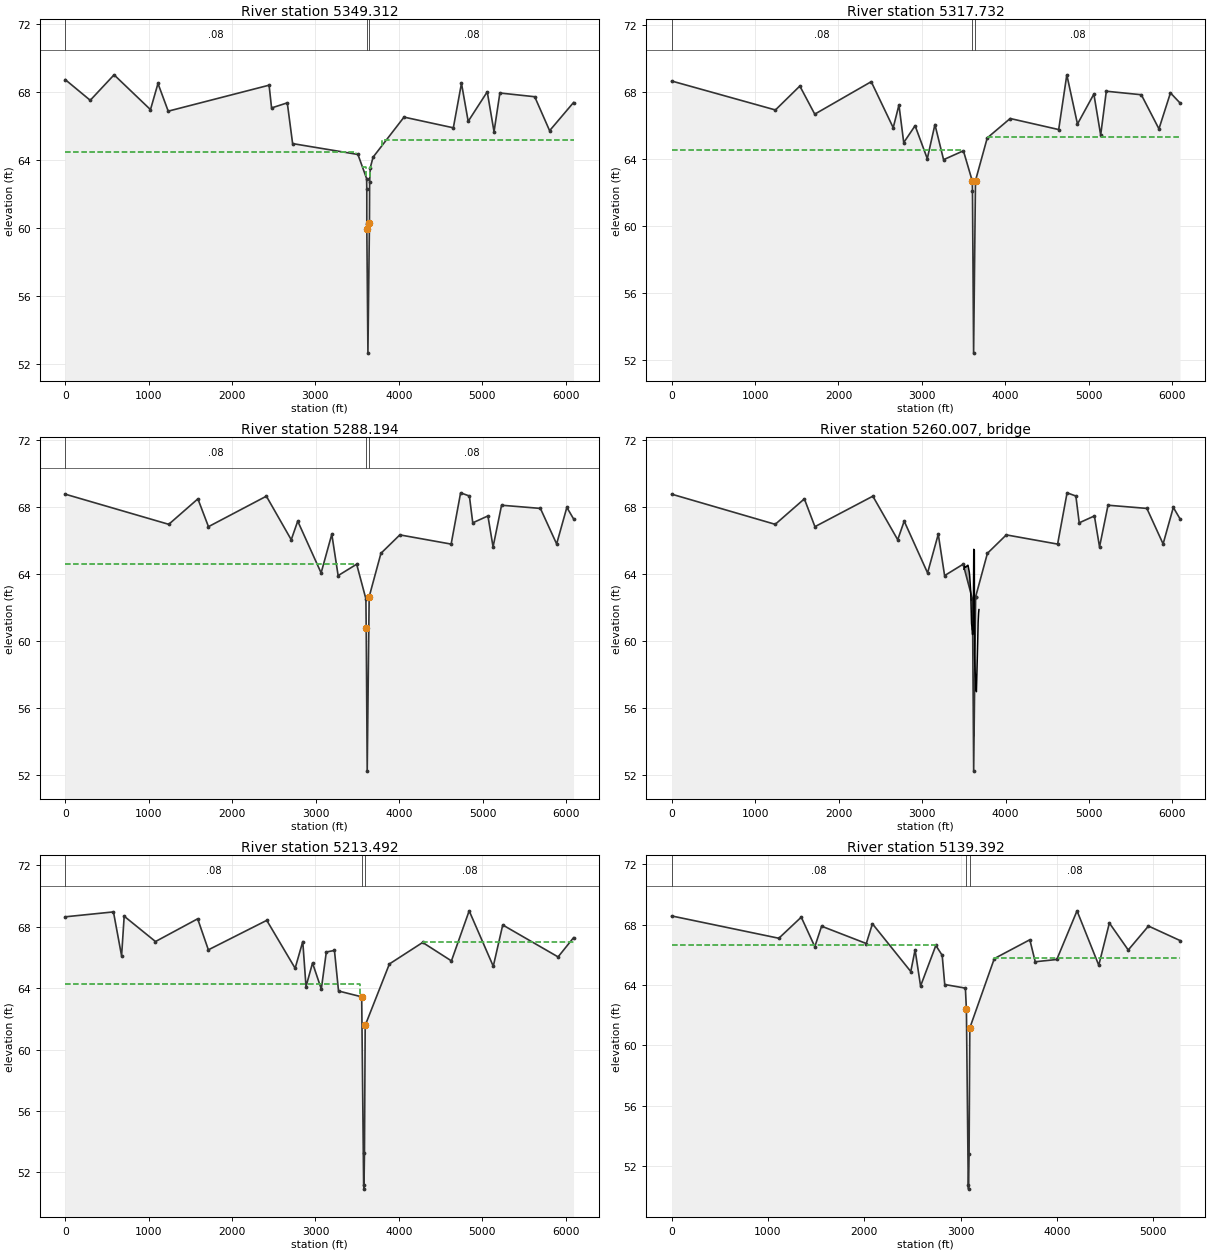
Type RM Length L Ch R = 1 ,5349.312,31.77,31.58,29.94
BEGIN DESCRIPTION:
Stations 3613.95 - 3668.09 developed from survey information (copied from cross-section 5317.73), and the remainder developed from LiDAR. The elevation of survey points adjusted to match the overall stream slope of approx. .0064 ft/ft.
END DESCRIPTION:
XS GIS Cut Line= 6
     3078387.588    13847986.375      3077068.41    13844814.925
     3077065.801     13844774.53     3077048.861    13844562.374
     3077047.859    13843822.377     3076404.072    13842285.033
#Sta/Elev= 30
       0   68.75  300.09   67.53  585.83   69.03 1022.38   66.98 1112.38   68.52
  1235.1   66.89 2444.55   68.42 2474.23   67.08 2662.77   67.38 2726.65   64.98
 3509.75   64.34 3613.95   62.92 3616.15   62.28 3616.34   60.22 3616.46   59.94
  3629.6   52.64 3647.91    60.3 3649.93   62.73 3658.64   63.57 3691.25   64.18
 4062.49   66.54 4653.76   65.91 4751.34   68.53 4831.69   66.29 5060.32   68.03
 5141.63   65.68 5211.87   67.96 5629.49   67.74 5808.09   65.74 6094.88    67.4
#Mann= 3 ,-1 , 0
       0     .08       0 3616.34     .06       0 3647.91     .08       0
#XS Ineff= 4 ,-1
       0 3481.44   64.49 3564.48  3601.8   63.62 3652.86 3676.42   63.62
 3798.74 6094.88   65.22
Permanent Ineff=
       F       F       F       F
Bank Sta=3616.46,3647.91
XS Rating Curve= 0
Exp/Cntr=.5,.3

Type RM Length L Ch R = 1 ,5317.732,29.68,29.54,29.42
BEGIN DESCRIPTION:
Stations 3604.98 - 3659.12 developed from survey information, and the remainder developed from LiDAR
END DESCRIPTION:
XS GIS Cut Line= 6
     3078418.234    13847987.074     3077095.784    13844825.875
     3077095.221    13844786.788     3077070.322     13844474.95
     3077069.885    13843830.472     3076428.375    13842285.887
#Sta/Elev= 30
       0   68.66 1244.16   66.93 1536.83   68.36 1715.69   66.68 2392.95   68.62
 2656.62   65.87  2725.4   67.23 2782.72   64.98 2918.91   65.99 3065.24   64.02
 3156.79   66.06 3260.36   63.96 3498.35   64.49 3604.98   62.68 3606.99    62.1
 3620.64    52.4 3643.08   62.69 3643.32   62.71 3784.24   65.26 4059.28   66.42
  4640.9   65.76 4738.35   69.03 4866.14   66.09 5062.75   67.88 5144.41   65.43
 5211.94   68.05 5631.68   67.84 5843.12    65.8 5981.03   67.95 6095.57   67.35
#Mann= 3 ,-1 , 0
       0     .08       0 3606.99     .06       0 3643.08     .08       0
#XS Ineff= 2 , 0
         3492.88   64.52 3788.59           65.29
Permanent Ineff=
       F       F
Bank Sta=3604.98,3643.32
XS Rating Curve= 0
Exp/Cntr=.5,.3

Type RM Length L Ch R = 1 ,5288.194,84.14,74.7,79.67
BEGIN DESCRIPTION:
Stations 3602.67 - 3656.82 developed from survey information (copied from cross-section 5317.73), and the remainder developed from LiDAR. The elevation of survey points adjusted to match the overall stream slope of approx. .0064 ft/ft.
END DESCRIPTION:
XS GIS Cut Line= 6
     3078440.682    13847987.586     3077128.634     13844853.25
     3077124.716    13844787.755     3077092.572    13844385.201
     3077092.868    13843840.522     3076457.811    13842286.923
#Sta/Elev= 30
       0   68.74 1240.61   66.94 1589.67   68.46 1716.41    66.8 2410.27   68.62
 2708.21   66.02  2785.9   67.13 3066.09   64.04 3194.19   66.35 3269.98   63.88
 3492.04   64.56 3602.67   62.49 3606.36   60.73 3606.42   60.68 3618.32   52.21
  3641.8    62.6 3641.99   62.62 3782.95   65.21 4009.36   66.31 4623.98   65.76
 4737.41   68.82  4842.6   68.63 4882.96   67.03 5064.72   67.44 5126.33   65.59
 5228.05   68.08 5693.49   67.89 5887.95   65.77 6010.24   67.95 6090.38   67.27
#Mann= 3 ,-1 , 0
       0     .08       0 3606.42     .06       0  3641.8     .08       0
#XS Ineff= 2 , 0
       0 3489.09   64.59 3898.11       0   65.66
Permanent Ineff=
       F       F
Bank Sta=3606.36,3641.99
XS Rating Curve= 0
Exp/Cntr=.5,.3

Type RM Length L Ch R = 3 ,5260.007,,,
BEGIN DESCRIPTION:
Structure 8 - Bridgewood
END DESCRIPTION:
Bridge Culvert--1,0,-1,-1, 0
Deck Dist Width WeirC Skew NumUp NumDn MinLoCord MaxHiCord MaxSubmerge Is_Ogee
18,22.5,2.6,45, 39, 40, , , .95, 0, 0,0,,
 3501.73 3507.73 3511.18 3518.36 3526.17 3539.62 3548.79 3551.52 3565.98 3571.49
 3572.44 3581.57 3582.12 3582.74 3592.75  3601.6 3603.37 3605.37 3605.71  3606.3
    3614 3618.65 3619.34 3624.31 3626.36    3628 3633.92 3635.25 3639.32 3642.12
 3642.55 3647.39 3651.21 3656.78 3662.26 3666.33 3671.78 3677.15 3681.45
   64.26   64.39   64.44   64.38   64.39   64.47    64.5   64.47   64.09   63.81
   63.73   63.01   62.99   62.93   61.02   60.61   60.43   60.36   60.38   60.43
   61.01   64.88   65.45   65.41   65.39   59.19   58.39   58.21   57.87   57.75
   57.69   57.03   56.95   58.04   59.07    59.9    61.1   61.63   61.85
                                                                                
           58.96   58.94   58.88   56.97   56.56   56.38   56.31   56.33   56.38
   56.96   60.83    61.4   61.36   61.34   55.14   54.34   54.16
                                                                        
    3460 3466.01 3472.01 3475.46 3482.64 3490.45  3503.9 3513.08  3515.8 3530.26
 3535.77 3536.72 3545.85  3546.4 3547.02 3557.03 3565.88 3567.65 3568.77 3582.93
 3588.59 3591.58 3592.28  3598.2 3599.53  3603.6  3606.4 3606.83 3611.67 3615.49
 3621.06 3626.54 3630.61 3636.06 3641.43 3645.74 3651.07 3656.31  3662.8 3663.31
   64.04   64.26   64.39   64.44   64.38   64.39   64.47    64.5   64.47   64.09
   63.81   63.73   63.01   62.99   62.93   61.02   60.61   60.43   65.33   65.34
   65.35   65.35   59.19   58.39   58.21   57.87   57.75   57.69   57.03   56.95
   58.04   59.07    59.9    61.1   61.63   61.85   62.28   62.56   63.09   63.12
                                                                                
                   58.96   58.94   58.88   56.97   56.56   56.38   61.28   61.29
    61.3    61.3   55.14   54.34   54.16   53.82    53.7   53.64   52.98
                                                                                
Pier Skew, UpSta & Num, DnSta & Num=  ,3623.029, 2 ,3573.154, 2 , 0 , 0 , 0 ,,
       1       1
    51.7    61.4
       1       1
    51.7    61.4
Pier Skew, UpSta & Num, DnSta & Num=  ,3626.246, 2 ,3575.247, 2 , 0 , 0 , 0 ,,
       1       1
   57.34    61.4
       1       1
   57.34    61.4
BR Coef=-1 , 1 , 1 ,1.25, 0 ,,,.8,-1,1.2,0,
WSPro=,,,, 1 ,,,, 0 ,,,, 0 ,,,,-1 ,-1 ,-1 , 0 , 0 , 0 , 0 , 0
BC Design=,, 0 ,, 0 ,,,,,,
BC HTab HWMax=69.06

Type RM Length L Ch R = 1 ,5213.492,69.04,74.1,75.35
BEGIN DESCRIPTION:
Stations 3542.53 - 3599.59 developed from survey information, and the remainder developed from LiDAR
END DESCRIPTION:
XS GIS Cut Line= 6
     3078460.662    13847988.042     3077183.383    13844924.424
     3077185.195    13844725.167      3077178.78    13844626.379
     3077179.055    13844020.707     3076477.845    13842287.628
#Sta/Elev= 30
       0   68.64  578.27   68.96  675.78    66.1  706.88   68.68 1082.07   67.03
 1587.59   68.51 1715.87   66.49 2415.85   68.41 2755.97   65.29 2847.41   67.03
 2886.39    64.1 2964.35   65.63 3069.61   63.94 3129.75   66.35 3227.26   66.45
 3276.01   63.81  3553.6   63.43 3553.73   63.38    3577   51.17 3580.72   50.91
 3586.95   53.23 3595.65   61.57 3885.69   65.57 4284.57   66.97 4629.36   65.77
 4841.96   69.03 5130.98   65.42 5244.24   68.11 5907.68   66.03 6092.87   67.28
#Mann= 3 ,-1 , 0
       0     .08       0 3553.73     .06       0 3595.65     .08       0
#XS Ineff= 2 , 0
       0 3539.01   64.27 4287.29       0   66.99
Permanent Ineff=
       F       F
Bank Sta=3553.6,3595.65
XS Rating Curve= 0
Exp/Cntr=.5,.3

Type RM Length L Ch R = 1 ,5139.392,89.2,103.36,109.03
BEGIN DESCRIPTION:
Stations 3520.77 - 3577.56 developed from survey information (copied from cross-section 5213.49), and the remainder developed from LiDAR. The elevation of survey points adjusted to match the overall stream slope of approx. .0064 ft/ft.
END DESCRIPTION:
XS GIS Cut Line= 6
     3078494.527    13847988.815     3077247.287    13844986.353
     3077247.287    13844750.276     3077251.395    13844643.723
     3077250.878    13844151.753       3076503.9    13842288.544
#Sta/Elev= 30
       0   68.581112.488    67.11345.249    68.51485.918   66.541556.248    67.9
2020.446   66.752084.055   68.062482.306   64.892526.845   66.332583.899   63.93
2742.356   66.622808.183   65.972834.735   64.033049.076   63.79 3059.72   62.38
3059.772   62.353078.781   50.713081.994   50.453087.363   52.773095.123   61.15
3349.301   65.753718.141      67 3774.13   65.543998.049   65.694207.983   68.92
4433.608   65.314543.879   68.114739.731   66.324949.586   67.915277.013   66.95
#Mann= 3 ,-1 , 0
       0     .08       03059.772     .06       03095.123     .08       0
#XS Ineff= 2 , 0
        2746.271   66.623347.327           65.79
Permanent Ineff=
       F       F
Bank Sta=3059.72,3095.123
XS Rating Curve= 0
Skew Angle= 30
Exp/Cntr=.5,.3

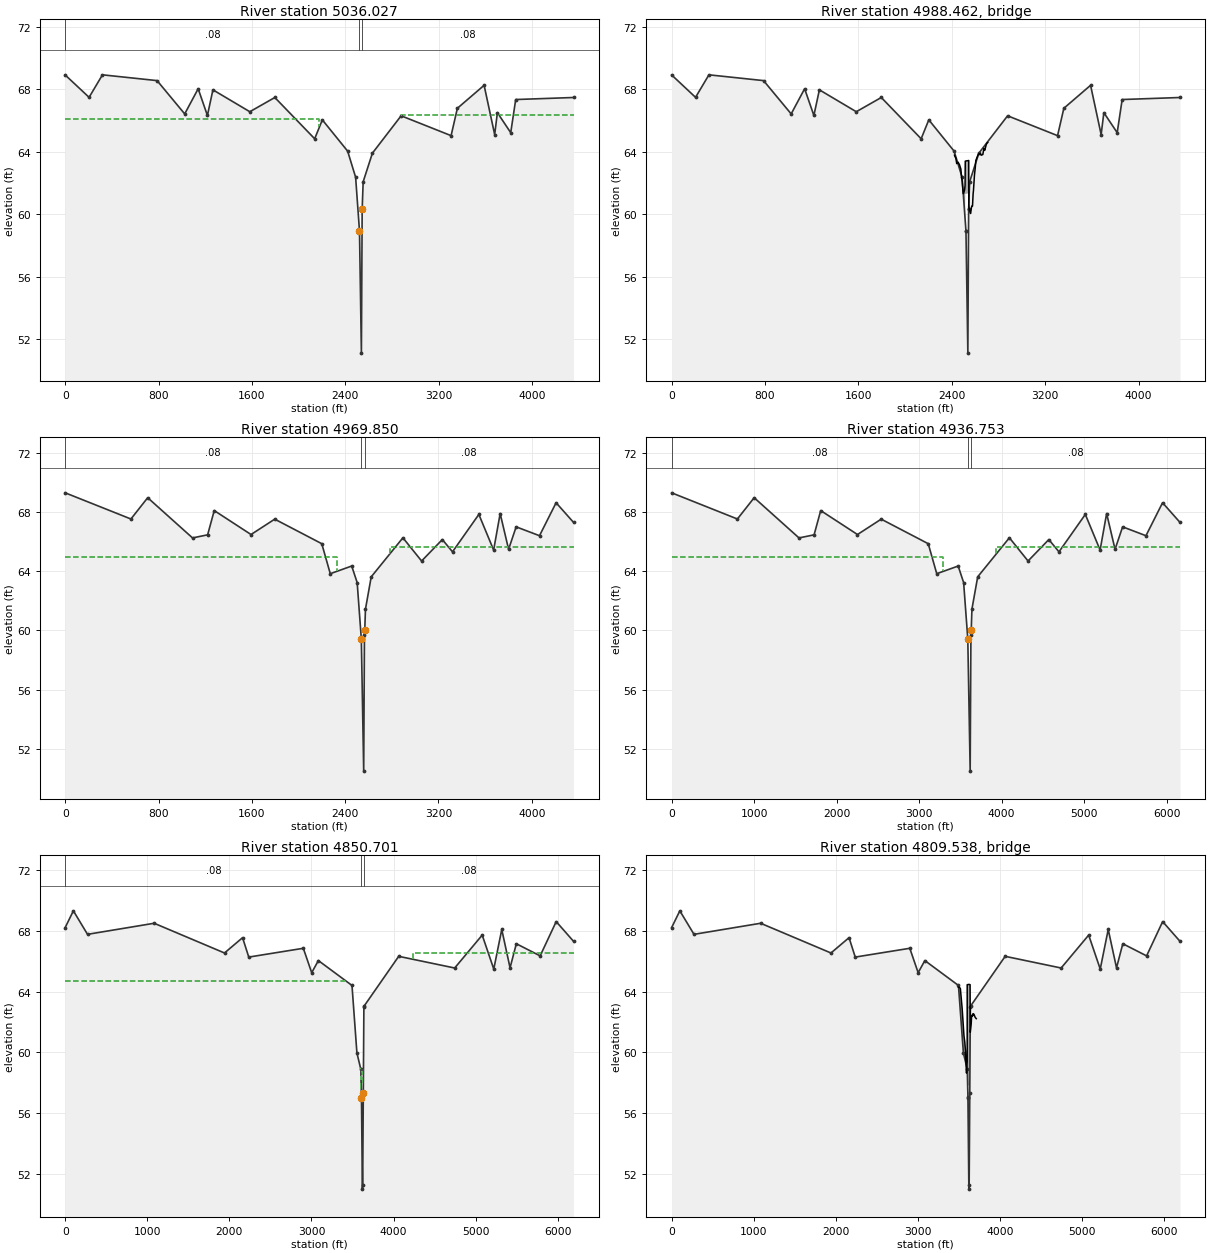
Type RM Length L Ch R = 1 ,5036.027,59.07,66.17,71.77
BEGIN DESCRIPTION:
Stations 3551.82 - 3610.49 developed from survey information, and the remainder developed from LiDAR
END DESCRIPTION:
XS GIS Cut Line= 6
     3078575.356    13847990.659     3077291.597    13844963.952
     3077291.219    13844800.384      3077368.23    13844635.359
     3077449.844    13844453.796     3076589.194    13842291.544
#Sta/Elev= 30
       0   68.91 204.587   67.48  319.16   68.92 787.229   68.551023.912   66.42
1139.213   68.031218.451   66.321265.686   67.961581.819   66.56 1796.15   67.47
2137.619   64.832203.189   66.042419.974   64.042488.443   62.372521.564   58.93
2521.606   58.912537.842   51.122544.474   60.332544.778   60.372553.002   62.08
2632.226   63.912878.377    66.33306.474   65.033360.271   66.783589.309   68.25
3679.918    65.13703.118    66.53817.436   65.223860.061   67.344355.559   67.47
#Mann= 3 ,-1 , 0
       0     .08       02521.564     .06       02544.474     .08       0
#XS Ineff= 2 , 0
        2177.408   66.122880.746           66.32
Permanent Ineff=
       F       F
Bank Sta=2521.606,2544.778
XS Rating Curve= 0
Skew Angle= 45
Exp/Cntr=.5,.3

Type RM Length L Ch R = 3 ,4988.462,,,
BEGIN DESCRIPTION:
Structure 7 - Pifer Road
END DESCRIPTION:
Bridge Culvert--1,0,-1,-1, 0
Deck Dist Width WeirC Skew NumUp NumDn MinLoCord MaxHiCord MaxSubmerge Is_Ogee
17,22.4,2.6,45, 56, 59, , , .95, 0, 0,0,,
2423.3892426.0412430.8422434.0242442.5452450.6982454.2482465.9222465.9432465.978
 2477.662481.9022489.3622489.8852491.003  2494.12497.8692501.0652509.8682513.828
2515.1932515.5612545.0472545.4222545.7472547.8832547.8972548.7522553.7662559.592
2561.7072566.2532569.1812571.2812577.7292582.8842585.7692594.4882601.8422606.092
2624.1722629.306 2638.012642.0272652.5132662.2432666.1322670.678 2675.722682.204
2696.8132697.9382698.5462698.9352700.6252708.304
   63.78   63.72   63.64   63.63   63.24   63.31   63.33   63.17   63.17   63.17
    62.9   62.51   62.09   62.07   61.93   61.66   61.33   61.33   61.56   61.84
   63.07    63.4   63.44   63.44   60.64   60.37   60.37   60.35   60.22   60.06
   60.05   60.35   60.44   60.52   60.53   61.31   61.51   62.51   63.03   63.44
   63.79   63.85   63.87   63.89   63.78   63.81   63.82   64.02   64.21   64.09
   64.49    64.5   64.52   64.52   64.54   64.59
                                                                                
                                                                                
   60.97    61.3   61.34
                                                                                
                                                                                
                                                
2444.8152447.4662452.2682455.449 2463.972472.1232475.6732487.3472487.3682487.404
2499.0852503.3282510.7882511.3112512.4282515.5252519.294 2522.492531.2942535.253
2536.6182538.8392539.4042545.9032547.9042563.0712566.4722567.1722569.3082569.322
2570.1772575.1912581.0182583.1322587.6782590.6062592.7062599.155 2604.312607.195
2615.9132623.2672627.5172645.5972650.7312659.4362663.4522673.9382683.6682687.557
2692.1042697.146 2703.632718.2392719.3632719.971 2720.36 2722.052729.729
   63.78   63.72   63.64   63.63   63.24   63.31   63.33   63.17   63.17   63.17
    62.9   62.51   62.09   62.07   61.93   61.66   61.33   61.33   61.56   61.84
   61.85   61.87   61.87   61.91   63.52   63.49   61.13   60.64   60.37   60.37
   60.35   60.22   60.06   60.05   60.35   60.44   60.52   60.53   61.31   61.51
   62.51   63.03   63.44   63.79   63.85   63.87   63.89   63.78   63.81   63.82
   64.02   64.21   64.09   64.49    64.5   64.52   64.52   64.54   64.59
                                                                                
                                                                                
   59.75   59.77   59.77   59.81   61.42   61.39   59.03
                                                                                
                                                                                
                                                                        
Pier Skew= 45
Pier Skew, UpSta & Num, DnSta & Num=  ,1783.25, 2 ,1807.305, 2 , 0 , 0 , 0 ,,
   16.55   16.55
   54.53   61.34
   16.55   16.55
   53.23   61.34
Pier Skew, UpSta & Num, DnSta & Num=  ,1798.98, 2 ,1812.05, 2 , 0 , 0 , 0 ,,
   16.55   16.55
   56.75   61.34
   16.55   16.55
   59.07   61.34
BR Coef=-1 , 1 , 1 ,1.25, 0 ,,,.8,-1,1.2,0,
WSPro=,,,, 1 ,,,, 0 ,,,, 0 ,,,,-1 ,-1 ,-1 , 0 , 0 , 0 , 0 , 0
BC Design=,, 0 ,, 0 ,,,,,,
BC HTab HWMax=69.07

Type RM Length L Ch R = 1 ,4969.850,33.88,33.1,31.8
BEGIN DESCRIPTION:
Stations 3582.12 - 3640.78 developed from survey information (copied from cross-section 5036.03), and the remainder developed from LiDAR. The elevation of survey points adjusted to match the overall stream slope of approx. .0064 ft/ft.
END DESCRIPTION:
XS GIS Cut Line= 6
     3078640.669    13848008.376     3077343.481    13844952.618
     3077344.074    13844813.345     3077441.781    13844602.823
     3077480.447    13844521.955 3076598.220361613842308.4629072
#Sta/Elev= 30
       0    69.3 563.486   67.53 707.262   68.971091.667   66.251221.089   66.46
1277.791    68.11593.182   66.481796.419   67.522199.717   65.862272.648   63.83
2456.397   64.352503.215   63.232538.824   59.422559.267   50.482565.694   59.67
2568.155   59.99 2574.42   61.442623.776   63.622895.461   66.263055.564   64.69
3233.444   66.143320.708   65.313546.543   67.843673.257   65.433729.232    67.9
3801.491   65.483866.248      674066.508    66.44208.785   68.634358.273    67.3
#Mann= 3 ,-1 , 0
       0     .08       02538.824     .06       02568.155     .08       0
#XS Ineff= 2 , 0
       0 2330.32   64.982782.677       0   65.63
Permanent Ineff=
       F       F
Bank Sta=2538.824,2568.155
XS Rating Curve= 0
Skew Angle= 45
Exp/Cntr=.5,.3

Type RM Length L Ch R = 1 ,4936.753,91.09,86.05,91.9
BEGIN DESCRIPTION:
Stations 3582.12 - 3640.78 developed from survey information (copied from cross-section 5036.03), and the remainder developed from LiDAR. The elevation of survey points adjusted to match the overall stream slope of approx. .0064 ft/ft.
END DESCRIPTION:
XS GIS Cut Line= 6
     3078670.779    13847992.836     3077373.591    13844937.077
     3077374.184    13844797.804     3077471.891    13844587.282
     3077510.557    13844506.414      3076628.33    13842292.921
#Sta/Elev= 30
       0    69.3  796.89   67.53 1000.22   68.97 1543.85   66.251726.881   66.46
1807.069    68.1  2253.1   66.48 2540.52   67.52 3110.87   65.86 3214.01   63.83
 3473.87   64.353540.081   63.233590.439   59.42 3619.35   50.483628.439   59.67
 3631.92   59.99 3640.78   61.443710.579   63.62  4094.8   66.26 4321.22   64.69
 4572.78   66.14 4696.19   65.315015.569   67.84 5194.77   65.43 5273.93    67.9
 5376.12   65.48  5467.7      675750.911    66.45952.121   68.636163.529    67.3
#Mann= 3 ,-1 , 0
       0     .08       03590.439     .06       0 3631.92     .08       0
#XS Ineff= 2 , 0
         3295.57   64.98  3935.3           65.63
Permanent Ineff=
       F       F
Bank Sta=3590.439,3631.92
XS Rating Curve= 0
Exp/Cntr=.5,.3

Type RM Length L Ch R = 1 ,4850.701,255.39,196.13,167.761
BEGIN DESCRIPTION:
Stations 3582.65 - 3685.57 developed from survey information, and the remainder developed from LiDAR
END DESCRIPTION:
XS GIS Cut Line= 6
     3078785.163    13847995.785     3077479.275    13844937.094
     3077478.993    13844702.073     3077574.514    13844613.716
     3076849.372    13842809.823      3076639.22    13842293.689
#Sta/Elev= 30
       0   68.24   99.47   69.34  271.81   67.79 1083.66   68.52 1940.59   66.56
 2160.63   67.57 2236.07   66.29  2900.7   66.87 3002.64   65.26 3084.19   66.06
 3493.59   64.42 3553.59   59.97 3600.89    58.9    3609   57.08 3609.12      57
 3620.44   50.99 3623.87   51.26 3631.47   57.36 3638.52   63.01 3643.86   63.08
 4062.65   66.34 4744.57   65.57 5079.93   67.74 5220.75    65.5 5318.12   68.11
 5419.12   65.58 5495.58   67.17  5785.6   66.37  5981.2   68.63 6192.41   67.33
#Mann= 3 ,-1 , 0
       0     .08       0    3609     .06       0 3643.86     .08       0
#XS Ineff= 4 ,-1
       0 3435.47   64.71 3596.35 3607.12   58.96 3632.26  3633.8   58.96
 4238.36 6192.41   66.53
Permanent Ineff=
       F       F       F       F
Bank Sta=3609.12,3631.47
XS Rating Curve= 0
Exp/Cntr=.5,.3

Type RM Length L Ch R = 3 ,4809.538,,,
BEGIN DESCRIPTION:
Structure 6 - private concrete drive
Survey data used in the vicinity of the main channel. The top of the railing was used as the road profile. Outside of the surveyed area, lidar information was used to define the roadway profile. The height of the railing above the natural ground is the reason for the sharp drop in roadway profile at the edges of the surveyed area.
END DESCRIPTION:
Bridge Culvert--1,0,-1,-1, 0
Deck Dist Width WeirC Skew NumUp NumDn MinLoCord MaxHiCord MaxSubmerge Is_Ogee
28,13,2.6,0, 33, 32, , , .95, 0, 0,0,,
    3493 3505.82 3516.64 3517.54 3518.38 3538.77 3538.81 3539.89 3559.25    3560
 3560.82 3570.62 3579.68 3582.91 3590.34 3591.84 3600.11 3600.17 3623.31 3635.34
 3637.38 3638.81 3648.81 3653.04 3661.83 3666.13 3670.71 3682.41  3687.1 3687.92
 3692.61 3696.78 3710.42
    64.3    64.3   64.21   64.19   64.12   62.89   62.88    62.8   61.22   61.17
    61.1   60.68   60.07   59.55   58.79   58.64   59.41   64.47   64.49   64.47
   61.33    61.4   61.88   62.34   62.48   62.41   62.56   62.52   62.46   62.44
   62.38   62.32   62.23
                                                                                
                                                           57.82   57.84   57.82
                                                                                
                        
    3029 3091.04 3101.86 3102.76  3103.6 3123.99 3124.03 3125.11 3144.47 3145.22
 3146.04 3155.84  3164.9 3168.13 3177.06 3178.69 3185.33 3216.27 3219.52  3222.6
 3224.03 3234.03 3238.26 3247.05 3251.35 3255.93 3267.63 3272.32 3273.14 3277.83
    3282 3295.64
   64.25    64.3   64.21   64.19   64.12   62.89   62.88    62.8   61.22   61.17
    61.1   60.68   60.07   59.55   58.64    60.1   60.74    63.7   61.18   61.33
    61.4   61.88   62.34   62.48   62.41   62.56   62.52   62.46   62.44   62.38
   62.32   62.23
                                                                                
                                                   54.09   57.05   54.53
                                                                                
                
BR Coef=-1 , 1 , 0 ,, 0 ,,,.8,-1,1.2,0,
WSPro=,,,, 1 ,,,, 0 ,,,, 0 ,,,,-1 ,-1 ,-1 , 0 , 0 , 0 , 0 , 0
BC Design=,, 0 ,, 0 ,,,,,,
BC HTab HWMax=69.34