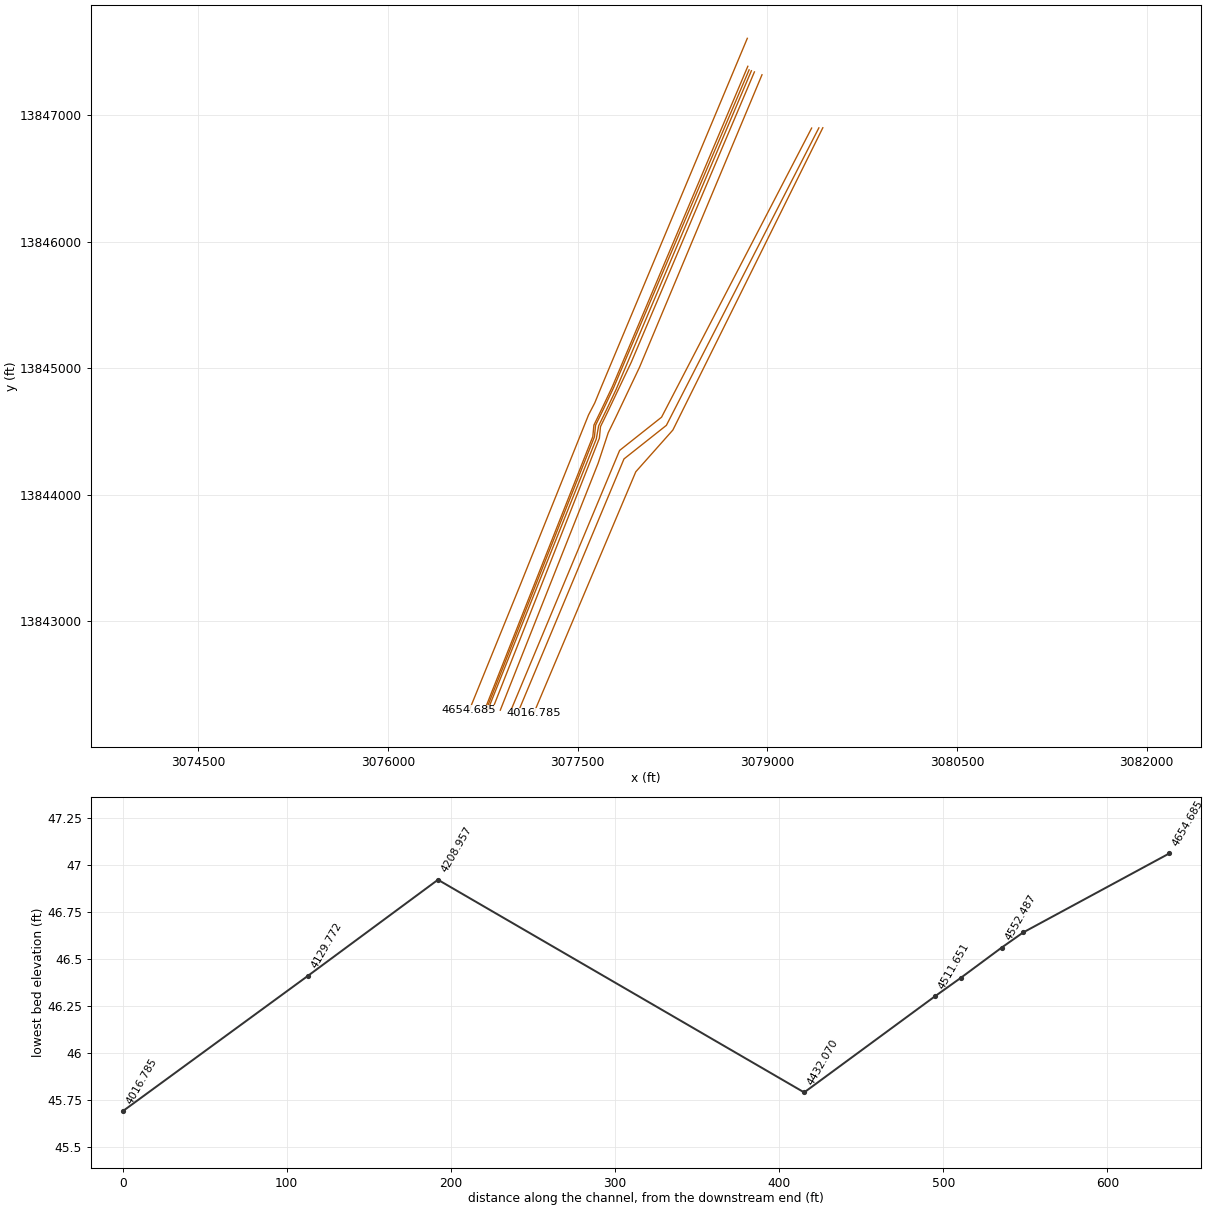
HEC-RAS study W141-00-00.prj: W141-00-00

--- W141-00-00.g01 (geometry) --- (continued)

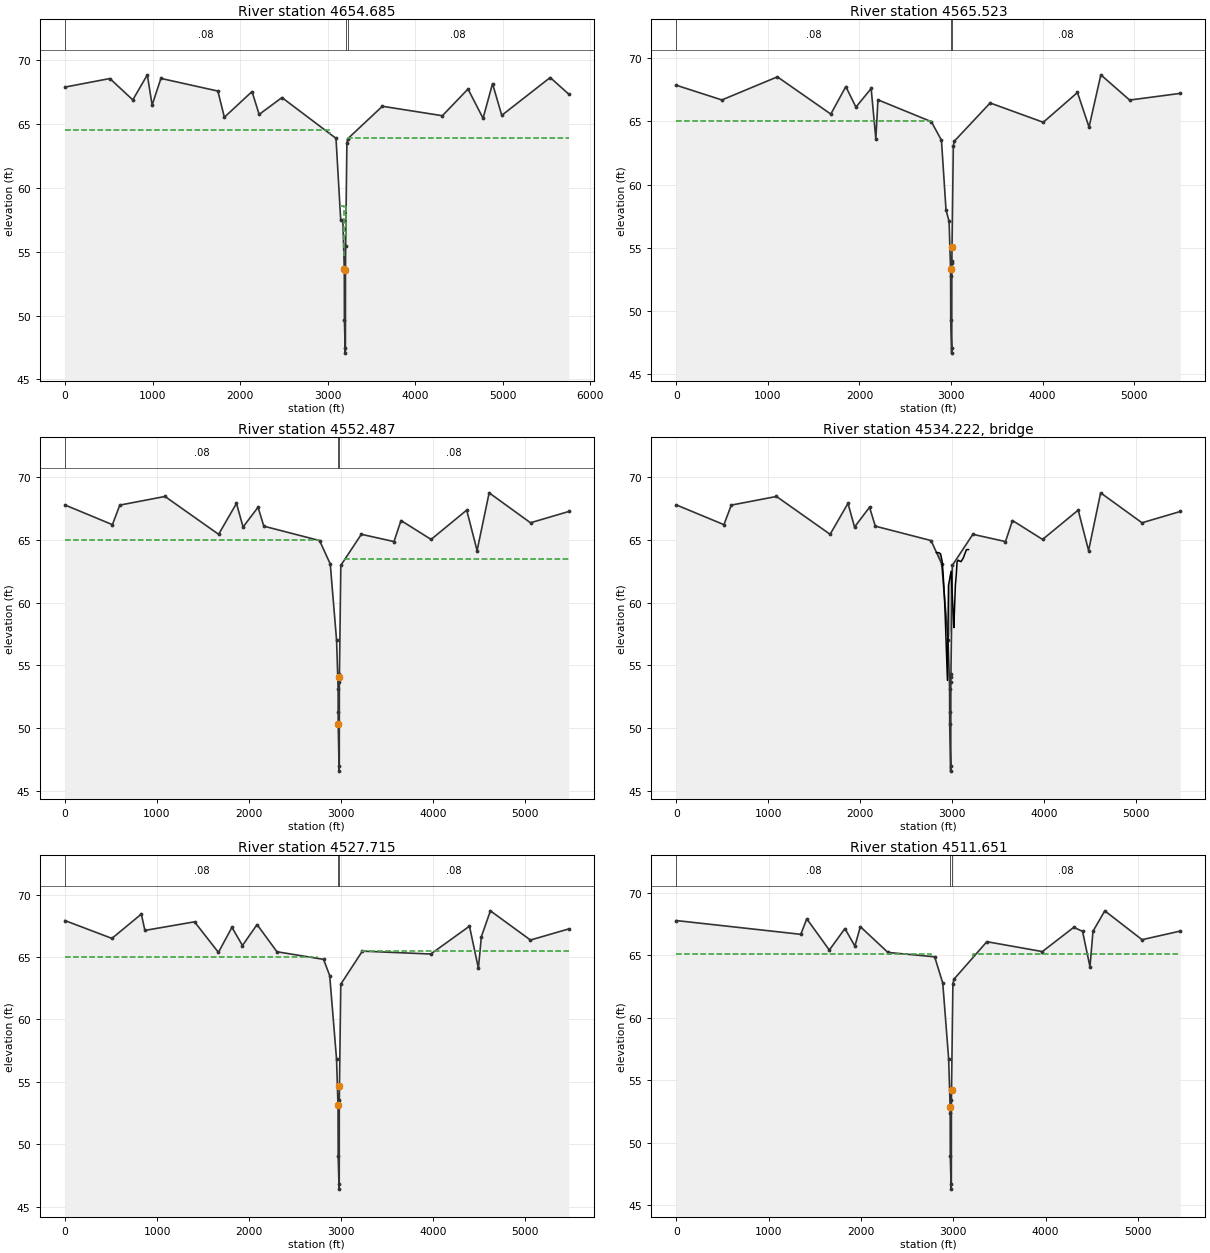
Type RM Length L Ch R = 1 ,4654.685,81.18,89.07,77.12
BEGIN DESCRIPTION:
Stations 3174.24 - 3230.82 developed from survey information (copied from cross-section 4565.523), and the remainder developed from LiDAR
END DESCRIPTION:
XS GIS Cut Line= 6
     3078841.778    13847610.127     3077686.602    13844852.025
     3077635.129    13844726.335      3077586.05    13844631.768
     3077045.208    13843285.122     3076641.759    13842293.393
#Sta/Elev= 30
       0   67.88  512.54   68.55  774.74   66.88  940.71   68.84   995.4   66.47
 1095.91   68.56 1746.41   67.57 1820.66   65.52 2136.71   67.53 2218.02   65.74
 2478.22   67.06 3095.85   63.87 3149.97   57.47 3174.24   57.49 3190.68   53.66
 3192.04   49.69 3201.87   47.06 3203.53    47.5  3204.2    53.6 3206.27   55.43
 3220.24   63.48 3230.38   63.84 3625.75   66.38 4311.29   65.64 4603.85   67.73
 4775.81   65.44 4884.03   68.15  4989.7   65.67 5542.96   68.63 5754.46   67.33
#Mann= 3 ,-1 , 0
       0     .08       0 3206.27     .06       0 3230.38     .08       0
#XS Ineff= 4 ,-1
       0 3023.31   64.51 3137.34 3187.04   58.55 3207.71 3211.67   58.55
 3232.36 5754.46   63.91
Permanent Ineff=
       F       F       F       F
Bank Sta=3190.68,3204.2
XS Rating Curve= 0
Exp/Cntr=.5,.3

Type RM Length L Ch R = 1 ,4565.523,13.11,13.04,12.83
BEGIN DESCRIPTION:
Stations 2979.25 - 3035.85 developed from survey information, and the remainder developed from LiDAR
END DESCRIPTION:
XS GIS Cut Line= 6
     3078845.783    13847388.779     3077773.591    13844853.455
     3077688.543    13844674.276     3077628.328    13844550.747
     3077619.357    13844459.167     3076764.281    13842297.566
#Sta/Elev= 30
       0   67.86  496.23    66.7 1102.86   68.53 1686.59   65.58 1850.63   67.76
 1961.29   66.13  2127.5   67.61 2178.76    63.6 2201.65   66.71 2784.85   64.98
 2895.68   63.51  2945.5   57.99 2979.25   57.07 2995.48   53.28 2996.03   52.75
 2997.06   49.27 3006.89   46.64 3008.55   47.08 3009.28   53.75 3009.63   53.96
 3011.39   55.07 3025.26   63.06 3035.85   63.43  3427.7   66.46 4008.41   64.93
 4382.15   67.29 4508.47   64.55 4637.52   68.69 4952.27   66.69 5505.08   67.22
#Mann= 3 ,-1 , 0
       0     .08       0 2996.03     .06       0 3009.63     .08       0
#XS Ineff= 2 , 0
          2783.8   65.06 3044.67           63.47
Permanent Ineff=
       F       F
Bank Sta=2995.48,3011.39
XS Rating Curve= 0
Exp/Cntr=.5,.3

Type RM Length L Ch R = 1 ,4552.487,25.13,24.77,24.72
BEGIN DESCRIPTION:
Stations 2953.63 - 3010.23 developed from survey information (copied from cross-section 4565.523), and the remainder developed from LiDAR. The elevation of survey points adjusted to match the overall stream slope of approx. .0064 ft/ft.
END DESCRIPTION:
XS GIS Cut Line= 6
     3078855.806    13847360.478     3077783.255    13844844.861
     3077701.598    13844672.825     3077641.383    13844549.296
     3077632.412    13844457.717     3076775.891    13842297.941
#Sta/Elev= 30
       0    67.8  516.01   66.23  596.04   67.79 1087.62   68.48 1670.67   65.46
 1865.01   67.93 1936.31   66.04 2099.38   67.62 2162.25   66.11 2768.55   64.96
 2884.78   63.09 2953.63   56.99 2970.28   53.13 2970.83   51.24 2971.11   50.31
 2981.27   46.56 2982.93      47 2983.66   53.67 2984.26   54.04 2984.69   54.32
 2999.64   62.98 3222.82   65.46 3577.82   64.88    3654   66.56 3981.23   65.05
 4368.42   67.39 4481.46   64.16 4612.55   68.77 5062.38   66.38 5478.01   67.28
#Mann= 3 ,-1 , 0
       0     .08       0 2970.83     .06       0 2984.69     .08       0
#XS Ineff= 2 , 0
         2765.43   64.98 3040.25           63.46
Permanent Ineff=
       F       F
Bank Sta=2971.11,2984.26
XS Rating Curve= 0
Exp/Cntr=.5,.3

Type RM Length L Ch R = 3 ,4534.222,,,
BEGIN DESCRIPTION:
Structure 5 - private wood walkway
Survey data used in the vicinity of the main channel. The top of the railing was used as the road profile. Outside of the surveyed area, lidar information was used to define the roadway profile. The height of the railing above the natural ground is the reason for the sharp drop in roadway profile at the edges of the surveyed area.
END DESCRIPTION:
Bridge Culvert--1,0,-1,-1, 0
Deck Dist Width WeirC Skew NumUp NumDn MinLoCord MaxHiCord MaxSubmerge Is_Ogee
9,5.1,2.6,0, 41, 41, , , .95, 0, 0,0,,
 2825.44 2829.28 2847.99  2861.1 2872.38 2888.02 2888.38 2888.55 2888.99 2900.21
 2904.39 2913.49 2920.39 2922.21 2925.44 2926.52 2946.78 2953.63 2957.93 2986.38
 3016.45 3016.76 3017.47 3032.83 3043.54 3048.89 3051.28  3057.5 3062.86  3062.9
 3064.82 3066.78 3092.59 3094.82  3119.8 3124.82 3127.41 3151.98 3154.83 3154.88
 3175.44
      64      64      64   63.96   63.89   63.35   63.34   63.33   63.29   62.27
   61.71    60.5   59.29   58.93   58.25   58.02    53.8   58.46   61.38   62.52
   58.01   58.12   58.28   61.36   62.31   62.96   63.26   63.32    63.4    63.4
   63.39   63.37   63.28   63.28   63.58   63.67   63.74   64.21   64.24   64.24
   64.24
                                                                                
                                                           53.86   56.78   57.92
   53.41
                                                                                
        
 2821.21 2825.05 2843.76 2856.87 2868.15 2883.79 2884.15 2884.32 2884.76 2895.98
 2900.16 2909.26 2916.16 2917.98 2921.21 2922.29 2942.55  2949.4  2953.7 2982.15
 3012.22 3012.53 3013.24  3028.6 3039.31 3044.66 3047.05 3053.27 3058.63 3058.67
 3060.59 3062.55 3088.36 3090.59 3115.57 3120.59 3123.18 3147.75  3150.6 3150.65
 3171.21
   64.41   64.41      64   63.96   63.89   63.35   63.34   63.33   63.29   62.27
   61.71    60.5   59.29   58.93   58.25   58.02    53.8   58.46   61.38   62.52
   58.01   58.12   58.28   61.36   62.31   62.96   63.26   63.32    63.4    63.4
   63.39   63.37   63.28   63.28   63.58   63.67   63.74   64.21   64.24   64.24
   64.24
                                                                                
                                                           53.86   56.82   58.08
   53.41
                                                                                
        
BR Coef=-1 , 0 , 0 ,, 0 ,,,.8,-1,,0,
WSPro=,,,, 1 ,,,, 0 ,,,, 0 ,,,,-1 ,-1 ,-1 , 0 , 0 , 0 , 0 , 0
BC Design=,, 0 ,, 0 ,,,,,,
BC HTab HWMax=68.77

Type RM Length L Ch R = 1 ,4527.715,16.01,16.06,16.52
BEGIN DESCRIPTION:
Stations 2949.41 - 3006 developed from survey information (copied from cross-section 4565.523), and the remainder developed from LiDAR. The elevation of survey points adjusted to match the overall stream slope of approx. .0064 ft/ft.
END DESCRIPTION:
XS GIS Cut Line= 6
     3078873.971    13847353.582     3077803.769    13844832.311
     3077725.773     13844667.99     3077665.559    13844544.461
     3077647.115    13844441.048     3076789.607    13842298.383
#Sta/Elev= 30
       0   67.92  509.81   66.49  829.31   68.44  868.13   67.13 1406.72   67.82
 1666.78   65.37 1813.44   67.38 1927.51   65.92 2086.24    67.6  2302.3   65.42
 2808.75   64.81 2875.17   63.51 2949.41   56.83 2965.25   53.11 2965.58   53.05
 2967.22   49.03 2977.04    46.4 2978.71   46.84 2979.44   53.51 2981.06   54.53
 2981.23   54.63 2995.42   62.82 3229.87   65.47 3973.08   65.24 4393.15   67.47
 4490.09    64.1  4522.4   66.63 4620.55    68.7 5055.57   66.36 5471.25   67.25
#Mann= 3 ,-1 , 0
       0     .08       0 2965.58     .06       0 2981.06     .08       0
#XS Ineff= 2 , 0
         2741.34   64.99 3226.71           65.49
Permanent Ineff=
       F       F
Bank Sta=2965.25,2981.23
XS Rating Curve= 0
Exp/Cntr=.5,.3

Type RM Length L Ch R = 1 ,4511.651,77.28,79.58,78.55
BEGIN DESCRIPTION:
Stations 2949.73 - 3006.33 developed from survey information (copied from cross-section 4565.523), and the remainder developed from LiDAR. The elevation of survey points adjusted to match the overall stream slope of approx. .0064 ft/ft.
END DESCRIPTION:
XS GIS Cut Line= 6
       3078897.9    13847344.498     3077924.267    13845048.899
      3077740.66    13844662.078     3077680.446    13844538.549
     3077671.475    13844446.969     3076824.328    13842299.503
#Sta/Elev= 30
       0   67.79 1347.14   66.69 1412.31   67.93 1656.71   65.43 1825.47   67.15
  1933.7   65.75 1992.97    67.3 2292.15   65.24 2798.24   64.89 2886.06   62.79
 2949.73   56.73 2966.19    52.9 2966.52   52.38 2967.54   48.93 2977.37    46.3
 2979.03   46.74 2979.76   53.41 2981.04   54.21  2981.1   54.25 2995.74   62.72
 3006.33   63.09 3363.99    66.1 3965.66   65.31  4305.8   67.25 4401.03   66.93
 4481.66   64.09 4513.91   66.93 4642.01   68.57 5046.03   66.26 5459.69   66.95
#Mann= 3 ,-1 , 0
       0     .08       0 2966.52     .06       0 2981.04     .08       0
#XS Ineff= 2 , 0
         2753.29   65.09 3217.11           65.15
Permanent Ineff=
       F       F
Bank Sta=2966.19,2981.1
XS Rating Curve= 0
Exp/Cntr=.3,.1

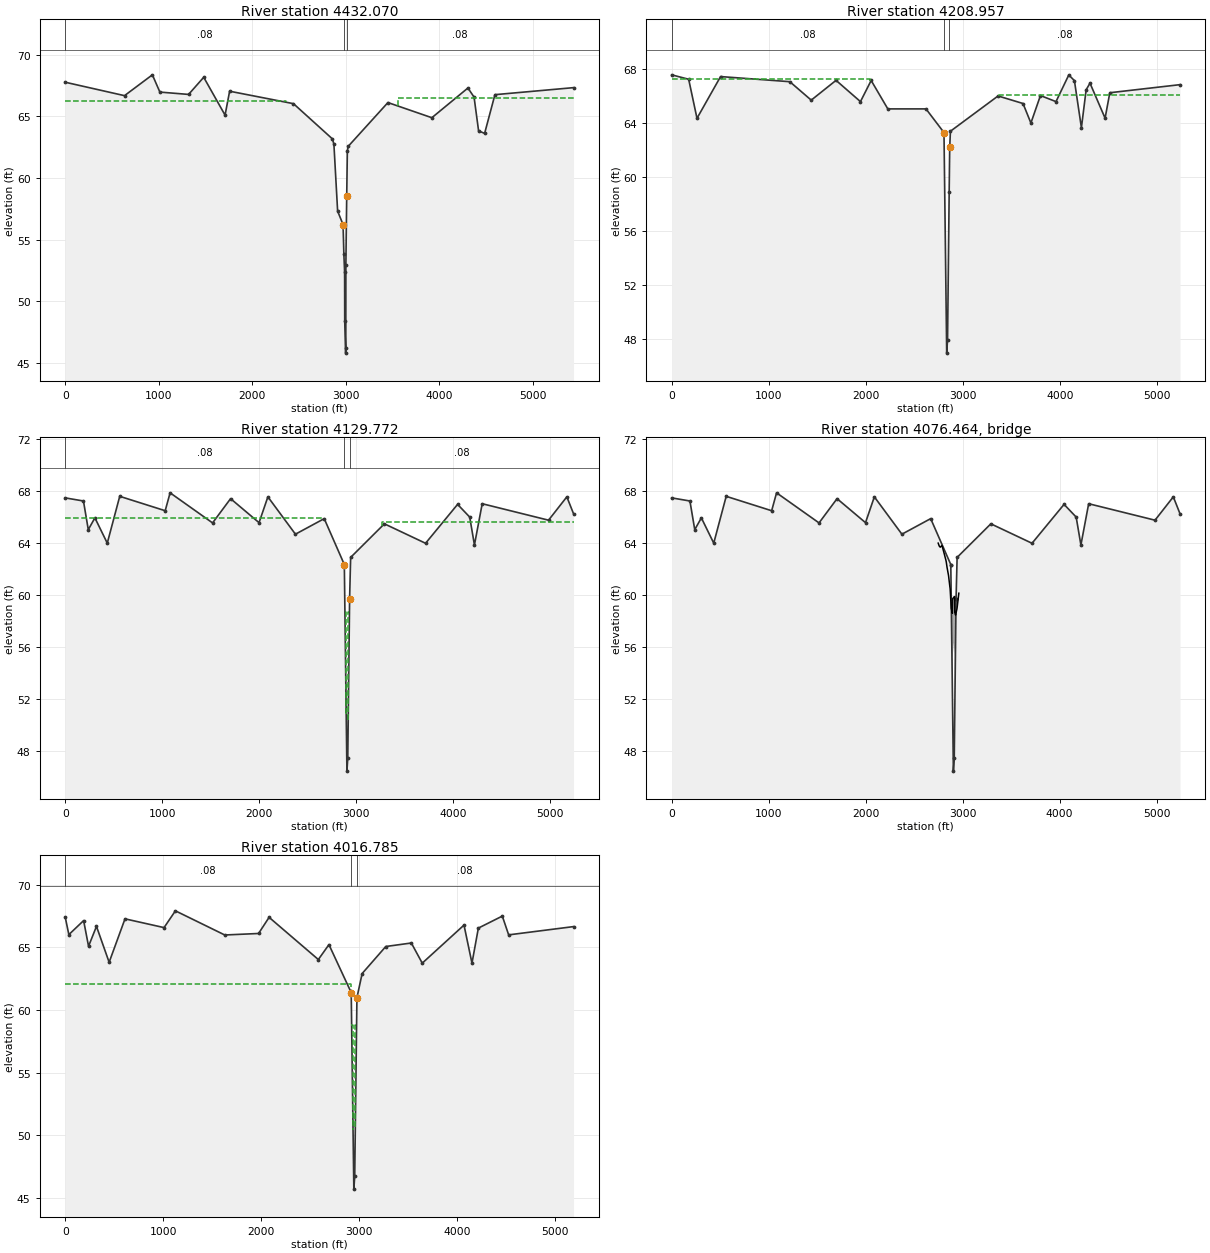
Type RM Length L Ch R = 1 ,4432.070,242.06,223.16,201.37
BEGIN DESCRIPTION:
Stations 2972.46 - 3029.05 developed from survey information (copied from cross-section 4565.523), and the remainder developed from LiDAR. The elevation of survey points adjusted to match the overall stream slope of approx. .0064 ft/ft.
END DESCRIPTION:
XS GIS Cut Line= 6
     3078957.863    13847321.734     3077989.977    13845010.055
     3077801.649    13844613.287     3077741.434    13844489.758
     3077661.464    13844248.115     3076887.529    13842295.144
#Sta/Elev= 30
       0   67.77  634.53   66.68  932.55   68.37 1012.79   66.97 1319.84   66.78
 1481.73   68.17 1710.12    65.1  1758.9   67.04  2441.9   66.03 2858.67   63.17
 2874.53   62.74 2914.33   57.31 2972.46   56.22 2981.12   53.81  2989.1   52.36
 2990.26   48.42 3000.09   45.79 3001.76   46.23 3002.48    52.9 3011.57   58.55
 3018.47   62.21 3029.05   62.58 3452.41   66.12 3922.24   64.89 4308.21    67.3
 4374.01   66.56 4422.42   63.82 4486.96   63.62  4597.1   66.76 5438.01   67.33
#Mann= 3 ,-1 , 0
       0     .08       0 2981.12     .06       0 3011.57     .08       0
#XS Ineff= 2 , 0
         2358.03   66.26 3564.06           66.45
Permanent Ineff=
       F       F
Bank Sta=2972.46,3011.57
XS Rating Curve= 0
Exp/Cntr=.3,.1

Type RM Length L Ch R = 1 ,4208.957,82.5,79.17,78.35
BEGIN DESCRIPTION:
Stations 2799.38 - 2871.45 developed from survey information (copied from cross-section 4016.785) , and the remainder developed from LiDAR. The elevation of survey points adjusted to match the overall stream slope of approx. .0064 ft/ft.
END DESCRIPTION:
XS GIS Cut Line= 6
     3079350.639    13846900.242     3079062.106    13846344.361
     3078163.447    13844613.019     3078006.387    13844488.611
     3077831.592    13844350.154     3076968.845    13842287.399
#Sta/Elev= 30
       0   67.59  175.17   67.26  260.81   64.36  503.62   67.46 1217.08   67.08
 1437.58   65.71 1693.21   67.18 1944.59    65.6 2054.98   67.17 2226.44   65.06
 2619.72   65.06  2805.1    63.3 2833.03   46.92 2841.86   47.93 2858.57    58.9
 2864.03   62.21 2871.45    63.4 3362.17   66.02  3619.1   65.46  3700.4   64.01
 3798.73   66.05 3958.94    65.6 4090.61   67.58 4148.67   67.16 4220.69   63.66
 4269.47   66.48 4309.17   66.97 4464.58   64.37 4513.35   66.26 5236.24   66.86
#Mann= 3 ,-1 , 0
       0     .08       0  2805.1     .06       0 2858.57     .08       0
#XS Ineff= 2 , 0
         2046.92   67.29 3368.64           66.11
Permanent Ineff=
       F       F
Bank Sta=2805.1,2864.03
XS Rating Curve= 0
Exp/Cntr=.5,.3

Type RM Length L Ch R = 1 ,4129.772,104.69,112.96,118.16
Node Photo=V:\TSARP\GIS\W141_00_00\Photos\w141-00-00s4\w141-00-s4p1.JPG
BEGIN DESCRIPTION:
Stations 2871.13 - 2943.2 developed from survey information (copied from cross-section 4016.785) , and the remainder developed from LiDAR. The elevation of survey points adjusted to match the overall stream slope of approx. .0064 ft/ft.
END DESCRIPTION:
XS GIS Cut Line= 6
     3079407.792    13846901.766     3079073.302    13846249.199
     3078201.584    13844548.541     3078040.958    13844421.307
     3077866.163    13844282.851     3077029.271    13842281.644
#Sta/Elev= 30
       0   67.48  188.18   67.24  237.97   65.03  306.17   65.94  433.75   63.99
  562.19    67.6 1030.97   66.49 1081.54   67.87  1519.5   65.55  1705.2   67.42
 1998.68   65.57 2089.84   67.56 2373.93   64.68 2670.64   65.88 2878.06   62.34
 2878.16   62.27 2904.78   46.41 2913.61   47.42 2932.41   59.66 2932.51   59.72
  2943.2   62.89 3291.14   65.48 3715.62   63.98  4045.9   66.98 4170.86      66
 4219.64   63.85 4299.67   67.03  4983.8   65.76 5172.38   67.56  5241.4   66.26
#Mann= 3 ,-1 , 0
       0     .08       0 2878.06     .06       0 2932.51     .08       0
#XS Ineff= 4 ,-1
       0 2660.84   65.92 2883.87 2897.34   58.66 2918.08 2931.19   58.66
 3268.52  5241.4    65.6
Permanent Ineff=
       F       F       F       F
Bank Sta=2878.16,2932.41
XS Rating Curve= 0
Exp/Cntr=.5,.3

Type RM Length L Ch R = 3 ,4076.464,,,
BEGIN DESCRIPTION:
Structure 4 - Longshadows
END DESCRIPTION:
Bridge Culvert--1,0,-1,-1, 0
Deck Dist Width WeirC Skew NumUp NumDn MinLoCord MaxHiCord MaxSubmerge Is_Ogee
23,60,2.6,0, 29, 30, , , .95, 0, 0,0,,
 2748.14 2758.16 2762.56 2769.53 2782.32 2786.87 2788.67 2812.85 2827.99 2828.57
 2830.64 2839.25 2848.14 2854.79 2860.61 2865.21 2871.28 2882.49 2894.37 2896.88
 2897.87 2907.87 2917.87 2918.68 2919.01 2927.27 2941.75 2946.03 2960.89
   63.99   63.78   63.73   63.68   63.77    63.8   63.78    63.1   62.66   62.64
   62.57   62.13   61.76   61.49   61.12   60.83   60.46   58.97   58.58   59.69
   59.69   59.82   59.87   59.87   58.65   58.44   58.93   59.18   60.13
                                                                                
                                                                                
   55.19   56.32   55.37
 2787.92 2797.94 2802.34 2809.31  2822.1 2826.65 2828.45 2852.63 2867.77 2868.35
 2870.42 2879.03 2887.92 2894.57 2900.39 2904.99 2911.06 2924.13 2932.42 2934.56
 2936.41 2938.82 2948.82 2958.82 2961.14 2964.99 2973.79 2981.53 2985.81 3000.67
   63.78   63.78   63.73   63.68   63.77    63.8   63.78    63.1   62.66   62.64
   62.57   62.13   61.76   61.49   61.12   60.83   60.46   59.91   58.87   58.82
   59.68   59.68   59.71   59.75   59.75   58.51   58.65   58.93   59.18   60.13
                                                                                
                                                                                
           55.18   56.21   55.25
BR Coef=-1 , 0 , 0 ,, 0 ,,,.8,-1,,0,
WSPro=,,,, 1 ,,,, 0 ,,,, 0 ,,,,-1 ,-1 ,-1 , 0 , 0 , 0 , 0 , 0
BC Design=,, 0 ,, 0 ,,,,,,
BC HTab HWMax=67.87

Type RM Length L Ch R = 1 ,4016.785,78.66,73.31,71.86
Node Photo=V:\TSARP\GIS\W141_00_00\Photos\w141-00-00s4\w141-00-s4p8.JPG
BEGIN DESCRIPTION:
Stations 2910.39 - 2983.57 developed from survey information, and the remainder developed from LiDAR
END DESCRIPTION:
XS GIS Cut Line= 6
     3079439.128    13846902.622     3079073.302    13846165.233
     3078252.808    13844511.382     3078107.643    13844347.976
     3077959.547     13844181.27     3077151.945    13842269.961
#Sta/Elev= 30
       0   67.42    37.2   66.02   187.9   67.14  238.13   65.09  318.98   66.68
   448.2   63.81  609.97   67.28 1008.38   66.58 1124.18   67.92 1627.93   65.99
 1972.56   66.11 2080.03    67.4 2582.36   64.03 2690.56   65.22 2917.81   61.39
 2918.07   61.24 2944.56   45.69 2953.52    46.7 2975.99   60.95 2976.03   60.98
 3029.19   62.91 3270.46   65.07    3531   65.35 3642.49   63.74 4068.37   66.78
 4149.79   63.74 4214.85   66.54 4459.19    67.5 4523.93      66 5185.83   66.66
#Mann= 3 ,-1 , 0
       0     .08       0 2918.07     .06       0 2975.99     .08       0
#XS Ineff= 4 ,-1
       0  2911.7   62.11 2920.62 2936.45   58.79 2959.76 2973.83   58.79
 3063.63 5185.83   63.13
Permanent Ineff=
       F       F       F       F
Bank Sta=2917.81,2976.03
XS Rating Curve= 0
Exp/Cntr=.5,.3