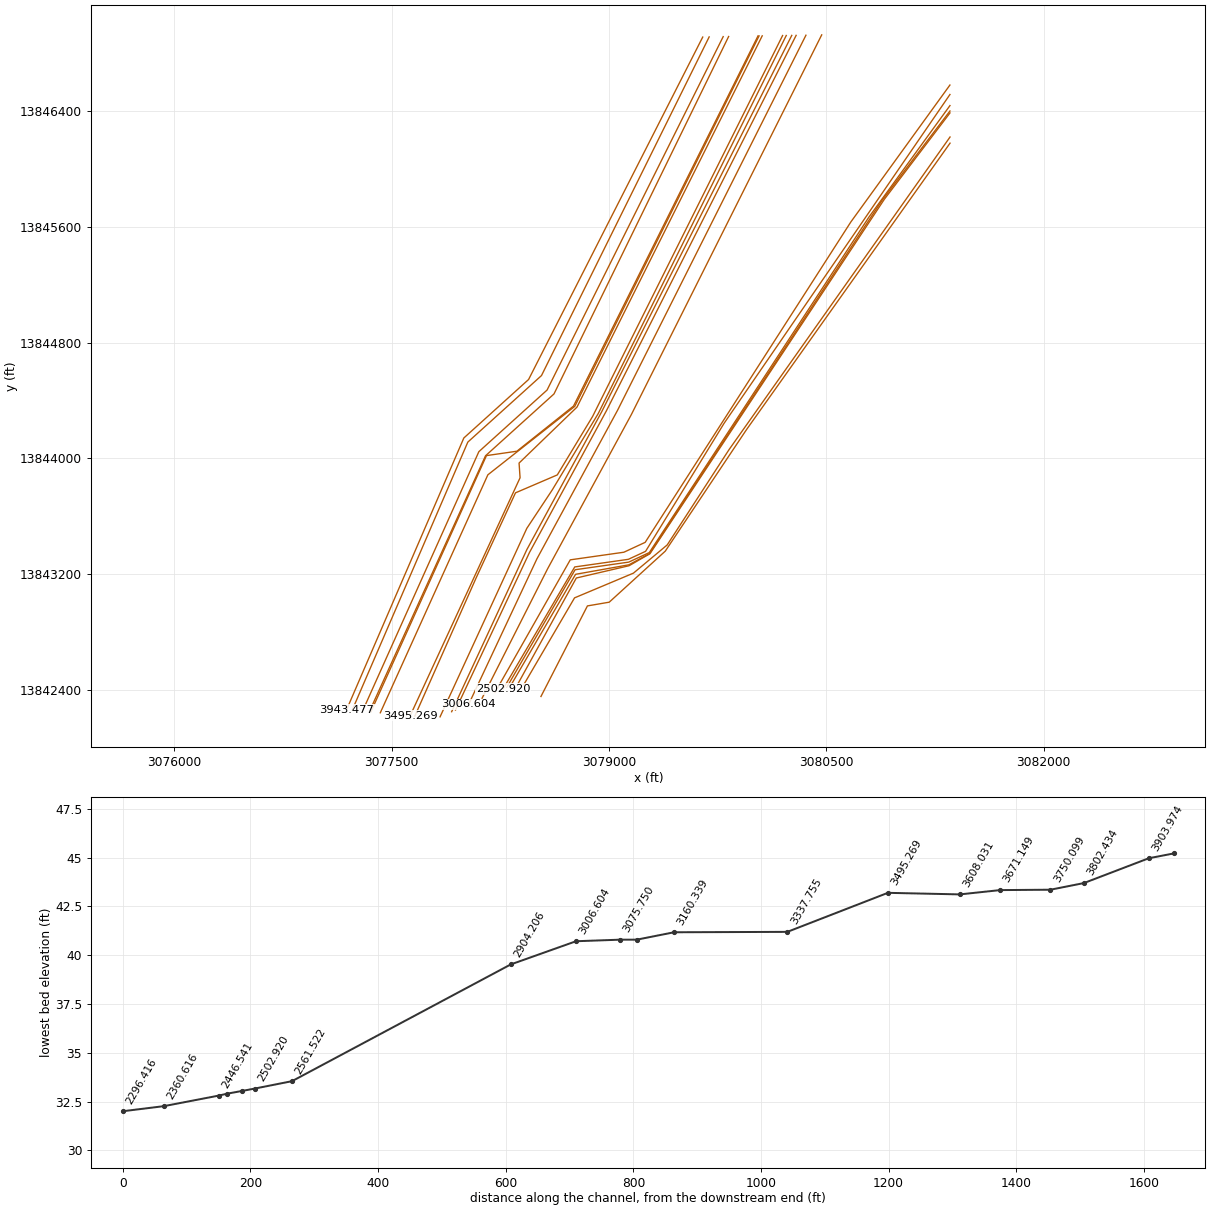
HEC-RAS study W141-00-00.prj: W141-00-00

--- W141-00-00.g01 (geometry) --- (continued)

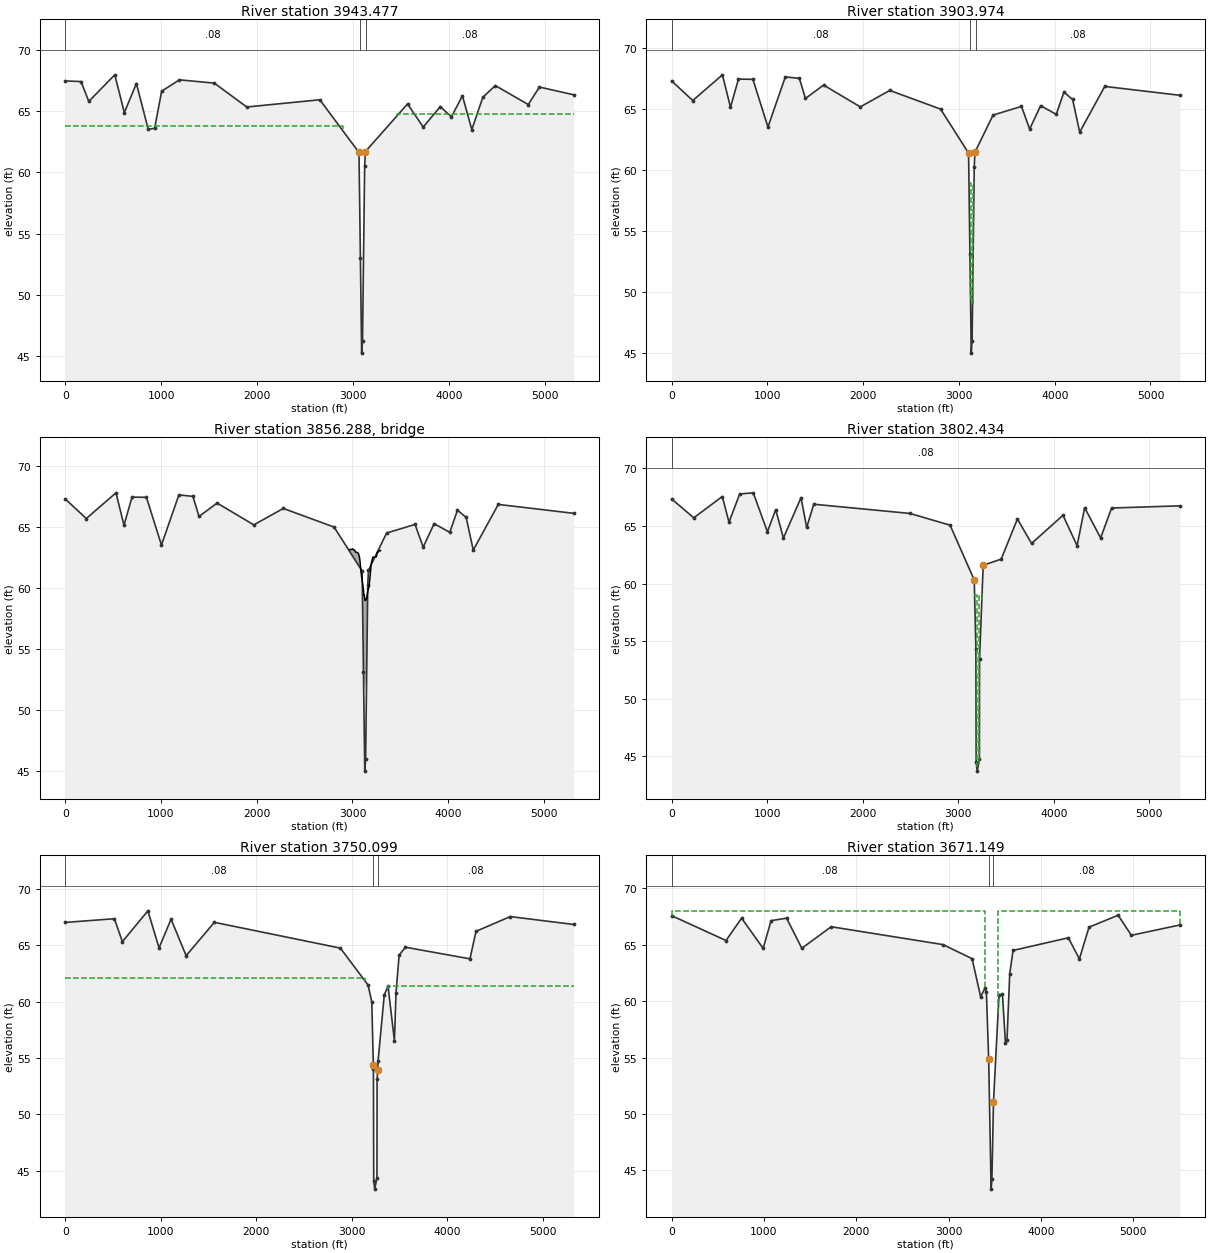
Type RM Length L Ch R = 1 ,3943.477,39.6,39.5,39.73
BEGIN DESCRIPTION:
Stations 3054.41 - 3127.15 developed from survey information (copied from cross-section 4016.785) , and the remainder developed from LiDAR. The elevation of survey points adjusted to match the overall stream slope of approx. .0064 ft/ft.
END DESCRIPTION:
XS GIS Cut Line= 6
      3079647.18    13846908.401      3079101.29    13845834.968
     3078445.125    13844544.688      3077998.25    13844141.059
     3077423.048    13842808.023      3077189.34      13842266.4
#Sta/Elev= 30
       0   67.48  164.61   67.43  245.81   65.81  516.47   67.98  616.03   64.89
  741.72   67.27  865.31   63.52  931.49   63.61 1004.92   66.64 1189.81   67.57
 1553.87    67.3 1891.13   65.35 2652.39   65.94 3060.58   61.63 3075.22   52.98
 3088.37   45.22 3097.28   46.23 3119.66   60.51 3127.15    61.7  3566.3    65.6
 3729.67   63.71  3907.8   65.38 4023.73   64.54 4138.09   66.27 4236.11    63.5
 4350.47   66.14 4481.16    67.1 4824.23   65.55 4940.33   66.98 5295.71   66.35
#Mann= 3 ,-1 , 0
       0     .08       0 3075.22     .06       0 3134.85     .08       0
#XS Ineff= 2 , 0
          2889.2   63.82 3452.26           64.81
Permanent Ineff=
       F       F
Bank Sta=3060.58,3127.15
XS Rating Curve= 0
Exp/Cntr=.5,.3

Type RM Length L Ch R = 1 ,3903.974,101.69,101.54,107.03
Node Photo=V:\TSARP\GIS\W141_00_00\Photos\w141-00-00s3\w141-00-s3p1.JPG
BEGIN DESCRIPTION:
Stations 3094.31 - 3167.05 developed from survey information (copied from cross-section 4016.785) , and the remainder developed from LiDAR. The elevation of survey points adjusted to match the overall stream slope of approx. .0064 ft/ft.
END DESCRIPTION:
XS GIS Cut Line= 6
     3079691.621    13846909.462     3078534.259    13844571.984
     3078253.639    13844318.521     3078179.429    13844251.492
     3078025.675    13844112.618     3077227.734    13842262.743
#Sta/Elev= 30
       0    67.3  219.98   65.69  530.22    67.8  613.91   65.14   697.6   67.45
  848.24   67.43 1005.19   63.52 1186.97   67.63 1333.64   67.51 1397.02   65.86
 1586.28   66.96 1969.68   65.17 2277.23   66.52 2807.98   64.99 3100.49   61.38
 3114.52   53.09 3128.27   44.97 3137.19   45.98 3159.56   60.26 3167.05   61.45
 3356.04    64.5 3653.04   65.21 3738.32   63.35 3852.67   65.27 4016.03   64.56
 4096.49   66.38 4186.94   65.78 4261.07    63.1 4522.45   66.85 5308.27   66.12
#Mann= 3 ,-1 , 0
       0     .08       0 3114.52     .06       0 3174.29     .08       0
#XS Ineff= 2 ,-1
 3104.57 3121.07   58.89 3141.94 3157.47   58.89
Permanent Ineff=
       F       F
Bank Sta=3100.49,3167.05
XS Rating Curve= 0
Exp/Cntr=.5,.3

Type RM Length L Ch R = 3 ,3856.288,,,
BEGIN DESCRIPTION:
Structure 3 - Smithdale
END DESCRIPTION:
Bridge Culvert--1,0,-1,-1, 0
Deck Dist Width WeirC Skew NumUp NumDn MinLoCord MaxHiCord MaxSubmerge Is_Ogee
21,68,2.6,0, 46, 44, , , .95, 0, 0,0,,
 2971.63 2985.63 2993.91 2998.52 3000.94 3008.74 3025.06 3031.11 3033.33 3036.98
 3054.55 3064.67 3074.76 3075.29 3075.87 3085.63 3085.91 3094.97 3110.35  3110.7
 3115.18 3117.77 3120.63 3121.49 3131.49 3141.49 3144.28 3149.63 3155.61 3158.58
 3165.39 3170.87 3175.82 3187.76 3192.82 3196.03 3210.14 3213.35 3216.25 3221.28
 3248.33 3263.08 3269.94 3277.28 3287.69 3292.82
   63.15   63.15   63.17   63.19   63.16   63.17   63.05   62.97   62.95   62.92
    62.9   62.77   62.43   62.42   62.38   61.62    61.6   60.91   60.11   60.09
   59.81   59.42   59.43   59.43   58.96   59.02   59.08   59.26   59.52   59.65
   59.93   60.03   60.34    61.3   61.74   62.01   62.44    62.5   62.54    62.5
   62.55      63   62.95   63.02   63.09   63.06
                                                                                
                                                                                
                            51.5   52.46    51.5
                                                                                
                                                
    2985 3053.03 3061.31 3065.92 3068.34 3076.14 3092.46 3098.51 3100.73 3104.38
 3121.95 3132.07 3142.16 3142.69 3143.27 3153.03 3153.31 3162.37 3177.75  3178.1
 3180.97 3192.78 3194.37 3204.37 3214.24 3217.03 3223.01 3225.98 3232.79 3238.27
 3243.22 3255.16 3260.22 3263.43 3277.54 3280.75 3283.65 3288.68 3315.73 3330.48
 3337.34 3344.68 3355.09 3360.22
   63.15   63.15   63.17   63.19   63.16   63.17   63.05   62.97   62.95   62.92
    62.9   62.77   62.43   62.42   62.38   61.62    61.6   60.91   60.11   60.09
   58.96   60.33   60.33   60.35   60.38   59.26   59.52   59.65   59.93   60.03
   60.34    61.3   61.74   62.01   62.44    62.5   62.54    62.5   62.55      63
   62.95   63.02   63.09   62.85
                                                                                
                                                                                
                   52.85   53.85   52.85
                                                                                
                                
BR Coef=-1 , 0 , 0 ,, 0 ,,,.8,-1,,0,
WSPro=,,,, 1 ,,,, 0 ,,,, 0 ,,,,-1 ,-1 ,-1 , 0 , 0 , 0 , 0 , 0
BC Design=,, 0 ,, 0 ,,,,,,
BC HTab HWMax=67.96

Type RM Length L Ch R = 1 ,3802.434,52.25,52.33,53.69
Node Photo=V:\TSARP\GIS\W141_00_00\Photos\w141-00-00s3\w141-00-s3p8.JPG
BEGIN DESCRIPTION:
Stations 3168.14 - 3233.5 developed from survey information, and the remainder developed from LiDAR
END DESCRIPTION:
XS GIS Cut Line= 6
     3079788.435    13846911.454     3078572.825    13844471.983
     3078329.822    13844252.496     3078176.068    13844113.622
     3078101.858    13844046.593     3077299.029    13842255.953
#Sta/Elev= 30
       0   67.34  231.45   65.71  529.93   67.56  600.15   65.33  712.32   67.78
   854.3   67.88 1002.37    64.5  1089.2   66.42 1169.96   63.95 1354.31   67.46
 1413.57   64.87 1487.95   66.89 2493.94   66.09 2915.15   65.07 3168.14   60.31
 3185.36   54.35  3188.3   44.45 3199.05    43.7  3222.2   44.72 3223.68   53.43
 3261.73   61.59 3450.41   62.12 3620.26   65.61 3768.21   63.48 4097.36   65.93
 4244.98   63.29 4324.35   66.59 4491.51   63.96 4606.58   66.56 5322.59   66.75
#Mann= 1 ,-1 , 0
       0     .08       0
#XS Ineff= 2 ,-1
 3170.65    3194   58.99 3215.35 3247.38   58.99
Permanent Ineff=
       F       F
Bank Sta=3168.14,3261.73
XS Rating Curve= 0
Exp/Cntr=.5,.3

Type RM Length L Ch R = 1 ,3750.099,101.38,78.95,51.26
BEGIN DESCRIPTION:
Stations 3210.45 - 3275.81 developed from survey information (copied from cross-section 3802.4343) , and the remainder developed from LiDAR. The elevation of survey points adjusted to match the overall stream slope of approx. .0064 ft/ft.
END DESCRIPTION:
XS GIS Cut Line= 6
        3079826.    13846912.227     3078620.463    13844445.022
     3078362.326    13844211.866     3078288.116    13844144.837
     3078147.892    13844018.184     3077345.905    13842251.489
#Sta/Elev= 30
       0   67.03  515.23   67.36  598.71   65.32  865.83   68.06  982.69   64.77
  1108.6   67.32 1266.41   64.08 1562.07   67.04 2881.44   64.75 3171.68   61.47
 3210.45   59.97 3226.69   54.35  3226.9   54.27 3227.67   54.01 3230.61   44.11
 3241.36   43.36 3264.51   44.38 3265.99   53.09 3271.94   53.93 3275.81    54.7
  3341.6   60.63 3381.12   61.35 3447.45   56.52 3463.92   60.77 3496.87   64.13
 3562.76   64.83 4238.16    63.8  4301.9   66.24 4660.03   67.55 5322.99   66.85
#Mann= 3 ,-1 , 0
       0     .08       0  3226.9     .06       0 3275.81     .08       0
#XS Ineff= 2 , 0
         3138.22   62.13 3384.41           61.38
Permanent Ineff=
       F       F
Bank Sta=3226.69,3271.94
XS Rating Curve= 0
Exp/Cntr=.3,.1

Type RM Length L Ch R = 1 ,3671.149,41.39,63.12,84.77
BEGIN DESCRIPTION:
Stations 3433.27 - 3492.57 developed from survey information, and the remainder developed from LiDAR. Station 3433.27 represents top of wood fence referenced in survey.
END DESCRIPTION:
XS GIS Cut Line= 6
      3080028.85    13846916.401     3078755.429    13844361.339
     3078364.546    13844049.721      3078203.01    13844026.381
     3078154.368    13844019.401     3077356.541    13842250.476
#Sta/Elev= 30
       0   67.57  588.94   65.37  757.62   67.35  991.17   64.67 1077.11   67.13
 1244.97   67.35 1410.16   64.68  1728.6   66.59 2938.49   65.01  3255.1   63.76
 3347.81   60.38 3394.72   61.16 3409.88   60.81 3434.69   54.84  3434.8   54.84
    3461   43.34 3469.73   44.22  3486.8   51.09 3546.28   60.53 3583.63    60.6
 3616.54   56.29 3632.99   56.54 3662.96   62.44 3698.81   64.49 4297.78   65.61
 4417.67   63.74 4521.57   66.55 4837.31   67.61 4980.47   65.83 5507.58   66.75
#Mann= 3 ,-1 , 0
       0     .08       0  3434.8     .06       0  3486.8     .08       0
#XS Ineff= 2 , 0
         3390.55      68 3536.47              68
Permanent Ineff=
       F       F
Bank Sta=3434.69,3486.8
XS Rating Curve= 0
Exp/Cntr=.8,.6

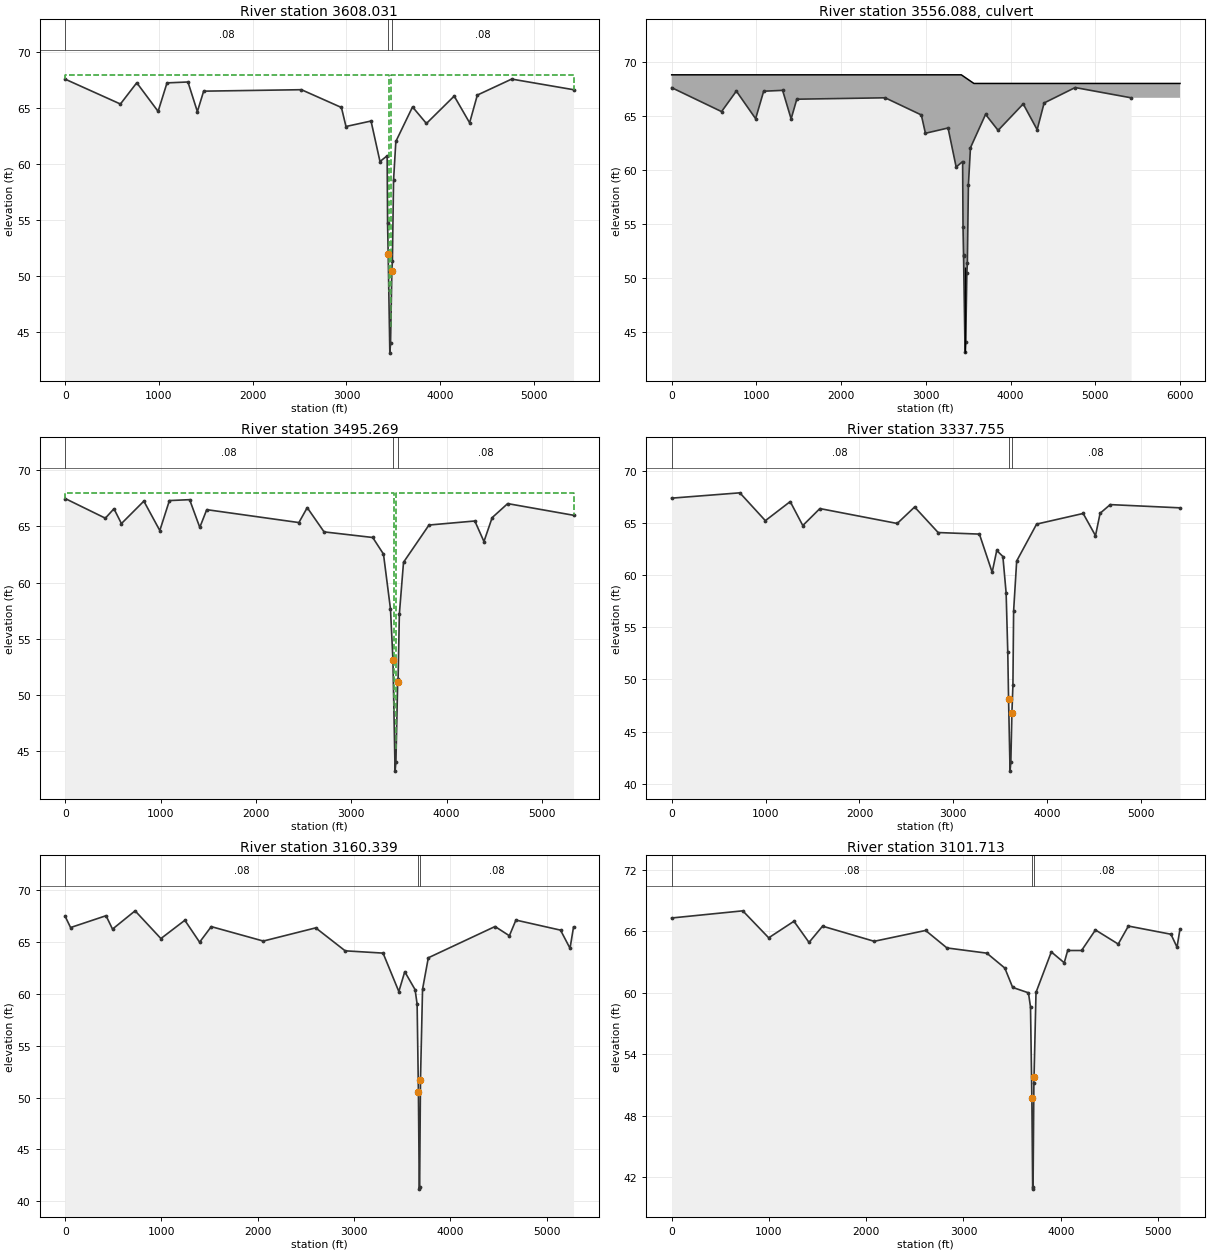
Type RM Length L Ch R = 1 ,3608.031,79.05,112.76,152.18
BEGIN DESCRIPTION:
Stations 3438.86 - 3490.21 developed from survey information (copied from cross-section 3671.149) , and the remainder developed from LiDAR. Station 3438.86 represents top of wood fence referenced in survey. The elevation of survey points adjusted to match the overall stream slope of approx. .0064 ft/ft.
END DESCRIPTION:
XS GIS Cut Line= 6
     3080036.155    13846916.551     3079358.786    13845555.081
     3078763.839    13844359.276      3078242.73    13843948.722
     3078164.106    13843886.929     3077421.655    13842244.275
#Sta/Elev= 30
       0   67.61   588.9   65.39  763.35   67.29     991   64.73 1085.93   67.28
 1309.32   67.36 1409.85   64.71 1476.86   66.54 2519.83   66.67 2946.61   65.08
 2994.94   63.38 3262.28   63.87 3357.76   60.25 3434.14   60.76 3438.86   54.72
 3445.15   52.06 3445.31   51.97 3462.88   43.12 3470.44      44 3484.24   50.42
 3490.21   51.39 3502.61    58.6 3526.86   62.04  3704.9   65.13 3853.05   63.65
 4149.34    66.1 4313.95   63.71 4396.26   66.19 4762.72   67.62 5422.36   66.67
#Mann= 3 ,-1 , 0
       0     .08       0 3445.15     .06       0 3484.24     .08       0
#XS Ineff= 2 , 0
         3451.96      68 3473.66              68
Permanent Ineff=
       F       F
Bank Sta=3445.31,3484.24
XS Rating Curve= 0
Exp/Cntr=.8,.6

Type RM Length L Ch R = 2 ,3556.088,,,
BEGIN DESCRIPTION:
Structure 2 - Voss
Survey data was used to define the road (fence in this case) profile in the vicinity of the main channel. Outside of the surveyed area, the profile was extended horizontally becuase this profile represents a large wooden fence that extends along Voss St. This assumption appeared to be the most appropriate for this structure.
END DESCRIPTION:
Bridge Culvert--1,0,-1,-1, 0
Deck Dist Width WeirC Skew NumUp NumDn MinLoCord MaxHiCord MaxSubmerge Is_Ogee
7,100,2.6,20, 6, 6, , , .95, 0, 0,0,,
       0  3418.7 3567.39 3606.64 3619.54    6000
    68.8    68.8      68      68      68      68
                                                
       0 3414.75 3563.44 3602.69 3615.59    6000
    68.8    68.8      68      68      68      68
                                                
Culvert=2,8,8,100,.013,.4,1,8,1,43,3462.7,41.5,3458.75,Culvert #1  , 0 ,7
Culvert Bottom n=.013
BC Design=,, 0 ,, 0 ,,,,,,
BC HTab HWMax=67.68

Type RM Length L Ch R = 1 ,3495.269,204.43,157.51,112.87
BEGIN DESCRIPTION:
Stations 3431.18 - 3490.48 developed from survey information (copied from cross-section 3671.149) , and the remainder developed from LiDAR. The elevation of survey points adjusted to match the overall stream slope of approx. .0064 ft/ft.
END DESCRIPTION:
XS GIS Cut Line= 6
     3080057.832    13846916.997     3079375.579    13845549.484
     3078779.278    13844354.252     3078379.458    13843968.001
     3078386.321    13843866.428     3077628.157    13842224.608
#Sta/Elev= 30
       0   67.49  420.88   65.74  511.16   66.58  589.56   65.26  824.52   67.26
  992.04   64.64 1092.62   67.31 1304.71   67.39 1411.12   64.92 1484.13    66.5
 2450.43   65.35 2537.69   66.68 2714.33   64.52 3224.57   64.02 3337.31   62.54
 3410.83   57.64 3436.49   53.11 3436.54   53.08 3458.93    43.2 3467.59   44.01
 3486.11   51.14 3490.48   51.39 3503.79    57.2 3547.41   61.81 3814.45   65.13
 4295.08   65.49 4390.89   63.66 4476.82   65.79 4639.55   67.04 5330.12      66
#Mann= 3 ,-1 , 0
       0     .08       0 3436.49     .06       0 3486.11     .08       0
#XS Ineff= 2 , 0
       0  3446.7      68  3470.7       0      68
Permanent Ineff=
       F       F
Bank Sta=3436.54,3486.11
XS Rating Curve= 0
Exp/Cntr=.8,.6

Type RM Length L Ch R = 1 ,3337.755,158.58,177.42,190.62
BEGIN DESCRIPTION:
Stations 3577.16 - 3634.44 developed from survey information (copied from cross-section 3671.149) , and the remainder developed from LiDAR. The elevation of survey points adjusted to match the overall stream slope of approx. .0064 ft/ft.
END DESCRIPTION:
XS GIS Cut Line= 6
     3080198.466    13846919.008      3078886.98     13844289.63
     3078643.329    13843886.131     3078354.761    13843762.453
     3078082.944    13843174.935     3077660.023    13842221.573
#Sta/Elev= 30
       0   67.39  726.04    67.9  997.79   65.23 1262.44   67.06 1396.54   64.76
 1578.57   66.39 2402.28   64.96 2587.41   66.54  2838.1   64.09 3277.53   63.94
 3413.35   60.28 3462.31   62.37 3527.59   61.79 3562.13   58.29 3579.61   52.63
 3588.08   48.09 3588.19   48.04 3603.96    41.2 3612.38   42.08 3623.59   46.75
 3623.65   46.77 3634.44   49.47 3641.84   56.56 3674.47   61.36 3886.86    64.9
  4382.6   65.92 4513.92   63.79 4563.11   65.94 4670.74   66.77 5413.92   66.46
#Mann= 3 ,-1 , 0
       0     .08       0 3588.19     .06       0 3623.65     .08       0
Bank Sta=3588.08,3623.59
XS Rating Curve= 0
Exp/Cntr=.3,.1

Type RM Length L Ch R = 1 ,3160.339,55.58,58.62,60.15
BEGIN DESCRIPTION:
Stations 3634.58 - 3729.37 developed from survey information (copied from cross-section 3006.349) , and the remainder developed from LiDAR. The elevation of survey points adjusted to match the overall stream slope of approx. .0064 ft/ft.
END DESCRIPTION:
XS GIS Cut Line= 6
     3080223.794    13846919.335     3078925.728    13844309.361
     3078608.871    13843783.154     3078553.677    13843699.765
     3078433.021    13843517.477     3077834.104    13842216.142
#Sta/Elev= 30
       0   67.43   55.88   66.36  424.09    67.5  491.45   66.21  725.99   67.97
  994.04    65.3 1242.78   67.06  1396.1   64.95 1517.14   66.45 2057.82   65.06
  2602.3   66.33 2908.13   64.12 3301.72    63.9 3465.65    60.2 3527.12   62.11
 3634.58   60.38 3655.57   58.99 3668.99   50.54 3677.88   41.18 3681.75   41.39
 3690.58   51.71 3690.64   51.73 3711.89   60.42 3771.85   63.45  4465.1   66.46
 4613.92   65.57 4681.77   67.08  5145.4   66.11 5243.83   64.36 5280.33   66.41
#Mann= 3 ,-1 , 0
       0     .08       0 3668.99     .06       0 3690.58     .08       0
Bank Sta=3668.99,3690.64
XS Rating Curve= 0
Exp/Cntr=.3,.1

Type RM Length L Ch R = 1 ,3101.713,25.64,25.96,25.56
Node Photo=V:\TSARP\GIS\W141_00_00\Photos\w141-00-00s1\w141-00-s1p1.JPG
BEGIN DESCRIPTION:
Stations 3668.35 - 3763.5 developed from survey information (copied from cross-section 3006.349) , and the remainder developed from LiDAR. The elevation of survey points adjusted to match the overall stream slope of approx. .0064 ft/ft.
END DESCRIPTION:
XS GIS Cut Line= 6
     3080261.616    13846919.823     3078949.004     13844320.61
     3078638.286    13843748.345      3078590.57    13843660.463
     3078433.105    13843370.453     3077914.118    13842251.576
#Sta/Elev= 30
       0   67.32  731.12   68.02  997.64   65.38 1257.16      67 1412.22   64.93
 1551.41   66.52 2082.15   65.04 2610.84    66.1 2830.25   64.39  3240.3   63.88
 3425.39   62.42 3505.79   60.53 3668.35      60 3689.42   58.61 3703.28   49.75
 3711.81    40.8 3715.69   41.01 3724.12   51.16 3725.86   51.81 3745.95   60.04
 3903.31      64  4036.2   62.94 4071.46   64.14 4214.44   64.14 4357.03   66.15
 4591.19   64.77 4695.67   66.53 5133.38   65.73 5195.85   64.46 5226.41   66.25
#Mann= 3 ,-1 , 0
       0     .08       0 3703.28     .06       0 3725.86     .08       0
Bank Sta=3703.28,3725.86
XS Rating Curve= 0
Exp/Cntr=.5,.3

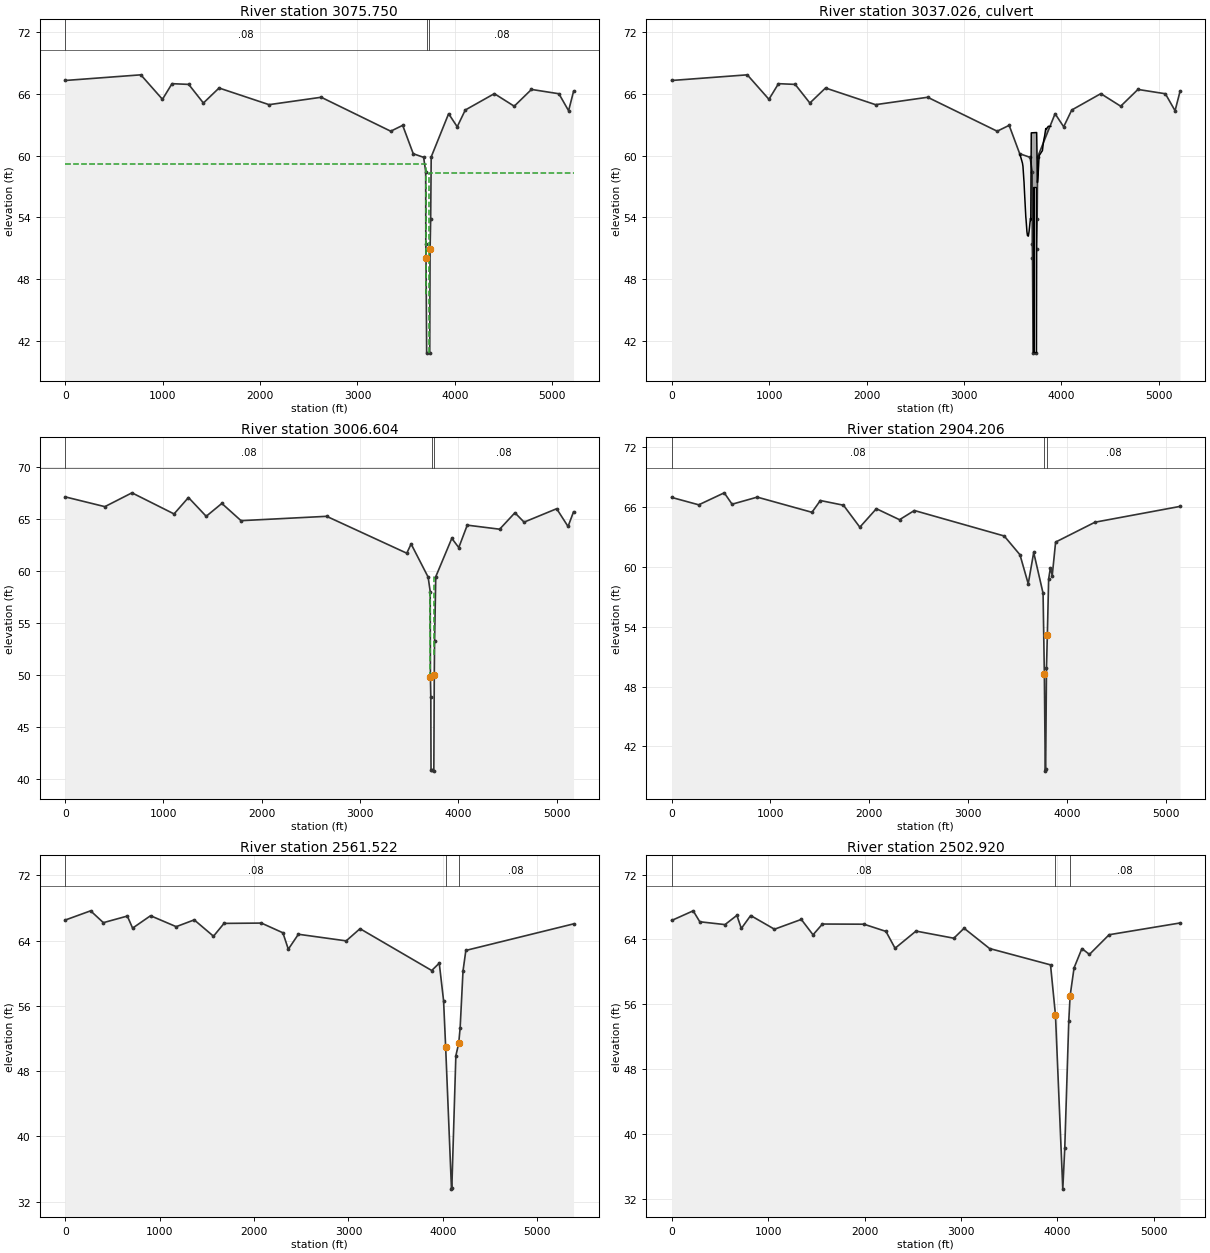
Type RM Length L Ch R = 1 ,3075.750,67.51,69.15,69.4
BEGIN DESCRIPTION:
Stations 3679.01 - 3774.16 developed from survey information (copied from cross-section 3006.349) , and the remainder developed from LiDAR. The elevation of survey points adjusted to match the overall stream slope of approx. .0064 ft/ft.
END DESCRIPTION:
XS GIS Cut Line= 6
     3080291.923    13846920.214     3078981.145    13844326.627
      3078615.28    13843652.795     3078558.688    13843548.565
     3078451.535    13843351.217     3077940.976    13842263.471
#Sta/Elev= 30
       0    67.3  776.22   67.85  998.23   65.47 1096.27   66.99 1267.62   66.92
  1418.4   65.11 1579.27   66.57 2092.45   64.95 2627.46   65.67 3341.05   62.37
 3463.89   62.94 3572.33   60.18 3679.01   59.83 3700.07   58.44 3701.37   51.39
 3703.53   50.09    3710    40.8  3741.6   40.81 3745.08   50.95 3751.17   53.82
 3756.61   59.87 3935.43   64.07 4023.55    62.8  4106.4   64.43 4404.67   66.02
 4608.84    64.8 4785.78   66.43 5067.47   66.01 5166.89   64.36 5217.52   66.23
#Mann= 3 ,-1 , 0
       0     .08       0 3711.53     .06       0 3737.78     .08       0
#XS Ineff= 2 , 0
         3706.18   59.17 3738.72           58.28
Permanent Ineff=
       F       F
Bank Sta=3703.53,3745.08
XS Rating Curve= 0
Exp/Cntr=.5,.3

Type RM Length L Ch R = 2 ,3037.026,,,
BEGIN DESCRIPTION:
Structure 1 - Private Rd.
END DESCRIPTION:
Bridge Culvert--1,0,-1,-1, 0
Deck Dist Width WeirC Skew NumUp NumDn MinLoCord MaxHiCord MaxSubmerge Is_Ogee
1,37,2.6,0, 37, 40, , , .95, 0, 0,0,,
 3573.21 3575.41 3583.58 3600.67 3605.72 3615.01 3616.78 3617.74 3620.97 3634.81
 3637.29 3646.45 3651.87 3661.03 3668.94 3673.21 3677.89 3683.15 3686.01 3690.93
 3746.38 3754.29 3760.59 3771.35 3772.19 3788.42 3791.81 3803.63 3805.49  3815.9
 3822.56 3826.96 3839.63 3845.37  3866.5 3871.21 3891.81
   60.13   60.04   59.83   59.26   58.95   57.62    57.4   57.19   56.55   54.05
   53.79    52.6   52.23   52.17   52.66   53.05   53.49   53.91   53.69   62.21
   62.24   57.38   58.04   59.98      60   60.24   60.29   60.46   60.49   61.31
   61.68   61.85   62.63   62.59   62.85   62.84   62.84
                                                                                
                                                                                
                                                                                
                                                        
 3586.75 3595.75 3603.54 3612.82 3617.87 3620.61 3629.87 3637.68 3639.99 3644.25
 3654.75 3667.22 3673.18 3675.69 3684.24 3686.75 3688.89  3695.3 3705.95 3707.13
 3721.26 3768.25    3770 3774.23 3779.25 3794.86 3805.35 3808.37 3822.66 3825.43
 3828.05  3842.5 3857.81  3860.3 3864.31  3872.3 3876.64 3883.36 3904.66 3905.35
   61.65   61.65   61.21   60.54   60.13   60.07   59.75   59.51   59.43    59.3
   58.67   58.33   58.12   58.21   57.88   58.05    58.2   57.23   56.69   56.16
   61.72   61.96   58.74    59.5   59.85   60.93   61.46   61.62   62.05   62.12
   62.19   62.42   62.45   62.46   62.42   62.27   62.26   62.33   62.33   62.35
                                                                                
                                                                                
                                                                                
                                                                                
Culvert=2,16,14.7,40,.013,.4,1,8,1,40.95,3714.41,40.8,3727.95,Culvert #1  , 0 ,1
Culvert Bottom n=.013
Culvert Bottom Depth=1
Culvert Depth Blocked=1
Culvert=2,16,14.7,40,.013,.4,1,8,1,40.95,3731.41,40.8,3744.95,Culvert #2  , 0 ,1
Culvert Bottom n=.013
BC Design=,, 0 ,, 0 ,,,,,,
BC HTab HWMax=67.85

Type RM Length L Ch R = 1 ,3006.604,101.1,102.4,102.76
Node Photo=V:\TSARP\GIS\W141_00_00\Photos\w141-00-00s1\w141-00-s1p8.JPG
BEGIN DESCRIPTION:
Stations 3692.54 - 3787.69 developed from survey information, and the remainder developed from LiDAR
END DESCRIPTION:
XS GIS Cut Line= 6
     3080359.617    13846921.192     3079058.285    13844330.235
     3078730.311    13843726.191     3078578.286    13843446.199
     3078502.745     13843307.07     3078032.114    13842303.832
#Sta/Elev= 30
       0   67.11  403.42   66.17  679.14    67.5 1107.36   65.47 1253.99   67.05
  1434.5   65.24 1593.63   66.48 1788.95   64.82 2659.85   65.24  3475.1   61.69
 3519.24   62.58 3692.54   59.39 3713.61      58 3715.78   49.79 3719.62   47.89
 3721.93    40.8 3735.77    40.8 3750.38   40.72 3754.99   49.99 3758.06   53.23
 3770.14   59.43 3933.32   63.12 4004.22   62.23 4090.41   64.39 4420.18      64
 4575.35   65.58  4668.7   64.68 5000.07   65.97 5116.05   64.26  5171.8   65.67
#Mann= 3 ,-1 , 0
       0     .08       0 3735.77     .06       0 3750.38     .08       0
#XS Ineff= 2 ,-1
 3705.66 3716.34      58 3756.84 3782.19   59.43
Permanent Ineff=
       F       F
Bank Sta=3715.78,3754.99
XS Rating Curve= 0
Exp/Cntr=.5,.3

Type RM Length L Ch R = 1 ,2904.206,394.22,342.68,276.85
BEGIN DESCRIPTION:
Stations 3737.8 - 3832.95 developed from survey information (copied from cross-section 3006.349) , and the remainder developed from LiDAR. The elevation of survey points adjusted to match the overall stream slope of approx. .0064 ft/ft.
END DESCRIPTION:
XS GIS Cut Line= 6
     3080468.414    13846923.623     3079154.891    13844303.468
     3078820.632    13843687.847     3078772.916    13843599.965
       3078575.8    13843236.928     3078124.043    13842344.543
#Sta/Elev= 30
       0   66.93  274.04   66.19  532.13   67.39   611.4   66.25  866.18   66.96
 1419.89   65.44 1504.81   66.62  1738.7   66.15 1904.42   63.95 2071.78    65.8
 2306.07    64.7 2456.31   65.62 3365.43   63.07 3525.07   61.19 3608.79   58.28
  3664.1   61.42 3758.87   57.34  3771.7   49.36 3771.91   49.24 3781.26   39.53
 3785.15   39.74 3793.57   49.89 3802.21   53.17 3802.31   53.21  3815.4   58.77
 3832.95   59.87 3851.71   59.11 3885.85   62.46 4284.83   64.45 5144.79   66.03
#Mann= 3 ,-1 , 0
       0     .08       0  3771.7     .06       0 3802.31     .08       0
Bank Sta=3771.91,3802.21
XS Rating Curve= 0
Exp/Cntr=.3,.1

Type RM Length L Ch R = 1 ,2561.522,65.76,58.6,58.56
BEGIN DESCRIPTION:
Stations 3962.15 - 4095.46  developed from survey information (copied from cross-section 2446.541) , and the remainder developed from LiDAR. The elevation of survey points adjusted to match the overall stream slope of approx. .0064 ft/ft.
END DESCRIPTION:
XS GIS Cut Line= 6
     3081353.475    13846577.336     3080669.459    13845632.011
      3079249.98    13843420.674     3079102.959    13843352.502
     3078732.813    13843299.897     3078212.893    13842383.891
#Sta/Elev= 30
       0   66.51  269.13   67.64  404.27   66.19  657.94      67  713.97   65.52
   903.9   67.04 1175.68    65.7 1366.69   66.53 1570.58   64.53 1682.36    66.1
 2078.33   66.14 2305.82   64.95 2363.31   62.94 2469.98   64.77 2976.14   63.96
 3123.09   65.45 3882.35   60.33 3962.15   61.23 4007.77   56.65 4029.46   51.08
 4029.68   51.01 4091.64   33.55 4095.46   33.74 4138.02   49.89 4168.43   51.43
 4168.49   51.44 4183.45   53.32 4213.74   60.27 4243.88   62.79 5384.46   66.04
#Mann= 3 ,-1 , 0
       0     .08       0 4029.46     .06       0 4168.49     .08       0
Bank Sta=4029.68,4168.43
XS Rating Curve= 0
Exp/Cntr=.3,.1

Type RM Length L Ch R = 1 ,2502.920,19.75,19.55,20.07
Node Photo=V:\TSARP\GIS\W141_00_00\Photos\w141-00-00s39\w141-00-s39p1.JPG
BEGIN DESCRIPTION:
Stations 3929.3 - 4060.31 developed from survey information (copied from cross-section 2446.541) , and the remainder developed from LiDAR. The elevation of survey points adjusted to match the overall stream slope of approx. .0064 ft/ft.
END DESCRIPTION:
XS GIS Cut Line= 6
     3081353.616    13846511.948     3079794.892    13844242.829
     3079252.708    13843358.629     3079133.857    13843303.518
      3078763.71    13843250.914     3078269.285    13842408.864
#Sta/Elev= 30
       0   66.33  223.17   67.52  291.68   66.17  553.08   65.82   676.4   66.96
  722.39   65.34   819.3   66.94 1066.27   65.25 1344.48   66.46 1466.21   64.56
 1563.45   65.89 1993.96   65.87 2222.52   64.98 2316.91    62.9 2534.08   65.02
 2926.44   64.14 3032.83   65.37 3296.76   62.87  3929.3   60.85 3980.58   54.66
 3980.69   54.64 4056.49   33.17 4077.04   38.25 4118.56   53.91 4132.47   57.03
 4173.42   60.48 4254.73   62.86 4332.75   62.14 4537.07   64.57 5272.16   66.02
#Mann= 3 ,-1 , 0
       0     .08       0 3980.69     .06       0 4132.47     .08       0
Bank Sta=3980.58,4132.47
XS Rating Curve= 0
Exp/Cntr=.5,.3

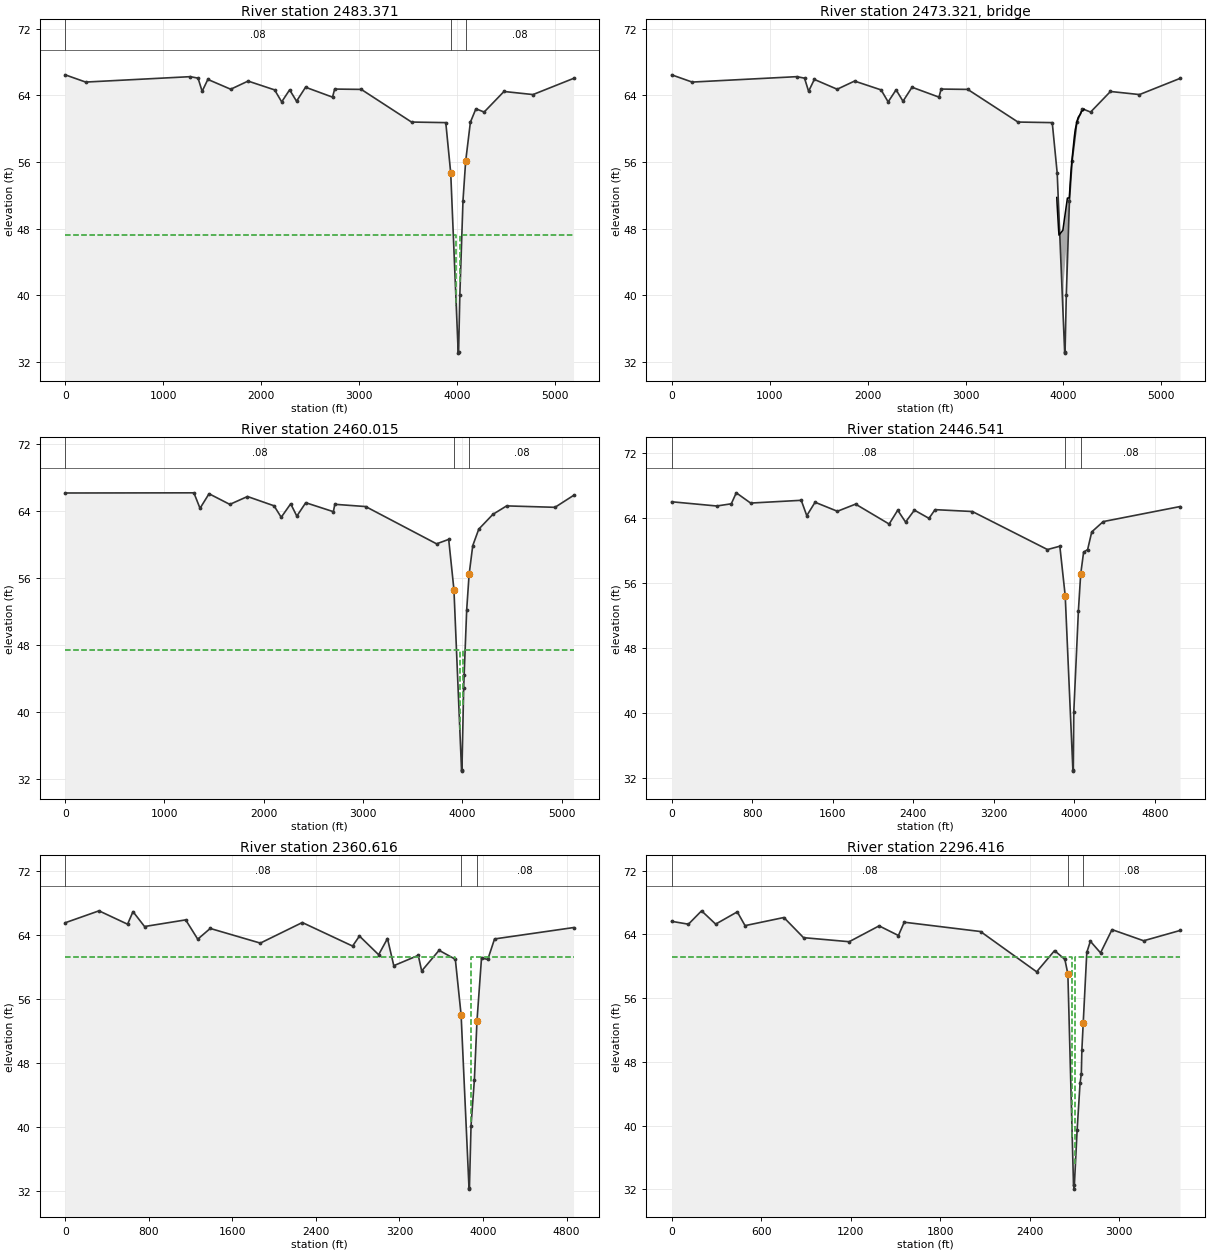
Type RM Length L Ch R = 1 ,2483.371,20.27,23.36,26.63
BEGIN DESCRIPTION:
Stations 3885.65 - 4016.56 developed from survey information (copied from cross-section 2446.541) , and the remainder developed from LiDAR. The elevation of survey points adjusted to match the overall stream slope of approx. .0064 ft/ft.
END DESCRIPTION:
XS GIS Cut Line= 6
     3081353.781    13846435.545     3080794.416    13845665.851
     3079278.623    13843350.184     3079136.274    13843284.178
     3078766.128    13843231.573     3078294.393    13842419.984
#Sta/Elev= 30
       0   66.47  209.04    65.6 1277.37   66.25  1356.4   66.07 1397.99   64.49
 1456.38   65.92 1689.73   64.74 1867.11   65.72  2138.2   64.66 2210.18   63.22
 2291.32   64.67 2361.88    63.3 2454.02   64.98 2729.37   63.79 2750.99   64.76
 3022.89   64.72 3535.62    60.8 3885.65   60.73 3936.23   54.66 4012.74   33.05
 4016.56   33.24 4029.06   39.98 4061.39   51.37 4088.35   56.07 4136.86   60.78
 4193.31   62.39  4277.3      62 4479.92   64.47 4776.43    64.1 5189.97   66.04
#Mann= 3 ,-1 , 0
       0     .08       0 3936.23     .06       0 4088.35     .08       0
#XS Ineff= 2 , 0
         3992.84   47.27 4033.69           47.28
Permanent Ineff=
       F       F
Bank Sta=3936.23,4088.35
XS Rating Curve= 0
Exp/Cntr=.5,.3

Type RM Length L Ch R = 3 ,2473.321,,,
BEGIN DESCRIPTION:
Structure 39 - Private Drive
END DESCRIPTION:
Bridge Culvert--1,0,-1,-1, 0
Deck Dist Width WeirC Skew NumUp NumDn MinLoCord MaxHiCord MaxSubmerge Is_Ogee
7.75,11,2.6,0, 29, 37, , , .95, 0, 0,0,,
 3931.82 3935.19 3943.04 3950.86 3954.22 3993.99 4001.73 4025.73 4040.23 4059.33
 4073.01 4074.61  4085.8 4089.89 4095.96 4111.39 4120.46 4133.91 4136.97  4143.3
 4149.76 4151.02  4151.1 4152.89 4175.35 4181.58 4190.83 4200.93 4212.15
   51.74   50.93   49.32   47.76   47.22   47.81   48.46   50.46   51.67   51.69
   54.24   54.56   56.15   56.63   57.31   59.08    59.9   60.63   60.81   61.09
   61.33   61.35   61.36   61.41   61.78   62.01   62.15   62.16   62.34
                                                   41.41   45.27
                                                                                
                                                                        
 3880.45 3883.44 3888.99  3899.1 3911.39 3914.76 3922.61 3930.43 3933.79 3973.66
  3980.8  4004.8 4024.24 4052.58 4054.18 4065.37 4069.46 4075.53 4090.96 4100.03
 4113.48 4116.54 4122.87 4129.33 4130.59 4130.67 4132.46 4154.92 4161.15  4170.4
  4180.5 4191.72 4201.39 4206.08 4208.35 4222.28 4230.67
   58.03   57.58    56.5    54.3   51.74   50.93   49.32   47.76   47.22   47.77
   48.37   50.38   52.01   54.24   54.56   56.15   56.63   57.31   59.08    59.9
   60.63   60.81   61.09   61.33   61.35   61.36   61.41   61.78   62.01   62.15
   62.16   62.34   62.32   62.32   62.32   62.21   62.17
                                                                                
   41.37   45.61
                                                                                
                                                        
BR Coef=-1 , 0 , 0 ,, 0 ,,,.8,0,,0,
WSPro=,,,, 1 ,,,, 0 ,,,, 0 ,,,,-1 ,-1 ,-1 , 0 , 0 , 0 , 0 , 0
BC Design=,, 0 ,, 0 ,,,,,,
BC HTab HWMax=66.97

Type RM Length L Ch R = 1 ,2460.015,8.67,13.47,15.34
BEGIN DESCRIPTION:
Stations 3862.52 - 3996.15 developed from survey information (copied from cross-section 2446.541) , and the remainder developed from LiDAR. The elevation of survey points adjusted to match the overall stream slope of approx. .0064 ft/ft.
END DESCRIPTION:
XS GIS Cut Line= 6
     3081353.861    13846398.204      3080885.24    13845781.889
     3079279.925    13843343.014     3079137.652    13843265.582
     3078769.485    13843200.054      3078321.81    13842432.126
#Sta/Elev= 30
       0   66.12 1296.29   66.14 1357.85   64.29 1448.73   66.03 1658.03   64.76
 1835.82    65.7 2103.49   64.59 2175.66   63.22 2271.13   64.83 2332.86   63.36
 2422.68   64.96 2700.88   63.89 2715.72   64.77 3026.08    64.5 3740.66   60.05
 3862.52   60.58  3915.3   54.58 3992.31   32.91 3996.15   33.09  4013.4   42.81
 4018.09   44.36 4043.85   52.18 4068.03   56.38 4068.08   56.39 4104.75   59.83
 4165.24    61.8 4307.68   63.57 4446.04   64.58 4933.23   64.41 5119.92   65.83
#Mann= 3 ,-1 , 0
       0     .08       0  3915.3     .06       0 4068.03     .08       0
#XS Ineff= 2 , 0
         3975.61   47.33 4009.79           47.33
Permanent Ineff=
       F       F
Bank Sta=3915.3,4068.08
XS Rating Curve= 0
Exp/Cntr=.5,.3

Type RM Length L Ch R = 1 ,2446.541,67.46,85.93,99.06
Node Photo=V:\TSARP\GIS\W141_00_00\Photos\w141-00-00s39\w141-00-s39p8.JPG
BEGIN DESCRIPTION:
Stations 3854.66 - 3988.47 developed from survey information, and the remainder developed from LiDAR
END DESCRIPTION:
XS GIS Cut Line= 6
      3081353.89    13846384.887     3080900.806    13845788.807
     3079282.852    13843342.176     3079138.485    13843259.239
     3078774.633    13843174.532     3078375.853    13842452.159
#Sta/Elev= 30
       0   65.96  447.17   65.44  591.97   65.71  641.45   67.06  784.09    65.8
  1286.7   66.14 1341.58   64.25 1423.99    65.9  1645.7   64.79 1826.26   65.67
  2159.5   63.22 2244.77   64.92 2322.59   63.46 2410.43   64.93 2555.12   63.92
 2615.61   64.99 2986.04   64.76  3731.7   60.08 3854.66   60.49 3907.99   54.39
 3984.64   32.81 3988.47      33 3993.16   40.09 4039.01   52.56 4061.55   57.04
 4090.54   59.75  4130.7   60.08 4171.36   62.25 4285.22   63.52 5047.85   65.37
#Mann= 3 ,-1 , 0
       0     .08       0 3907.99     .06       0 4061.55     .08       0
Bank Sta=3907.99,4061.55
XS Rating Curve= 0
Exp/Cntr=.3,.1

Type RM Length L Ch R = 1 ,2360.616,36.04,64.2,87.88
BEGIN DESCRIPTION:
Stations 3738.82 - 3870.1 developed from survey information (copied from cross-section 2446.541) , and the remainder developed from LiDAR. The elevation of survey points adjusted to match the overall stream slope of approx. .0064 ft/ft.
END DESCRIPTION:
XS GIS Cut Line= 6
     3081354.248    13846218.567     3079828.273    13844059.867
     3079401.982     13843402.85     3079168.915    13843208.136
     3078762.362    13843037.463      3078411.54    13842437.848
#Sta/Elev= 30
       0   65.53  323.58   67.02  596.97   65.35  648.98   66.92  759.56   65.06
 1153.49   65.89 1268.92   63.48 1388.48   64.82 1868.14   62.99 2269.86   65.56
 2751.25   62.62 2817.12   63.87 3000.67   61.54 3085.33   63.56 3145.78   60.17
 3380.23   61.46 3412.77   59.51 3579.31   62.09 3734.95   60.97  3790.3   54.01
 3866.32   32.27  3870.1   32.45 3885.25   40.19 3917.39   45.93 3942.13   53.25
 3942.18   53.27  3985.5   61.11 4045.94   60.96 4110.43   63.51 4866.59   64.93
#Mann= 3 ,-1 , 0
       0     .08       0  3790.3     .06       0 3942.18     .08       0
#XS Ineff= 2 , 0
          3734.2   61.21 3888.17           61.21
Permanent Ineff=
       F       F
Bank Sta=3790.3,3942.13
XS Rating Curve= 0
Exp/Cntr=.8,.6

Type RM Length L Ch R = 1 ,2296.416,139.77,109.85,154.15
Node Photo=V:\TSARP\GIS\W141_00_00\Photos\w141-00-00s40\w141-00-s40p1.JPG
BEGIN DESCRIPTION:
Stations 3738.42 - 3934.48 developed from survey information, and the remainder developed from LiDAR
END DESCRIPTION:
XS GIS Cut Line= 6
     3081354.339    13846176.221     3079949.026    13844198.296
     3079388.748    13843360.101      3079001.76    13843007.623
     3078851.289    13842981.876     3078530.536    13842356.673
#Sta/Elev= 30
       0   65.65 112.232   65.29 200.394   66.97 294.793    65.3 439.707   66.84
 491.757   65.11  751.98   66.13  883.65    63.61189.594   63.091390.151   65.08
1519.636   63.871558.668   65.542069.999   64.372446.038   59.31 2566.02   61.97
2635.246   60.872655.334   59.03 2693.15   32.482697.478   32.012717.185   39.38
2736.963   45.332745.505   46.492749.111   49.492758.049   52.842782.097   61.74
2805.998   63.152874.212   61.692951.188   64.613163.129   63.21 3406.77    64.5
#Mann= 3 ,-1 , 0
       0     .08       02655.334     .06       02758.049     .08       0
#XS Ineff= 2 , 0
        2684.961   61.212706.069           61.21
Permanent Ineff=
       F       F
Bank Sta=2655.334,2758.049
XS Rating Curve= 0
Skew Angle= 45
Exp/Cntr=.8,.6