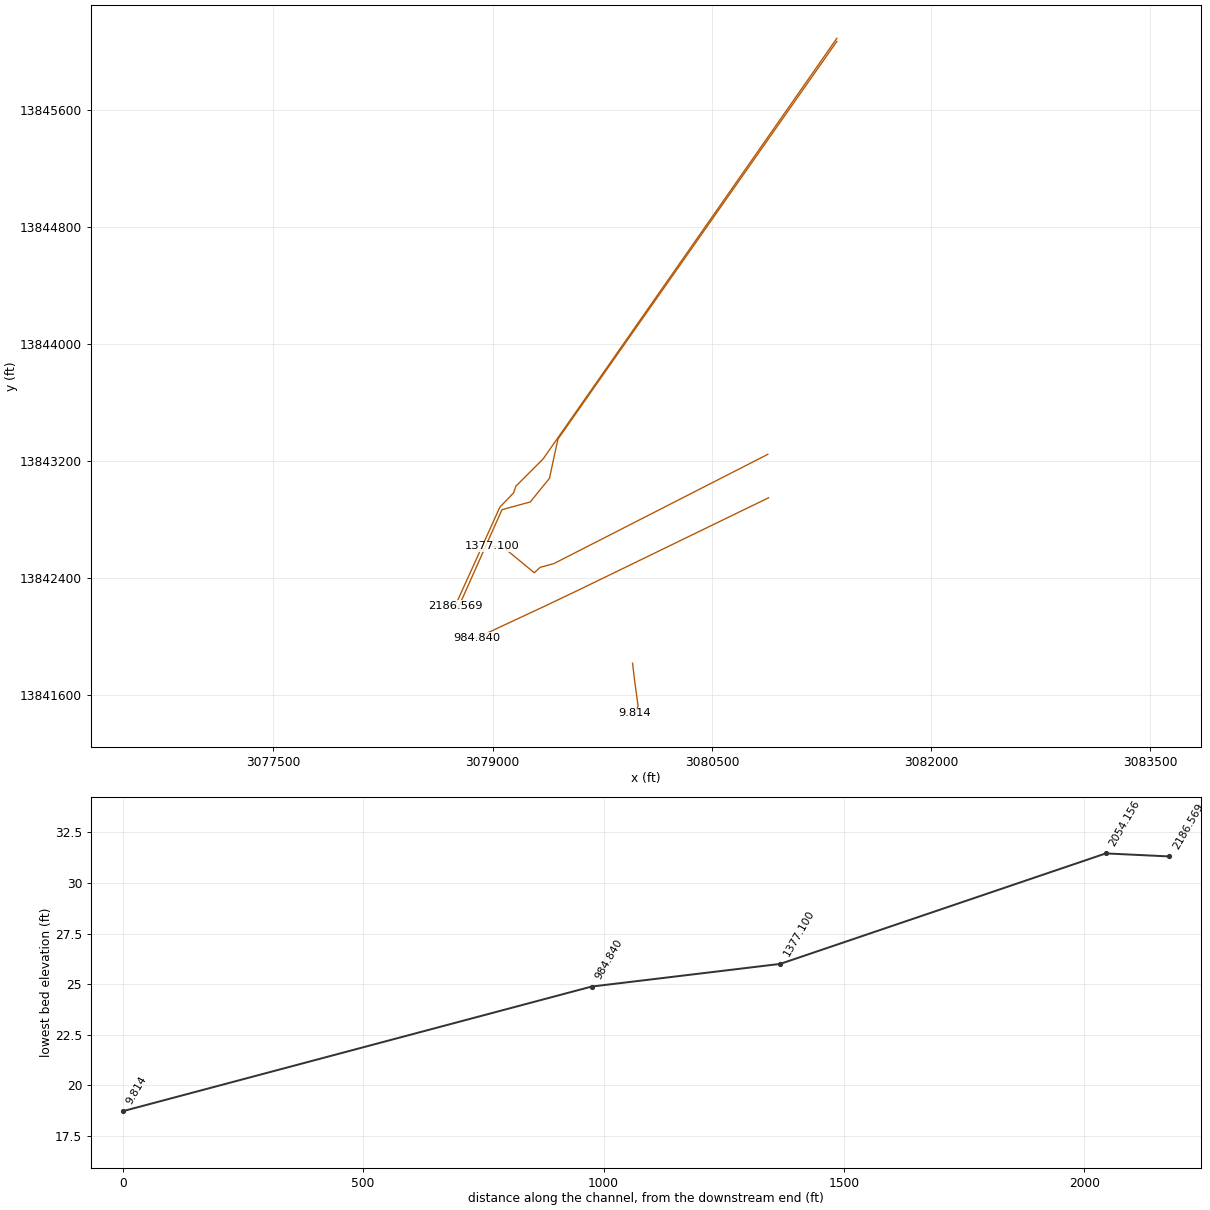
HEC-RAS study W141-00-00.prj: W141-00-00

--- W141-00-00.g01 (geometry) --- (continued)

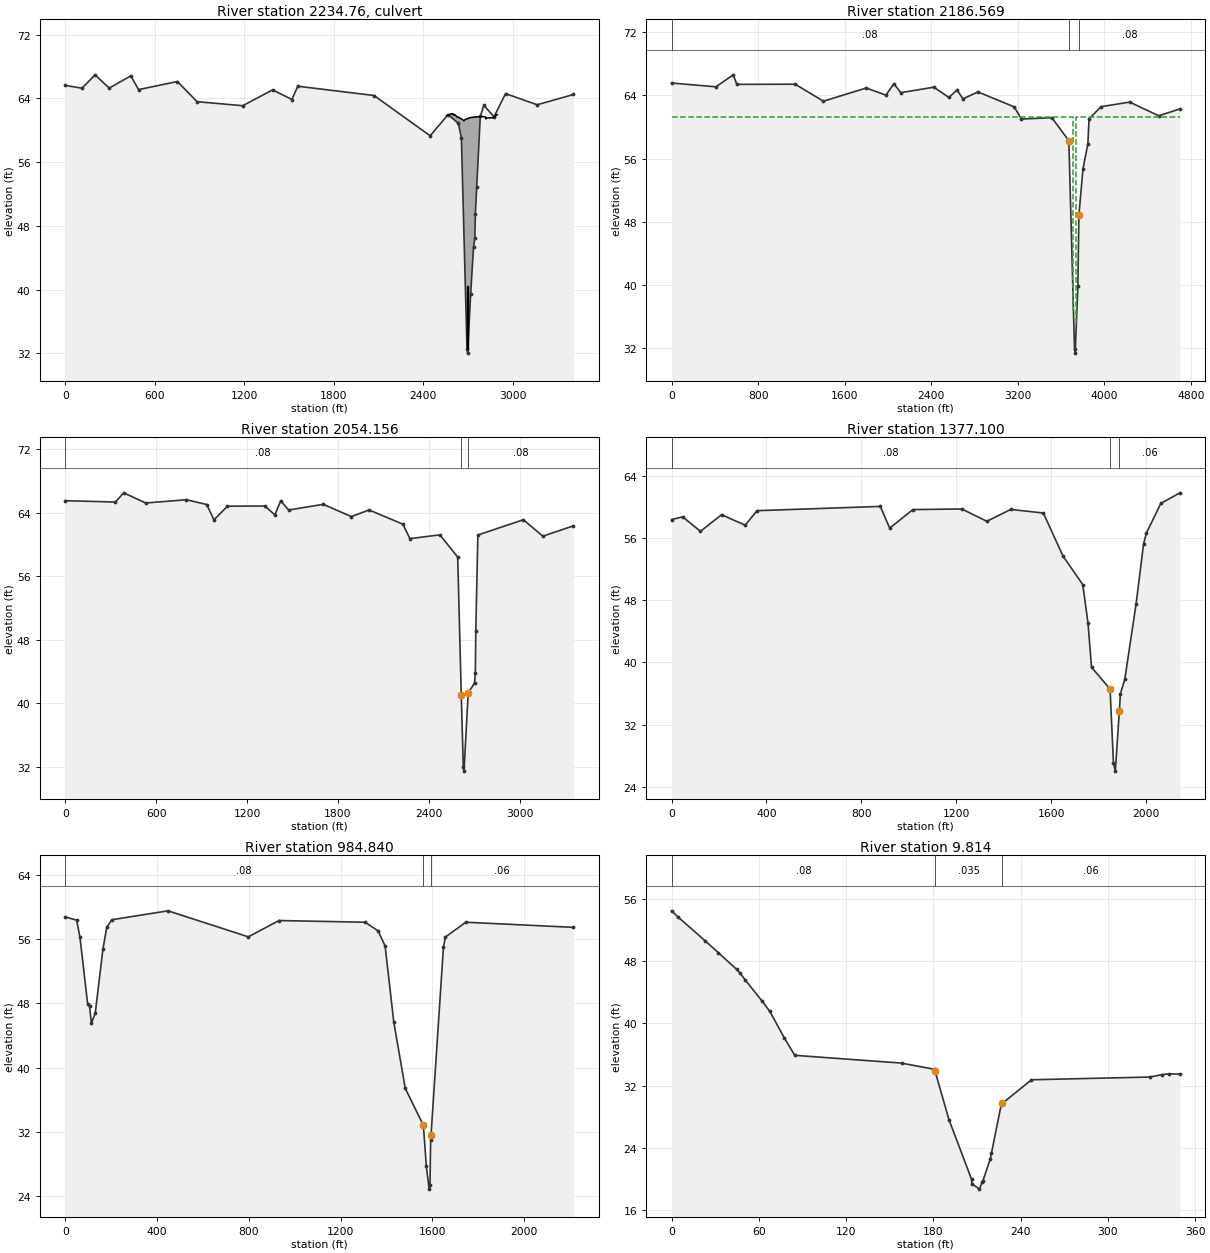
Type RM Length L Ch R = 2 ,2234.76 ,,,
BEGIN DESCRIPTION:
Structure 40 - Memorial
END DESCRIPTION:
Bridge Culvert--1,0,-1,-1, 0
Deck Dist Width WeirC Skew NumUp NumDn MinLoCord MaxHiCord MaxSubmerge Is_Ogee
11,96,2.6,45, 43, 44, , , .95, 0, 0,0,,
 2556.19  2581.6 2583.56 2594.09 2596.67 2597.36 2604.33 2608.86 2613.36 2616.83
 2627.33 2636.31 2642.67 2652.32 2655.78    2658 2659.45 2661.21 2672.09 2678.53
 2710.41 2744.47 2797.06  2817.5 2819.34  2823.9 2830.51 2830.62 2847.11 2849.23
 2849.71 2850.05 2851.91 2862.96 2864.96 2867.83 2875.87 2880.19 2886.44 2887.82
 2888.78 2890.02 2897.37
   61.85      62   62.06   62.09   62.07   62.09    61.9      62   61.89   61.88
   61.65   61.64   61.57   61.47   61.43   61.41    61.4   61.38   61.19   61.33
   61.58   61.67   61.73   61.66   61.42   61.57   61.54   61.54   61.58   61.56
   61.54   61.55   61.57   61.59   61.54   61.63   61.71   61.66   61.91   61.86
   61.92   61.94   61.97
                                                                                
                                                                                
                                                                                
                                                                                
                        
    3175 3566.49 3569.26 3584.15 3587.79 3588.77 3598.63 3605.04  3611.4 3616.31
 3631.16 3643.85 3652.85 3666.49 3671.39 3674.53 3676.58 3679.07 3694.46 3703.56
 3748.65 3796.82 3871.19  3900.1  3902.7 3909.15 3918.49 3918.65 3941.97 3944.97
 3945.65 3946.13 3948.76 3964.38 3967.21 3971.28 3982.64 3988.76 3997.59 3999.54
  4000.9 4002.66 4013.05 4016.06
      62      62   62.06   62.09   62.07   62.09    61.9      62   61.89   61.88
   61.65   61.64   61.57   61.47   61.43   61.41    61.4   61.38   61.19   61.33
   61.58   61.67   61.73   61.66   61.42   61.57   61.54   61.54   61.58   61.56
   61.54   61.55   61.57   61.59   61.54   61.63   61.71   61.66   61.91   61.86
   61.92   61.94   61.97   61.97
                                                                                
                                                                                
                                                                                
                                                                                
                                
Culvert=2,8,8,96,.013,.7,1,8,3,32.47,2695.8,31.6,3727.99,Culvert #1  , 0 ,11
Culvert Bottom n=.013
BC Design=,, 0 ,, 0 ,,,,,,
BC HTab HWMax=66.97

Type RM Length L Ch R = 1 ,2186.569,120.89,132.41,130.62
Node Photo=V:\TSARP\GIS\W141_00_00\Photos\w141-00-00s40\w141-00-s40p8.JPG
BEGIN DESCRIPTION:
Stations 3654.25 - 3858.47 developed from survey information (copied from cross-section 2296.416) , and the remainder developed from LiDAR. The elevation of survey points adjusted to match the overall stream slope of approx. .0064 ft/ft.
END DESCRIPTION:
XS GIS Cut Line= 6
     3081354.524    13846090.682     3079345.122    13843213.165
     3079159.145    13843027.188     3079143.275    13842981.249
     3079049.604    13842883.872     3078744.819    13842210.495
#Sta/Elev= 30
       0   65.58 409.131    65.1 570.101   66.62 602.331   65.41 1142.81   65.43
1402.411   63.27 1798.95   64.95 1981.22   64.04 2054.12   65.49 2119.27   64.36
 2424.07   65.052562.819   63.75 2638.17    64.7 2692.94   63.57 2831.61   64.45
 3167.79   62.553232.459   61.01 3515.26   61.18 3671.83   58.263724.271   31.78
 3730.36   31.31 3755.42   39.84 3764.61    48.8 3802.24   54.67  3847.9   57.87
 3858.47   61.04 3970.24   62.58    4234   63.16 4503.77   61.424698.549    62.3
#Mann= 3 ,-1 , 0
       0     .08       0 3671.83    .035       0 3764.61     .08       0
#XS Ineff= 2 , 0
       0 3714.54   61.21 3741.67       0   61.21
Permanent Ineff=
       F       F
Bank Sta=3671.83,3764.61
XS Rating Curve= 0
Exp/Cntr=.8,.6

Type RM Length L Ch R = 1 ,2054.156,761.41,677.06,596.77
BEGIN DESCRIPTION:
Stations 3645.19 - 3851.01 developed from survey information (copied from cross-section 2296.416) , and the remainder developed from LiDAR. The elevation of survey points adjusted to match the overall stream slope of approx. .0064 ft/ft.
END DESCRIPTION:
XS GIS Cut Line= 6
     3081354.569    13846069.724      3079446.63    13843348.904
     3079388.577    13843080.614     3079257.441    13842919.409
     3079063.874     13842866.43     3078765.033    13842196.706
#Sta/Elev= 30
       0   65.51  331.52   65.34 385.762    66.5 531.575   65.22 799.886   65.63
 933.911   65.03 981.401   63.091070.454   64.821316.223   64.841383.327   63.73
1422.218    65.51474.084   64.341703.024   65.051887.918   63.512005.355   64.34
2228.588   62.552274.289   60.732472.505   61.212589.969   58.41 2613.46   41.03
2627.043   31.932631.356   31.462659.266    41.32700.858   42.552706.331   43.77
  2709.4   49.152723.075   61.19 3023.32   63.113151.851   61.043354.019   62.35
#Mann= 3 ,-1 , 0
       0     .08       0 2613.46    .035       02659.266     .08       0
Bank Sta=2613.46,2659.266
XS Rating Curve= 0
Skew Angle= 45
Exp/Cntr=.3,.1

Type RM Length L Ch R = 1 ,1377.100,360.38,392.26,439.12
BEGIN DESCRIPTION:
Stations 1816.25 - 2037.12 developed from survey information, and the remainder developed from LiDAR
END DESCRIPTION:
XS GIS Cut Line= 6
     3080882.433    13843245.074     3079417.473    13842496.976
      3079324.61    13842472.009     3079285.231    13842434.942
     3079083.048    13842601.405     3078999.602    13842617.213
#Sta/Elev= 30
       0   58.42   46.51   58.76  121.72    56.9  210.53   59.04  310.16   57.69
  360.45   59.56  880.19   60.11  919.59   57.31 1017.32    59.7 1223.47   59.78
 1329.43   58.19 1430.07   59.72 1567.58   59.26 1650.77    53.7 1733.86   50.04
 1755.96    45.1 1770.74   39.38 1848.95   36.59 1849.08   36.59 1863.31      27
 1871.29      26 1888.26   33.79 1888.28    33.8 1892.67   35.97 1911.25   37.85
 1958.83   47.55  1990.3   55.27 2002.16   56.66 2062.89   60.49 2143.58   61.86
#Mann= 3 ,-1 , 0
       0     .08       0 1849.08    .035       0 1888.26     .06       0
Bank Sta=1848.95,1888.28
XS Rating Curve= 0
Exp/Cntr=.3,.1

Type RM Length L Ch R = 1 ,984.840 ,892.44,975.03,1007.3
BEGIN DESCRIPTION:
Stations 1512.65 - 1656.6 developed from survey information, and the remainder developed from LiDAR
END DESCRIPTION:
XS GIS Cut Line= 6
     3080887.736    13842948.074     3079769.485    13842405.009
     3079575.016    13842310.735     3079359.519    13842207.997
     3079003.996     13842041.95     3078891.522    13841989.418
#Sta/Elev= 30
       0   58.78   49.81   58.38   64.25   56.26    97.6   47.99  105.94   47.65
  114.28   45.53  130.95   46.81   164.3   54.74  180.98   57.49  203.21   58.43
  447.78   59.54  797.96    56.3  931.37   58.33 1306.72   58.12 1363.09   57.05
 1393.78   55.16 1431.56   45.69  1481.5   37.43  1560.5   32.83 1560.55   32.81
 1573.39    27.7 1585.79   24.88 1589.19   25.35 1592.32   30.97 1593.88   31.64
 1594.12   31.74 1647.94   55.01  1656.6   56.28  1745.6   58.12 2214.52   57.48
#Mann= 3 ,-1 , 0
       0     .08       0  1560.5    .035       0 1594.12     .06       0
Bank Sta=1560.55,1593.88
XS Rating Curve= 0
Exp/Cntr=.3,.1

Type RM Length L Ch R = 1 ,9.814   ,6.77,9.81,7.67
BEGIN DESCRIPTION:
Stations 158.13 - 247.49 developed from survey information, and the remainder developed from LiDAR
END DESCRIPTION:
XS GIS Cut Line= 4
     3079957.244    13841816.201     3079970.461    13841703.857
     3079995.006    13841524.485     3079974.168     13841473.15
#Sta/Elev= 30
       0   54.45    4.14    53.7   23.06    50.6   32.12   49.08   44.68   46.94
   47.22   46.43   50.45   45.61   62.33   42.84   67.56   41.53   77.43   38.16
   84.68    35.9  158.13    34.9  180.82    34.1  181.12    33.9  181.17   33.87
  190.72   27.65   206.3   19.97  206.53   19.42  211.67   18.72  213.63   19.62
  214.12    19.8  219.01   22.53  219.94   23.31  226.74   29.62   227.5   29.74
  247.49   32.76   328.9   33.11  337.53   33.43  342.01   33.52  349.57   33.49
#Mann= 3 ,-1 , 0
       0     .08       0  181.17    .035       0   227.5     .06       0
Bank Sta=181.12,227.5
XS Rating Curve= 0
Exp/Cntr=.3,.1

Chan Stop Cuts=-1